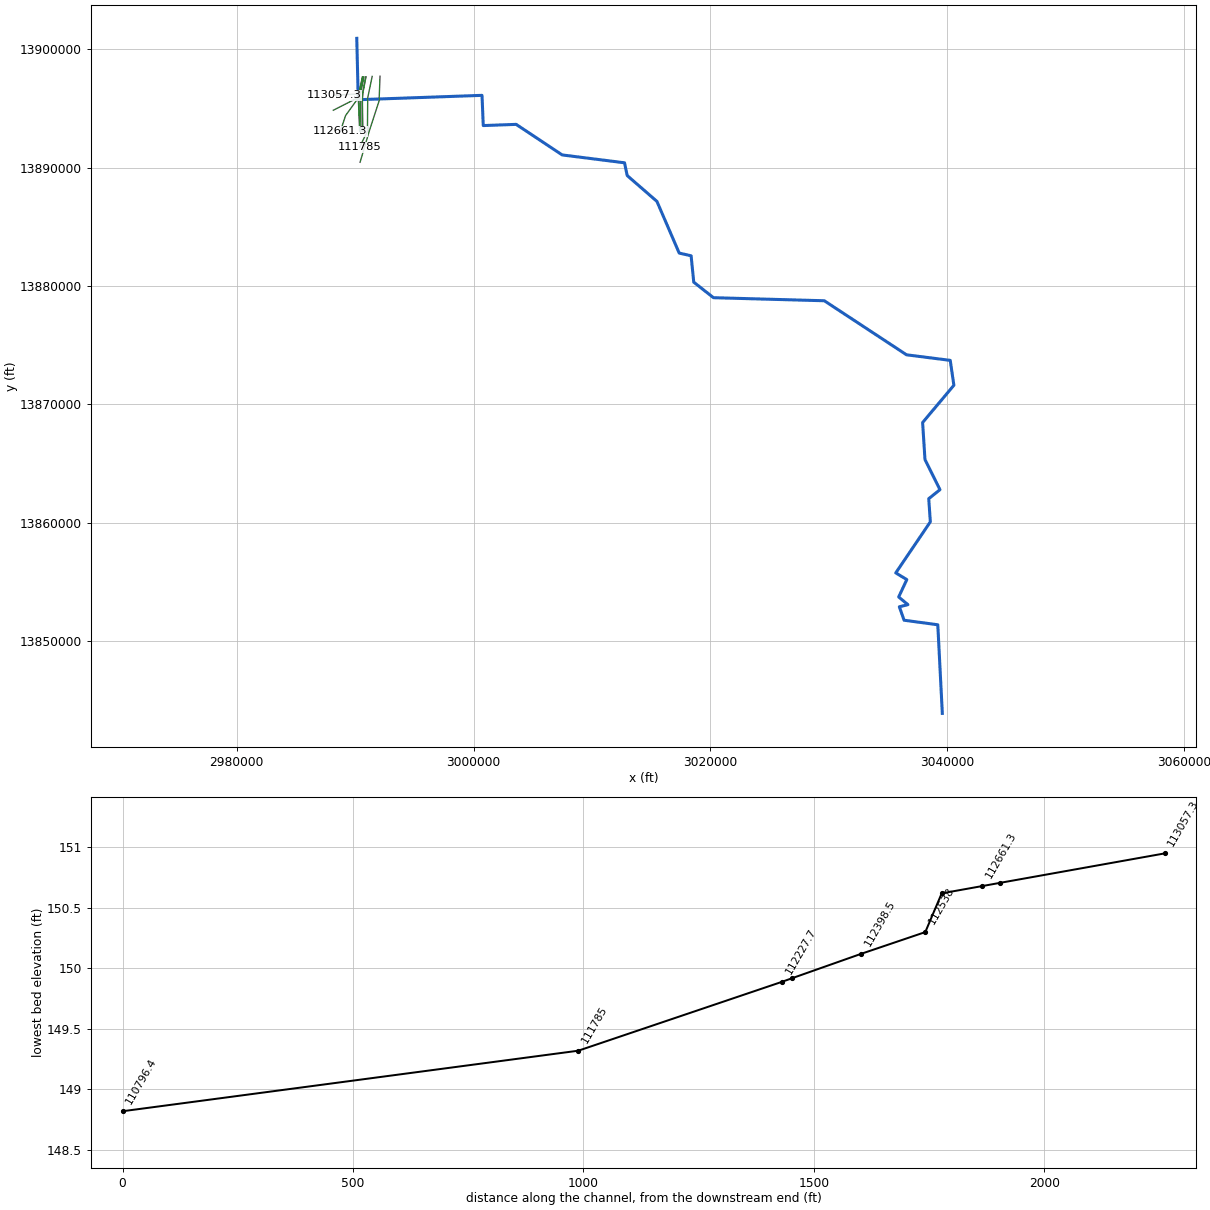
HEC-RAS study U100-00-00.prj: U100-00-00

--- U100-00-00.f01 (steady flow) ---

Flow Title=Effective Multi-Profile 2019
Program Version=4.10
Number of Profiles= 4
Profile Names=10YR,50YR,100YR,500YR
River Rch & RM=U100-00-00,U100-00-00_0383 ,113057.3
     490     819     998    1531
River Rch & RM=U100-00-00,U100-00-00_0383 ,112249.7
     502     839    1022    1568
River Rch & RM=U100-00-00,U100-00-00_0383 ,111785
     529     883    1076    1651
River Rch & RM=U100-00-00,U100-00-00_0383 ,110796.4
     559     933    1137    1744
River Rch & RM=U100-00-00,U100-00-00_0383 ,109730.1
     587     980    1195    1833
River Rch & RM=U100-00-00,U100-00-00_0383 ,108775.4
     619    1033    1260    1932
River Rch & RM=U100-00-00,U100-00-00_0383 ,107760.3
     654    1092    1331    2041
River Rch & RM=U100-00-00,U100-00-00_0383 ,106699.1
     690    1152    1405    2155
River Rch & RM=U100-00-00,U100-00-00_0383 ,105654.6
     730    1218    1486    2278
River Rch & RM=U100-00-00,U100-00-00_0383 ,104580.3
     765    1276    1557    2387
River Rch & RM=U100-00-00,U100-00-00_0383 ,103683.9
     786    1312    1600    2453
River Rch & RM=U100-00-00,U100-00-00_0383 ,103157.1
     821    1371    1672    2564
River Rch & RM=U100-00-00,U100-00-00_0383 ,102304.1
     856    1429    1743    2672
River Rch & RM=U100-00-00,U100-00-00_0383 ,101552.3
     898    1499    1828    2803
River Rch & RM=U100-00-00,U100-00-00_0383 ,100582.2
     949    1583    1931    2960
River Rch & RM=U100-00-00,U100-00-00_0383 ,99531.3
     951    1586    1935    2966
River Rch & RM=U100-00-00,U100-00-00_0383 ,99490.14
     951    1587    1937    2969
River Rch & RM=U100-00-00,U100-00-00_0383 ,97495.54
     986    1610    2044    3112
River Rch & RM=U100-00-00,U100-00-00_0383 ,95544.38
    1020    1705    2086    3259
River Rch & RM=U100-00-00,U100-00-00_0383 ,93740.3
    1054    1762    2158    3400
River Rch & RM=U100-00-00,U100-00-00_0383 ,91427.11
    1098    1837    2254    3591
River Rch & RM=U100-00-00,U100-00-00_0383 ,89382.33
    1138    1906    2343    3768
River Rch & RM=U100-00-00,U100-00-00_0383 ,87061.14
    1186    1988    2448    3980
River Rch & RM=U100-00-00,U100-00-00_0383 ,85584.03
    1218    2042    2517    4121
River Rch & RM=U100-00-00,U100-00-00_0383 ,84358.83
    1245    2088    2575    4242
River Rch & RM=U100-00-00,U100-00-00_0383 ,82566.91
    1285    2157    2664    4425
River Rch & RM=U100-00-00,U100-00-00_0383 ,82288.55
    1425    2418    2691    4456
River Rch & RM=U100-00-00,U100-00-00_0383 ,81201.59
    1532    2574    2802    4580
River Rch & RM=U100-00-00,U100-00-00_0383 ,79381.02
    1619    2700    2996    4795
River Rch & RM=U100-00-00,U100-00-00_0383 ,77984.7
    1723    2849    3155    4967
River Rch & RM=U100-00-00,U100-00-00_0383 ,76425.34
    1842    3018    3342    5167
River Rch & RM=U100-00-00,U100-00-00_0383 ,74744.11
    1967    3194    3556    5391
River Rch & RM=U100-00-00,U100-00-00_0383 ,73088.5
    2105    3387    3780    5621
River Rch & RM=U100-00-00,U100-00-00_0383 ,71377.24
    2135    3429    4027    5869
River Rch & RM=U100-00-00,U100-00-00_0383 ,71022.41
    3338    5332    6296    9378
River Rch & RM=U100-00-00,U100-00-00_0383 ,70575.73
    3500    5597    6428    9803
River Rch & RM=U100-00-00,U100-00-00_0383 ,69460.43
    3569    5710    6770    9983
River Rch & RM=U100-00-00,U100-00-00_0383 ,69001.19
    3696    5918    6916   10314
River Rch & RM=U100-00-00,U100-00-00_0383 ,68180.03
    3865    6194    7185   10753
River Rch & RM=U100-00-00,U100-00-00_0383 ,67130.95
    4070    6532    7544   11287
River Rch & RM=U100-00-00,U100-00-00_0383 ,65911.57
    4197    6739    7985   11614
River Rch & RM=U100-00-00,U100-00-00_0383 ,65193.2
    4404    7080    8256   12149
River Rch & RM=U100-00-00,U100-00-00_0383 ,64058.53
    4575    7362    8703   12590
River Rch & RM=U100-00-00,U100-00-00_0383 ,63161.89
    4873    7839    8810   13330
River Rch & RM=U100-00-00,U100-00-00_0383 ,58763.71
    5185    8337    9354   14099
River Rch & RM=U100-00-00,U100-00-00_0383 ,54446.93
    5522    8875    9921   14926
River Rch & RM=U100-00-00,U100-00-00_0383 ,50060.86
    5575    8960   10533   15057
River Rch & RM=U100-00-00,U100-00-00_0383 ,49388.92
    9892   16013   19258   27615
River Rch & RM=U100-00-00,U100-00-00_0383 ,48823.23
   10043   16350   19654   28263
River Rch & RM=U100-00-00,U100-00-00_0383 ,43528.58
   10194   16688   20052   28915
Boundary for River Rch & Prof#=U100-00-00,U100-00-00_0383 , 1
Up Type= 0
Dn Type= 1
Dn Known WS=97.6
Boundary for River Rch & Prof#=U100-00-00,U100-00-00_0383 , 2
Up Type= 0
Dn Type= 1
Dn Known WS=99.9
Boundary for River Rch & Prof#=U100-00-00,U100-00-00_0383 , 3
Up Type= 0
Dn Type= 1
Dn Known WS=100.8
Boundary for River Rch & Prof#=U100-00-00,U100-00-00_0383 , 4
Up Type= 0
Dn Type= 1
Dn Known WS=102.4
Observed WS=U100-00-00      ,U100-00-00_0383 ,113057.3,0,157.68,157.94,158.05,158.34
Observed WS=U100-00-00      ,U100-00-00_0383 ,112699  ,0,157.23,157.57,157.68,157.97
Observed WS=U100-00-00      ,U100-00-00_0383 ,112661.3,0,157.18,157.53,157.64,157.93
Observed WS=U100-00-00      ,U100-00-00_0383 ,112573.5,0,157.07,157.44,157.55,157.84
Observed WS=U100-00-00      ,U100-00-00_0383 ,112538  ,0,157.07,157.43,157.55,157.84
Observed WS=U100-00-00      ,U100-00-00_0383 ,112398.5,0,156.92,157.18,157.27,157.53
Observed WS=U100-00-00      ,U100-00-00_0383 ,112249.7,0,156.79,156.99,157.05,157.27
Observed WS=U100-00-00      ,U100-00-00_0383 ,112227.7,0,156.4,156.74,156.87,157.17
Observed WS=U100-00-00      ,U100-00-00_0383 ,111785  ,0,156.13,156.39,156.51,156.81
Observed WS=U100-00-00      ,U100-00-00_0383 ,110796.4,0,155.43,155.75,155.87,156.17
Observed WS=U100-00-00      ,U100-00-00_0383 ,109730.1,0,154.8,154.96,155.05,155.37
Observed WS=U100-00-00      ,U100-00-00_0383 ,108775.4,0,152.76,153.47,153.59,153.67
Observed WS=U100-00-00      ,U100-00-00_0383 ,107760.3,0,152.04,152.27,152.37,152.64
Observed WS=U100-00-00      ,U100-00-00_0383 ,106699.1,0,151.58,151.81,151.92,152.19
Observed WS=U100-00-00      ,U100-00-00_0383 ,105654.6,0,151,151.27,151.4,151.71
Observed WS=U100-00-00      ,U100-00-00_0383 ,104580.3,0,150.63,150.9,151.02,151.37
Observed WS=U100-00-00      ,U100-00-00_0383 ,103683.9,0,150.42,150.69,150.81,151.16
Observed WS=U100-00-00      ,U100-00-00_0383 ,103157.1,0,150.22,150.47,150.6,150.98
Observed WS=U100-00-00      ,U100-00-00_0383 ,102624.4,0,150.19,150.44,150.57,150.94
Observed WS=U100-00-00      ,U100-00-00_0383 ,102304.1,0,150.14,150.38,150.51,150.89
Observed WS=U100-00-00      ,U100-00-00_0383 ,102197.2,0,149.91,150.29,150.42,150.82
Observed WS=U100-00-00      ,U100-00-00_0383 ,102116.5,0,149.99,150.29,150.42,150.81
Observed WS=U100-00-00      ,U100-00-00_0383 ,101930.3,0,149.9,150.23,150.37,150.77
Observed WS=U100-00-00      ,U100-00-00_0383 ,101878.4,0,149.88,150.21,150.36,150.76
Observed WS=U100-00-00      ,U100-00-00_0383 ,101828.7,0,149.85,150.2,150.35,150.75
Observed WS=U100-00-00      ,U100-00-00_0383 ,101777.7,0,149.83,150.18,150.33,150.74
Observed WS=U100-00-00      ,U100-00-00_0383 ,101652.2,0,149.77,150.14,150.3,150.71
Observed WS=U100-00-00      ,U100-00-00_0383 ,101602.5,0,149.76,150.14,150.3,150.71
Observed WS=U100-00-00      ,U100-00-00_0383 ,101552.3,0,149.75,150.13,150.29,150.7
Observed WS=U100-00-00      ,U100-00-00_0383 ,101503.3,0,149.74,150.13,150.29,150.7
Observed WS=U100-00-00      ,U100-00-00_0383 ,100582.2,0,149.55,150.04,150.21,150.64
Observed WS=U100-00-00      ,U100-00-00_0383 ,99531.3 ,0,149.44,149.97,150.14,150.58
Observed WS=U100-00-00      ,U100-00-00_0383 ,99490.14,0,149.43,149.97,150.14,150.58
Observed WS=U100-00-00      ,U100-00-00_0383 ,98634.54,0,149.32,149.89,150.06,150.5
Observed WS=U100-00-00      ,U100-00-00_0383 ,97495.54,0,148.98,149.6,149.78,150.21
Observed WS=U100-00-00      ,U100-00-00_0383 ,96771.5 ,0,148.26,148.78,148.99,149.43
Observed WS=U100-00-00      ,U100-00-00_0383 ,96004.46,0,148.09,148.56,148.73,149.07
Observed WS=U100-00-00      ,U100-00-00_0383 ,95544.38,0,147.71,148.14,148.3,148.56
Observed WS=U100-00-00      ,U100-00-00_0383 ,94911.28,0,147.08,147.57,147.71,148.02
Observed WS=U100-00-00      ,U100-00-00_0383 ,94516.37,0,146.64,147.26,147.4,147.72
Observed WS=U100-00-00      ,U100-00-00_0383 ,94452.52,0,146.56,147.2,147.35,147.67
Observed WS=U100-00-00      ,U100-00-00_0383 ,94396.13,0,146.5,147.16,147.31,147.63
Observed WS=U100-00-00      ,U100-00-00_0383 ,94212.15,0,146.31,146.94,147.09,147.43
Observed WS=U100-00-00      ,U100-00-00_0383 ,94148.49,0,146.24,146.86,147.02,147.36
Observed WS=U100-00-00      ,U100-00-00_0383 ,94049.88,0,146.14,146.74,146.9,147.25
Observed WS=U100-00-00      ,U100-00-00_0383 ,93740.3 ,0,145.82,146.37,146.54,146.91
Observed WS=U100-00-00      ,U100-00-00_0383 ,92724.82,0,144.63,145.04,145.19,145.54
Observed WS=U100-00-00      ,U100-00-00_0383 ,92213.05,0,143.78,144.08,144.24,144.58
Observed WS=U100-00-00      ,U100-00-00_0383 ,91427.11,0,142.73,143.17,143.36,143.81
Observed WS=U100-00-00      ,U100-00-00_0383 ,90943.98,0,142.52,142.96,143.13,143.57
Observed WS=U100-00-00      ,U100-00-00_0383 ,90469.36,0,142.31,142.75,142.91,143.33
Observed WS=U100-00-00      ,U100-00-00_0383 ,89756.23,0,142.01,142.44,142.56,142.92
Observed WS=U100-00-00      ,U100-00-00_0383 ,89599.33,0,141.95,142.37,142.49,142.84
Observed WS=U100-00-00      ,U100-00-00_0383 ,89511.89,0,141.95,142.33,142.48,142.84
Observed WS=U100-00-00      ,U100-00-00_0383 ,89382.33,0,141.9,142.27,142.42,142.77
Observed WS=U100-00-00      ,U100-00-00_0383 ,88559.77,0,141.57,141.92,142.05,142.36
Observed WS=U100-00-00      ,U100-00-00_0383 ,87976.86,0,140.6,141.06,141.24,141.75
Observed WS=U100-00-00      ,U100-00-00_0383 ,87851.38,0,140.41,140.95,141.15,141.68
Observed WS=U100-00-00      ,U100-00-00_0383 ,87766.38,0,140.35,140.9,141.1,141.64
Observed WS=U100-00-00      ,U100-00-00_0383 ,87061.14,0,139.89,140.49,140.73,141.31
Observed WS=U100-00-00      ,U100-00-00_0383 ,86116.94,0,139.49,140.1,140.35,140.92
Observed WS=U100-00-00      ,U100-00-00_0383 ,85584.03,0,138.79,139.56,139.84,140.45
Observed WS=U100-00-00      ,U100-00-00_0383 ,84647.29,0,137.86,138.99,139.27,139.85
Observed WS=U100-00-00      ,U100-00-00_0383 ,84525.94,0,137.74,138.92,139.19,139.78
Observed WS=U100-00-00      ,U100-00-00_0383 ,84358.83,0,137.57,138.82,139.09,139.67
Observed WS=U100-00-00      ,U100-00-00_0383 ,83126.72,0,134.65,136.81,137.49,138.68
Observed WS=U100-00-00      ,U100-00-00_0383 ,82787.9 ,0,133.35,135.78,136.6,138.12
Observed WS=U100-00-00      ,U100-00-00_0383 ,82691.01,0,132.98,135.48,136.34,137.95
Observed WS=U100-00-00      ,U100-00-00_0383 ,82566.91,0,132.51,135.1,136.02,137.75
Observed WS=U100-00-00      ,U100-00-00_0383 ,82349.09,0,131.68,134.44,135.44,137.38
Observed WS=U100-00-00      ,U100-00-00_0383 ,82288.55,0,131.44,134.26,135.29,137.28
Observed WS=U100-00-00      ,U100-00-00_0383 ,82214.41,0,131.16,134.03,135.09,137.16
Observed WS=U100-00-00      ,U100-00-00_0383 ,82108.27,0,130.77,133.76,134.82,137.05
Observed WS=U100-00-00      ,U100-00-00_0383 ,82016.73,0,130.59,132.87,133.91,135.94
Observed WS=U100-00-00      ,U100-00-00_0383 ,81201.59,0,129.61,131.96,133.05,135.17
Observed WS=U100-00-00      ,U100-00-00_0383 ,80190.38,0,128.64,131.01,132.11,134.23
Observed WS=U100-00-00      ,U100-00-00_0383 ,79381.02,0,127.85,130.23,131.34,133.42
Observed WS=U100-00-00      ,U100-00-00_0383 ,78709.89,0,127.19,129.58,130.69,132.92
Observed WS=U100-00-00      ,U100-00-00_0383 ,77984.7 ,0,126.47,128.84,129.93,132.15
Observed WS=U100-00-00      ,U100-00-00_0383 ,77900.38,0,126.39,128.76,129.84,132.06
Observed WS=U100-00-00      ,U100-00-00_0383 ,77238.62,0,125.76,128.09,129.17,131.34
Observed WS=U100-00-00      ,U100-00-00_0383 ,76425.34,0,125.04,127.32,128.4,130.55
Observed WS=U100-00-00      ,U100-00-00_0383 ,75591.2 ,0,124.18,126.43,127.51,129.87
Observed WS=U100-00-00      ,U100-00-00_0383 ,75549.38,0,124.15,126.39,127.47,129.84
Observed WS=U100-00-00      ,U100-00-00_0383 ,75528.21,0,123.85,126.12,127.24,129.83
Observed WS=U100-00-00      ,U100-00-00_0383 ,75445.26,0,123.81,126.07,127.19,129.76
Observed WS=U100-00-00      ,U100-00-00_0383 ,75287.42,0,123.73,125.98,127.1,129.62
Observed WS=U100-00-00      ,U100-00-00_0383 ,75169.06,0,123.33,125.45,126.54,128.93
Observed WS=U100-00-00      ,U100-00-00_0383 ,75148.62,0,123.18,125.26,126.37,128.71
Observed WS=U100-00-00      ,U100-00-00_0383 ,75030.15,0,123.04,125.05,126.16,128.41
Observed WS=U100-00-00      ,U100-00-00_0383 ,75026.36,0,122.98,125.05,126.16,128.4
Observed WS=U100-00-00      ,U100-00-00_0383 ,75005.7 ,0,122.64,125.06,126.15,128.36
Observed WS=U100-00-00      ,U100-00-00_0383 ,74959.69,0,122.55,124.97,126.06,128.3
Observed WS=U100-00-00      ,U100-00-00_0383 ,74841.23,0,122.33,124.72,125.81,128.14
Observed WS=U100-00-00      ,U100-00-00_0383 ,74744.11,0,122.14,124.52,125.61,128.01
Observed WS=U100-00-00      ,U100-00-00_0383 ,74216.28,0,120.94,123.34,124.45,127.08
Observed WS=U100-00-00      ,U100-00-00_0383 ,73387.53,0,119.24,121.75,122.92,125.82
Observed WS=U100-00-00      ,U100-00-00_0383 ,73275.78,0,119.19,121.7,122.87,125.84
Observed WS=U100-00-00      ,U100-00-00_0383 ,73218.35,0,118.99,121.47,122.64,125.11
Observed WS=U100-00-00      ,U100-00-00_0383 ,73088.5 ,0,118.78,121.25,122.43,124.88
Observed WS=U100-00-00      ,U100-00-00_0383 ,72791.48,0,118.31,120.76,121.95,124.36
Observed WS=U100-00-00      ,U100-00-00_0383 ,72607.04,0,117.78,120.26,121.49,123.87
Observed WS=U100-00-00      ,U100-00-00_0383 ,72031.7 ,0,117.22,119.82,121.05,123.57
Observed WS=U100-00-00      ,U100-00-00_0383 ,71937.8 ,0,117.13,119.75,120.98,123.52
Observed WS=U100-00-00      ,U100-00-00_0383 ,71849.88,0,117.06,119.69,120.92,123.45
Observed WS=U100-00-00      ,U100-00-00_0383 ,71778.68,0,117.01,119.64,120.87,123.4
Observed WS=U100-00-00      ,U100-00-00_0383 ,71758.34,0,116.99,119.63,120.85,123.38
Observed WS=U100-00-00      ,U100-00-00_0383 ,71756.49,0,116.99,119.63,120.85,123.38
Observed WS=U100-00-00      ,U100-00-00_0383 ,71618.56,0,116.2,118.84,120.06,122.83
Observed WS=U100-00-00      ,U100-00-00_0383 ,71580.98,0,116.16,118.8,120.02,122.8
Observed WS=U100-00-00      ,U100-00-00_0383 ,71474.76,0,116.05,118.69,119.92,122.71
Observed WS=U100-00-00      ,U100-00-00_0383 ,71377.24,0,115.94,118.59,119.82,122.64
Observed WS=U100-00-00      ,U100-00-00_0383 ,71022.41,0,115.56,118.23,119.47,122.35
Observed WS=U100-00-00      ,U100-00-00_0383 ,70575.73,0,115.03,117.75,119,121.91
Observed WS=U100-00-00      ,U100-00-00_0383 ,70200.7 ,0,114.58,117.34,118.6,121.54
Observed WS=U100-00-00      ,U100-00-00_0383 ,69460.43,0,113.97,116.73,117.99,120.9
Observed WS=U100-00-00      ,U100-00-00_0383 ,69001.19,0,113.66,116.4,117.65,120.53
Observed WS=U100-00-00      ,U100-00-00_0383 ,68180.03,0,112.96,115.64,116.87,119.76
Observed WS=U100-00-00      ,U100-00-00_0383 ,67130.95,0,112.36,115.05,116.27,119.16
Observed WS=U100-00-00      ,U100-00-00_0383 ,66957.83,0,112.21,114.89,116.1,118.95
Observed WS=U100-00-00      ,U100-00-00_0383 ,66850.04,0,111.93,114.57,115.77,118.57
Observed WS=U100-00-00      ,U100-00-00_0383 ,66665.68,0,111.75,114.38,115.57,118.36
Observed WS=U100-00-00      ,U100-00-00_0383 ,66117.75,0,111.21,113.81,114.98,117.73
Observed WS=U100-00-00      ,U100-00-00_0383 ,65911.57,0,110.89,113.46,114.62,117.3
Observed WS=U100-00-00      ,U100-00-00_0383 ,65193.2 ,0,110.14,112.7,113.81,116.41
Observed WS=U100-00-00      ,U100-00-00_0383 ,64572.4 ,0,109.57,112.13,113.21,115.76
Observed WS=U100-00-00      ,U100-00-00_0383 ,64058.53,0,109.33,112,113.13,115.75
Observed WS=U100-00-00      ,U100-00-00_0383 ,63538.9 ,0,108.67,111.35,112.47,115.04
Observed WS=U100-00-00      ,U100-00-00_0383 ,63161.89,0,108.43,111.12,112.24,114.76
Observed WS=U100-00-00      ,U100-00-00_0383 ,62946.27,0,108.3,110.99,112.11,114.6
Observed WS=U100-00-00      ,U100-00-00_0383 ,62063.01,0,107.95,110.64,111.75,114.3
Observed WS=U100-00-00      ,U100-00-00_0383 ,61771.35,0,107.84,110.52,111.63,114.18
Observed WS=U100-00-00      ,U100-00-00_0383 ,61237.47,0,107.64,110.31,111.42,113.96
Observed WS=U100-00-00      ,U100-00-00_0383 ,60580.55,0,107.49,110.16,111.27,113.85
Observed WS=U100-00-00      ,U100-00-00_0383 ,60029.36,0,107.28,109.91,111.02,113.59
Observed WS=U100-00-00      ,U100-00-00_0383 ,59531.67,0,107.13,109.73,110.83,113.45
Observed WS=U100-00-00      ,U100-00-00_0383 ,59431.11,0,107.1,109.7,110.8,113.43
Observed WS=U100-00-00      ,U100-00-00_0383 ,59303.02,0,107.06,109.65,110.75,113.39
Observed WS=U100-00-00      ,U100-00-00_0383 ,59170.38,0,106.56,108.95,109.94,112.96
Observed WS=U100-00-00      ,U100-00-00_0383 ,59048.18,0,106.22,108.55,109.53,112.39
Observed WS=U100-00-00      ,U100-00-00_0383 ,58916.32,0,106.14,108.48,109.46,112.34
Observed WS=U100-00-00      ,U100-00-00_0383 ,58763.71,0,106.04,108.39,109.38,112.29
Observed WS=U100-00-00      ,U100-00-00_0383 ,58379.91,0,105.86,108.17,109.16,112.04
Observed WS=U100-00-00      ,U100-00-00_0383 ,58217.4 ,0,105.78,108.08,109.06,111.83
Observed WS=U100-00-00      ,U100-00-00_0383 ,58077.66,0,105.59,107.86,108.82,111.12
Observed WS=U100-00-00      ,U100-00-00_0383 ,57389.92,0,105.2,107.37,108.3,110.56
Observed WS=U100-00-00      ,U100-00-00_0383 ,57319.71,0,105.2,107.39,108.34,110.63
Observed WS=U100-00-00      ,U100-00-00_0383 ,56824.9 ,0,104.97,107.13,108.08,110.34
Observed WS=U100-00-00      ,U100-00-00_0383 ,56770.67,0,104.95,107.11,108.05,110.32
Observed WS=U100-00-00      ,U100-00-00_0383 ,56407.3 ,0,104.81,106.94,107.87,110.16
Observed WS=U100-00-00      ,U100-00-00_0383 ,56080.86,0,104.72,106.81,107.75,109.97
Observed WS=U100-00-00      ,U100-00-00_0383 ,55795.19,0,104.64,106.69,107.61,109.85
Observed WS=U100-00-00      ,U100-00-00_0383 ,55639.65,0,104.6,106.63,107.55,109.78
Observed WS=U100-00-00      ,U100-00-00_0383 ,55604.97,0,104.59,106.62,107.54,109.76
Observed WS=U100-00-00      ,U100-00-00_0383 ,55455.98,0,104.55,106.56,107.47,109.68
Observed WS=U100-00-00      ,U100-00-00_0383 ,55208.76,0,104.49,106.47,107.37,109.55
Observed WS=U100-00-00      ,U100-00-00_0383 ,54863.05,0,104.4,106.34,107.22,109.37
Observed WS=U100-00-00      ,U100-00-00_0383 ,54591.68,0,104.35,106.26,107.14,109.26
Observed WS=U100-00-00      ,U100-00-00_0383 ,54446.93,0,104.32,106.22,107.09,109.2
Observed WS=U100-00-00      ,U100-00-00_0383 ,53835.61,0,104.2,106.05,106.9,108.95
Observed WS=U100-00-00      ,U100-00-00_0383 ,53287.78,0,103.93,105.64,106.46,108.41
Observed WS=U100-00-00      ,U100-00-00_0383 ,52978.66,0,103.77,105.42,106.24,108.29
Observed WS=U100-00-00      ,U100-00-00_0383 ,52832.13,0,103.62,105.23,105.93,107.6
Observed WS=U100-00-00      ,U100-00-00_0383 ,52321.22,0,103.53,105.11,105.79,107.38
Observed WS=U100-00-00      ,U100-00-00_0383 ,51460.62,0,103.42,104.98,105.66,107.25
Observed WS=U100-00-00      ,U100-00-00_0383 ,51306.21,0,103.38,104.93,105.61,107.2
Observed WS=U100-00-00      ,U100-00-00_0383 ,51255.05,0,103.37,104.92,105.6,107.19
Observed WS=U100-00-00      ,U100-00-00_0383 ,51230.64,0,103.36,104.92,105.6,107.19
Observed WS=U100-00-00      ,U100-00-00_0383 ,50649.96,0,103.28,104.83,105.51,107.08
Observed WS=U100-00-00      ,U100-00-00_0383 ,50060.86,0,102.83,104.36,105.04,106.62
Observed WS=U100-00-00      ,U100-00-00_0383 ,49388.92,0,102.79,104.29,104.97,106.53
Observed WS=U100-00-00      ,U100-00-00_0383 ,48823.23,0,102.75,104.24,104.91,106.45
Observed WS=U100-00-00      ,U100-00-00_0383 ,47982.29,0,102.59,104.05,104.7,106.24
Observed WS=U100-00-00      ,U100-00-00_0383 ,46816.39,0,102.31,103.72,104.38,105.91
Observed WS=U100-00-00      ,U100-00-00_0383 ,46039.27,0,102.19,103.57,104.22,105.73
Observed WS=U100-00-00      ,U100-00-00_0383 ,44920.4 ,0,102.06,103.39,104.02,105.5
Observed WS=U100-00-00      ,U100-00-00_0383 ,43528.58,0,101.68,102.92,103.52,104.94
Observed WS=U100-00-00      ,U100-00-00_0383 ,42339.98,0,100.94,102.2,102.82,104.27
Observed WS=U100-00-00      ,U100-00-00_0383 ,41257.1 ,0,100.1,101.45,102.13,103.62
Observed WS=U100-00-00      ,U100-00-00_0383 ,40140.33,0,99.61,101.02,101.76,103.27
Observed WS=U100-00-00      ,U100-00-00_0383 ,39113.75,0,98.76,100.39,101.21,102.75
Observed WS=U100-00-00      ,U100-00-00_0383 ,38317.03,0,97.6,99.9,100.8,102.4
DSS Import GetInterval= 0
DSS Import GetPeak= 0
DSS Import FillOption= 0

--- U100-00-00.f03 (steady flow) ---

Flow Title=SVSQ
Program Version=4.10
Number of Profiles= 8
Profile Names=PF 1,PF 2,PF 3,PF 4,PF 5,PF 6,PF 7,PF 8
River Rch & RM=U100-00-00,U100-00-00_0383 ,113057.3
     387     774    1161    1548    1935    2322    2903    3870
River Rch & RM=U100-00-00,U100-00-00_0383 ,99490.14
     580    1160    1740    2320    2900    3480    4350    5800
River Rch & RM=U100-00-00,U100-00-00_0383 ,82288.55
     823    1646    2470    3293    4116    4939    6174    8232
River Rch & RM=U100-00-00,U100-00-00_0383 ,70575.73
    1777    3554    5331    7108    8885   10662   13328   17770
River Rch & RM=U100-00-00,U100-00-00_0383 ,63161.89
    2122    4243    6365    8486   10608   12730   15912   21216
River Rch & RM=U100-00-00,U100-00-00_0383 ,48823.23
    4024    8048   12073   16097   20121   24145   30182   40242
Boundary for River Rch & Prof#=U100-00-00,U100-00-00_0383 , 1
Up Type= 0
Dn Type= 3
Dn Slope=0.0009
Boundary for River Rch & Prof#=U100-00-00,U100-00-00_0383 , 2
Up Type= 0
Dn Type= 3
Dn Slope=0.0009
Boundary for River Rch & Prof#=U100-00-00,U100-00-00_0383 , 3
Up Type= 0
Dn Type= 3
Dn Slope=0.0009
Boundary for River Rch & Prof#=U100-00-00,U100-00-00_0383 , 4
Up Type= 0
Dn Type= 3
Dn Slope=0.0009
Boundary for River Rch & Prof#=U100-00-00,U100-00-00_0383 , 5
Up Type= 0
Dn Type= 3
Dn Slope=0.0009
Boundary for River Rch & Prof#=U100-00-00,U100-00-00_0383 , 6
Up Type= 0
Dn Type= 3
Dn Slope=0.0009
Boundary for River Rch & Prof#=U100-00-00,U100-00-00_0383 , 7
Up Type= 0
Dn Type= 3
Dn Slope=0.0009
Boundary for River Rch & Prof#=U100-00-00,U100-00-00_0383 , 8
Up Type= 0
Dn Type= 3
Dn Slope=0.0009
DSS Import GetInterval= 0
DSS Import GetPeak= 0
DSS Import FillOption= 0

--- U100-00-00.g01 (geometry) ---

Geom Title=U100-00-00 2019
Program Version=4.10

River Reach=U100-00-00      ,U100-00-00_0383
Reach XY= 30
2990134.08552952 13900916.9181522990259.75850652 13895733.948203
 3000709.257948713896102.71879093000814.9483541113893551.5546019
3003590.6580257713893653.06620993007478.5508405313891071.8909261
3012741.8775841913890408.3860195 3012968.440123213889328.9590445
 3015477.429199713887149.89548933017358.24794461 13882785.997721
3018364.9975715313882554.9988392 3018588.098175213880328.7267169
 3020253.502324713879018.00164813029612.2473866913878759.4818239
 3036554.749249713874195.00440443040244.87507153 13873726.212691
3040549.7842386113871621.95213583037910.5995563613868476.3147263
 3038110.983998113865352.62018633039376.4959027813862808.4254715
3038428.5476674413862046.06643193038562.9876872713860091.4204068
3035644.9584183513855780.6672174 3036577.818101213855216.7054188
3035890.0996603713853745.75724523036673.23031195 13853099.080717
3035945.58248903  13852919.707063036347.3933651913851785.5508638
3039193.2941694413851400.33837963039574.7464905213843920.0022904

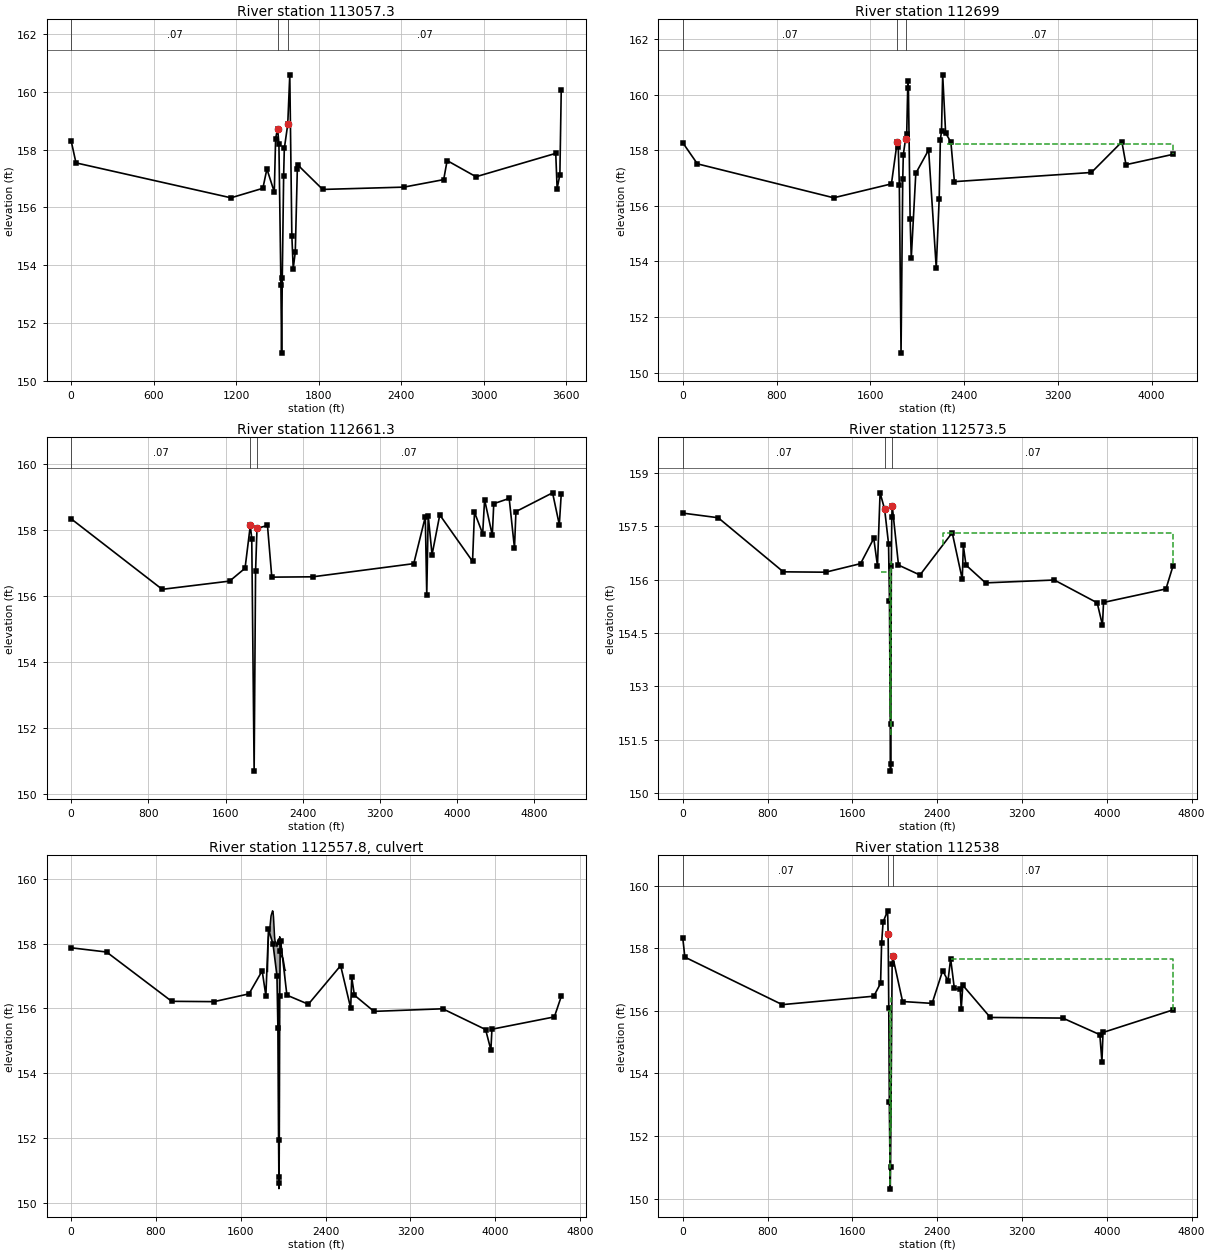
Type RM Length L Ch R = 1 ,113057.3,50.36,358.21,360.14
Node Name=AJ
XS GIS Cut Line= 6
 2990602.002572713897647.20684372990489.5999103613897099.0701447
2990310.6409506913896394.19425792990271.7561859513896207.8150374
2989929.8198619513896202.38000892988187.3604336613896111.2199969
#Sta/Elev= 30
       0   158.3   34.97  157.54 1162.25  156.33 1394.18  156.66 1423.47  157.33
 1477.17  156.53 1486.78  158.38 1501.18  158.73 1510.78  158.21 1525.35  153.32
 1530.31  150.95 1535.27  153.55 1545.19   157.1 1550.16  158.04 1574.97  158.87
  1589.9  160.59 1604.85  155.02 1614.83  153.88 1629.78  154.45 1644.74  157.33
 1649.72  157.46 1829.23  156.62 2419.16   156.7 2709.13  156.96 2734.13  157.62
 2944.11  157.06 3524.04  157.87 3534.04  156.65 3554.04  157.13 3564.04  160.06
#Mann= 3 , 0 , 0
       0     .07       0 1501.18     .04       0 1574.97     .07       0
Bank Sta=1501.18,1574.97
XS Rating Curve= 0 ,0
Exp/Cntr=0.3,0.1

Type RM Length L Ch R = 1 ,112699  ,23.32,37.78,38.35
XS GIS Cut Line= 6
2990633.2997541913897647.77934912990339.4653681113896307.0920698
 2990279.130843113895873.94136142990249.9324106913895850.1175901
2990095.6082442713895835.47916792988155.4438175313894845.5986018
#Sta/Elev= 30
       0  158.27  124.77  157.51 1287.66  156.29 1780.02  156.79 1828.68  158.28
  1838.1  158.13 1847.52  156.74 1862.06 150.706 1876.59  156.95 1881.43  157.84
 1900.81  158.41  1910.5   158.6 1920.19  160.48 1925.03  160.22 1939.57  155.54
 1949.25  154.12 1988.01  157.17 2097.46  158.01  2162.4  153.77 2187.38  156.24
 2197.37  158.38 2207.36  158.68 2217.35  160.71 2242.33  158.62 2287.29  158.29
 2317.27  156.87 3486.26   157.2 3746.04   158.3 3781.01  157.48 4180.66  157.85
#Mann= 3 , 0 , 0
       0     .07       0 1828.68     .04       0 1900.81     .07       0
#XS Ineff= 1 ,-1
 2252.32 4180.66  158.24
Permanent Ineff=
       F
Bank Sta=1828.68,1900.81
XS Rating Curve= 0 ,0
Exp/Cntr=0.3,0.1

Type RM Length L Ch R = 1 ,112661.3,17.62,87.72,175.48
XS GIS Cut Line= 6
2990643.6051797713897647.39746012990282.4828705313895851.1467875
2990251.1364765313895812.79122122990207.0289531913895807.2426759
2989190.2176666113894396.46629792988745.0856828513893054.0552689
#Sta/Elev= 30
       0  158.34  943.75   156.2 1642.79  156.45 1802.56  156.84 1857.29  158.14
 1872.15  157.74 1896.87  150.68 1911.69  156.75 1926.51  158.05 2035.08  158.14
 2079.98  156.57 2504.03  156.58 3551.69  156.98 3671.43   158.4 3686.43  156.04
 3701.42  158.44  3741.4  157.25 3821.36  158.46 4161.18  157.05 4181.18  158.54
 4266.14  157.89 4286.13  158.92 4366.09  157.84 4381.08   158.8 4541.01  158.96
 4595.98  157.45 4610.97  158.56  4990.8  159.13 5060.76  158.16 5080.76   159.1
#Mann= 3 , 0 , 0
       0     .07       0 1857.29     .04       0 1926.51     .07       0
#XS Ineff= 1 ,-1
 2035.08 5080.76  158.14
Permanent Ineff=
       F
Bank Sta=1857.29,1926.51
XS Rating Curve= 0 ,0
Exp/Cntr=0.5,0.3

Type RM Length L Ch R = 1 ,112573.5,48.95,35.57,42.28
BEGIN DESCRIPTION:
Upstream Section - ROAD SOUTH OF HOUSE HAHL
END DESCRIPTION:
XS GIS Cut Line= 6
2990649.6389603613897651.96142732990333.8502218613896106.4536916
2990287.98449995 13895831.2590322990262.9487888713895764.5482074
2990274.4773091113895595.53706252990377.1303190313893072.6244574
#Sta/Elev= 30
       0  157.87   334.1  157.74  948.29  156.22 1347.76  156.21  1677.1  156.45
 1801.65  157.16 1836.52  156.39  1861.2  158.44 1903.95  157.98    1941  157.01
 1949.86  155.41 1959.37  150.62 1961.14  150.81 1962.96  151.95 1967.33  156.39
 1971.63  157.77 1975.94  158.07 2034.84  156.41 2237.24  156.13 2541.63  157.32
 2636.44  156.01 2646.42  156.96 2671.37  156.41    2856  155.91 3504.71  155.99
 3908.91  155.35 3958.81  154.72 3968.79  155.36 4557.63  155.74 4622.51  156.37
#Mann= 3 , 0 , 0
       0     .07       0 1903.95     .04       0 1975.94     .07       0
#XS Ineff= 3 ,-1
 1865.95 1956.47  156.22 1962.47 1975.94   156.5 2451.63 4622.51  157.32
Permanent Ineff=
       F       F       F
Bank Sta=1903.95,1975.94
XS Rating Curve= 0 ,0
Exp/Cntr=0.5,0.3

Type RM Length L Ch R = 2 ,112557.8,,,
BEGIN DESCRIPTION:
ROAD SOUTH OF HOUSE HAHL
END DESCRIPTION:
Node Name=S OF HOUSE HAHL
Bridge Culvert--1,0,-1,-1, 0
Deck Dist Width WeirC Skew NumUp NumDn MinLoCord MaxHiCord MaxSubmerge Is_Ogee
2,24,2.6,0, 20, 20, , , 0.98, 0, 0,0,,
 1851.47 1856.45  1861.2  1870.7 1884.95  1899.2 1903.95  1908.7  1918.2 1922.95
 1932.13    1941 1954.29 1958.72 1967.33 1971.63 1980.24 1997.84 2015.56 2020.38
  157.14  157.92   158.2  158.37  158.85  159.01  158.99  158.81  158.23  158.08
  158.04  157.91  158.13  157.97  158.21  157.71  157.63  157.55   157.2  157.18
       0       0       0       0       0       0       0       0       0       0
       0       0       0       0       0       0       0       0       0       0
 1851.47 1856.45  1861.2  1870.7 1884.95  1899.2 1903.95  1908.7  1918.2 1922.95
 1932.13    1941 1954.29 1958.72 1967.33 1971.63 1980.24 1997.84 2015.56 2020.38
  157.14  157.92   158.2  158.37  158.85  159.01  158.99  158.81  158.23  158.08
  158.04  157.91  158.12  157.97  158.19  157.71  157.63  157.55   157.2  157.18
       0       0       0       0       0       0       0       0       0       0
       0       0       0       0       0       0       0       0       0       0
BR Coef=-1 , 0 , 0 ,, 0 ,,,0.8,-1,,0,
WSPro=,,,, 1 ,,,, 0 ,,,, 0 ,,,,-1 ,-1 ,-1 , 0 , 0 , 0 , 0 , 0
Culvert=1,6,,24.2,0.013,0.5,1,1,3,150.43,1959.47,150.35,1959.47,Culvert #1  , 0 ,1.9
Culvert Bottom n=0.013
BC Design=,, 0 ,, 0 ,,,,,,
BC Use User HTab Curves=0
BC User HTab FreeFlow(D)= 0

Type RM Length L Ch R = 1 ,112538  ,78.66,139.49,132.62
BEGIN DESCRIPTION:
Downstream Section - ROAD SOUTH OF HOUSE HAHL
END DESCRIPTION:
XS GIS Cut Line= 6
2990685.0765535213897649.42829592990369.2878150213896103.9205602
2990323.4220931113895828.72590062990298.38638203 13895762.015076
2990309.9149022713895593.00393112990412.56791219 13893070.091326
#Sta/Elev= 30
       0  158.34   19.52  157.72   938.3   156.2 1801.65  156.47 1865.95  156.88
 1875.45  158.16  1889.7  158.84 1932.13   159.2 1937.21  158.45 1943.23  156.09
 1948.44  153.09 1956.85   150.3 1959.85  151.01 1974.88  157.49 1980.24  157.74
 2073.41   156.3 2352.01  156.24 2451.81  157.29 2501.71  156.96 2526.66  157.67
 2561.59  156.72 2616.48  156.69 2626.46  156.05 2641.43  156.82 2900.92  155.79
 3584.56  155.77 3933.86  155.24 3953.82  154.37  3963.8  155.31 4622.51  156.03
#Mann= 3 , 0 , 0
       0     .07       0 1937.21     .04       0 1980.24     .07       0
#XS Ineff= 3 ,-1
 1932.13 1956.47     156 1962.47 1980.24   156.4 2526.66 4622.51  157.67
Permanent Ineff=
       F       F       F
Bank Sta=1937.21,1980.24
XS Rating Curve= 0 ,0
Exp/Cntr=0.5,0.3

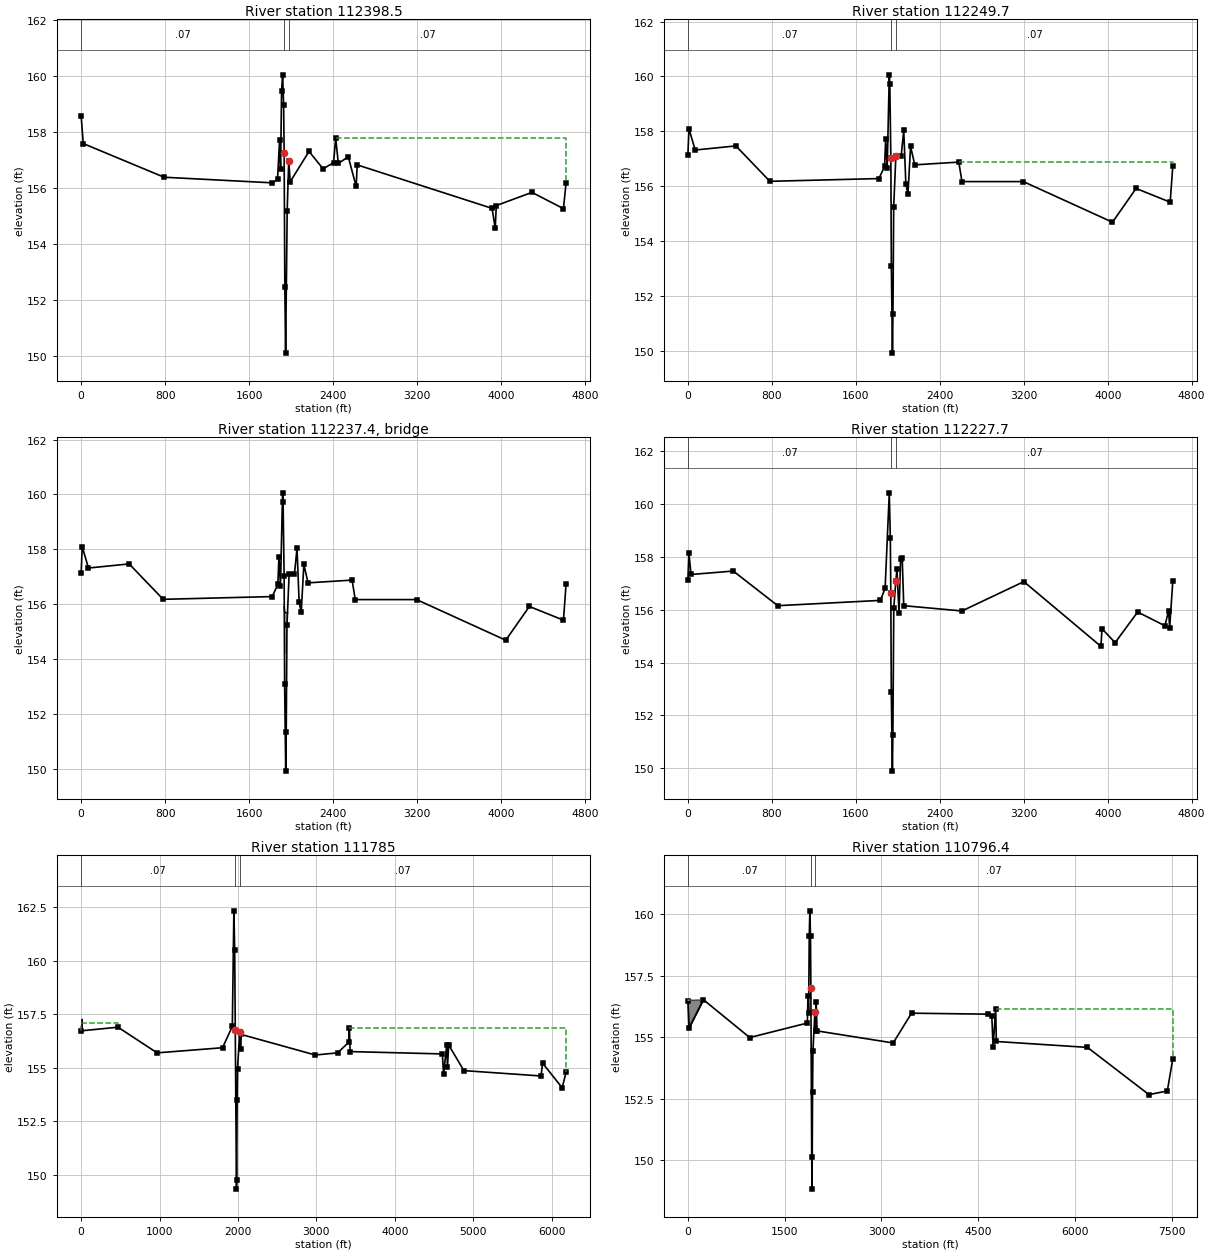
Type RM Length L Ch R = 1 ,112398.5,187.71,148.79,148.56
XS GIS Cut Line= 6
2990741.8864792713897652.93189782990426.9100751113896101.3700404
2990434.8900460313895830.21999212990440.2099172813895694.6500533
2990440.2099172813895396.92984822990488.1940732713893069.6251196
#Sta/Elev= 30
       0  158.57   19.98  157.59  789.11  156.39 1819.95  156.19 1869.01  156.31
  1888.4  157.71 1898.09  156.68 1907.78  159.48 1917.47  160.04 1927.16  158.96
 1932.01  157.25 1938.64  152.47 1946.08  150.12 1961.08   155.2 1975.61  156.98
 1990.15  156.23 2168.78  157.31 2302.86  156.69 2402.76  156.91 2422.74  157.79
 2447.72  156.88 2542.63  157.12 2617.55  156.06 2627.54  156.83 3911.31  155.28
 3941.29  154.57 3951.28  155.38 4290.96  155.85 4590.67  155.27 4615.65  156.19
#Mann= 3 , 0 , 0
       0     .07       0 1932.01     .04       0 1975.61     .07       0
#XS Ineff= 1 ,-1
 2422.74 4615.65  157.79
Permanent Ineff=
       F
Bank Sta=1932.01,1975.61
XS Rating Curve= 0 ,0
Exp/Cntr=0.5,0.3

Type RM Length L Ch R = 1 ,112249.7,21.43,21.99,22.01
BEGIN DESCRIPTION:
Upstream Section - 18" PIPELINE
END DESCRIPTION:
XS GIS Cut Line= 6
2990890.74215269  13897664.538832990631.7879461913896320.4404684
2990587.8178897813895752.13025332990587.2847543713895741.2703668
2990586.6879707713895729.11028622990622.21086562 13893070.874789
#Sta/Elev= 30
       0  157.13    9.94   158.1   69.56  157.32   457.5  157.47  781.19  156.18
 1819.87  156.28 1874.39  156.72  1884.3  157.73 1899.17  156.66    1919  160.06
 1923.95  159.74 1933.87  157.02 1938.59  153.11 1949.06  149.92 1953.88  151.33
 1960.94  155.24 1981.86  157.12 2031.83  157.09 2056.82  158.04  2076.8  156.08
 2096.79  155.71 2121.78  157.45 2161.75  156.78 2581.51  156.88 2611.49  156.17
 3196.14  156.17 4045.64  154.69 4270.51  155.92 4595.32  155.42  4620.3  156.74
#Mann= 3 , 0 , 0
       0     .07       0 1933.87     .04       0 1981.86     .07       0
#XS Ineff= 1 ,-1
 2581.51 4620.21  156.88
Permanent Ineff=
       T
Bank Sta=1933.87,1981.86
XS Rating Curve= 0 ,0
Exp/Cntr=0.5,0.3

Type RM Length L Ch R = 3 ,112237.4,,,
BEGIN DESCRIPTION:
18" PIPELINE
END DESCRIPTION:
Node Name=18" PIPELINE
Bridge Culvert--1,0,-1,-1, 0
Deck Dist Width WeirC Skew NumUp NumDn MinLoCord MaxHiCord MaxSubmerge Is_Ogee
10.5,1.5,2.6,0, 7, 7, , , 0.98, 0, 0,0,,
 1933.87 1938.82 1942.45 1946.07  1949.7 1953.75 1966.87
  155.91  155.72  155.71   155.7  155.69  155.69  155.69
  154.62  154.22  154.21   154.2  154.19  154.19  154.19
 1933.87 1938.82 1942.45 1946.07  1949.7 1953.75 1966.87
  155.91  155.72  155.71   155.7  155.69  155.69  155.69
  154.62  154.22  154.21   154.2  154.19  154.19  154.19
BR Coef=-1 , 0 , 0 ,, 0 ,,,0.8,-1,,0,
WSPro=,,,, 1 ,,,, 0 ,,,, 0 ,,,,-1 ,-1 ,-1 , 0 , 0 , 0 , 0 , 0
BC Design=,, 0 ,, 0 ,,,,,,
BC Use User HTab Curves=0
BC User HTab FreeFlow(D)= 0

Type RM Length L Ch R = 1 ,112227.7,488.08,442.7,445.29
BEGIN DESCRIPTION:
Downstream Section - 18" PIPELINE
END DESCRIPTION:
Node Name=AI
XS GIS Cut Line= 6
2990912.7211113613897665.35739792990653.7669048613896321.2590363
2990609.7968484513895752.94882122990609.2637130313895742.0889348
2990608.6669294413895729.92885412990644.1898242813893071.6933569
#Sta/Elev= 30
       0  157.11    9.94  158.13   29.81  157.33   432.6  157.46  855.89  156.15
 1834.73  156.35 1879.34  156.81    1919  160.42 1928.91  158.72 1933.49  156.63
 1938.25  152.88 1948.47  149.89 1953.22  151.26  1961.8  156.07 1981.86  157.09
 1991.85  157.52 2011.84  155.87 2026.83  157.92 2041.83  157.97 2056.82  156.15
 2611.49  155.95 3201.14  157.06 3935.71  154.61  3945.7  155.28 4070.63  154.75
  4285.5  155.91 4545.35  155.39 4580.33  155.96 4590.32  155.31  4620.3  157.07
#Mann= 3 , 0 , 0
       0     .07       0 1933.49     .04       0 1981.86     .07       0
#XS Ineff= 1 ,-1
 3201.14  4620.3  157.06
Permanent Ineff=
       T
#Block Obstruct= 2 , 0
       0    9.94  158.13               0
Bank Sta=1933.49,1981.86
XS Rating Curve= 0 ,0
Exp/Cntr=0.5,0.3

Type RM Length L Ch R = 1 ,111785  ,895.44,988.65,969.67
XS GIS Cut Line= 6
2991434.3161967713897701.33862522991047.0298978513895838.3498971
2991055.9399850213895684.1901004 2991044.810742213894305.9212034
2991034.9121399413893080.0936026 2990366.884932713891711.9178613
#Sta/Elev= 30
       0  156.72  469.46  156.89  968.89  155.69 1802.93  155.93 1927.72  156.93
 1947.65  162.33 1957.61  160.52 1965.41  156.74 1980.65  149.32 1983.28  149.73
 1989.04  153.48 1994.07  154.95 2022.37  156.67 2032.33  155.86 2042.29  156.55
  2986.1  155.59 3270.75  155.69 3410.58  156.18 3420.56  156.87 3430.55  155.75
 4606.59  155.64 4621.54  154.68  4661.4  156.05 4671.39  155.01 4686.36  156.06
 4881.05  154.86 5864.49  154.61 5884.46  155.21 6134.06  154.06 6183.98  154.78
#Mann= 3 , 0 , 0
       0     .07       0 1965.41     .04       0 2022.37     .07       0
#XS Ineff= 2 ,-1
       0  469.46  157.07 3420.56 6183.98  156.87
Permanent Ineff=
       F       T
#Block Obstruct= 2 , 0
       0    9.99  157.29               0
Bank Sta=1965.41,2022.37
XS Rating Curve= 0 ,0
Exp/Cntr=0.3,0.1

Type RM Length L Ch R = 1 ,110796.4,1102.78,1066.3,1044.45
XS GIS Cut Line= 5
 2992097.570119613897717.5213356 2992028.109956713895876.6598599
2992049.5000057813895722.50006322991188.99516511  13893086.31964
2990413.4957318613890453.0151954
#Sta/Elev= 30
       0  156.45   14.98  155.36  239.63  156.52  958.53  154.98  1851.9  155.57
 1861.63  156.68 1871.36  155.97 1881.09   159.1 1890.81  160.13 1900.54  159.09
 1906.27  157.01 1919.25  150.12 1924.79  148.82 1932.18  152.77 1938.36  154.42
 1968.63  156.03 1978.36  155.26 1988.09  156.41 2002.81  155.25 3181.98  154.76
 3466.78  155.97 4650.96  155.93 4710.92  155.84 4730.91  154.59 4770.88  156.16
 4780.86  154.82 6193.34  154.58 7146.65  152.66 7431.14  152.81 7515.99  154.12
#Mann= 3 , 0 , 0
       0     .07       0 1906.27     .04       0 1968.63     .07       0
#XS Ineff= 3 ,-1
       0  239.63  156.52 3466.78 4770.88  155.97 4770.88 7515.99  156.16
Permanent Ineff=
       F       F       T
#Block Obstruct= 2 , 0
       0  239.63  156.52               0
Bank Sta=1906.27,1968.63
XS Rating Curve= 0 ,0
Exp/Cntr=0.3,0.1