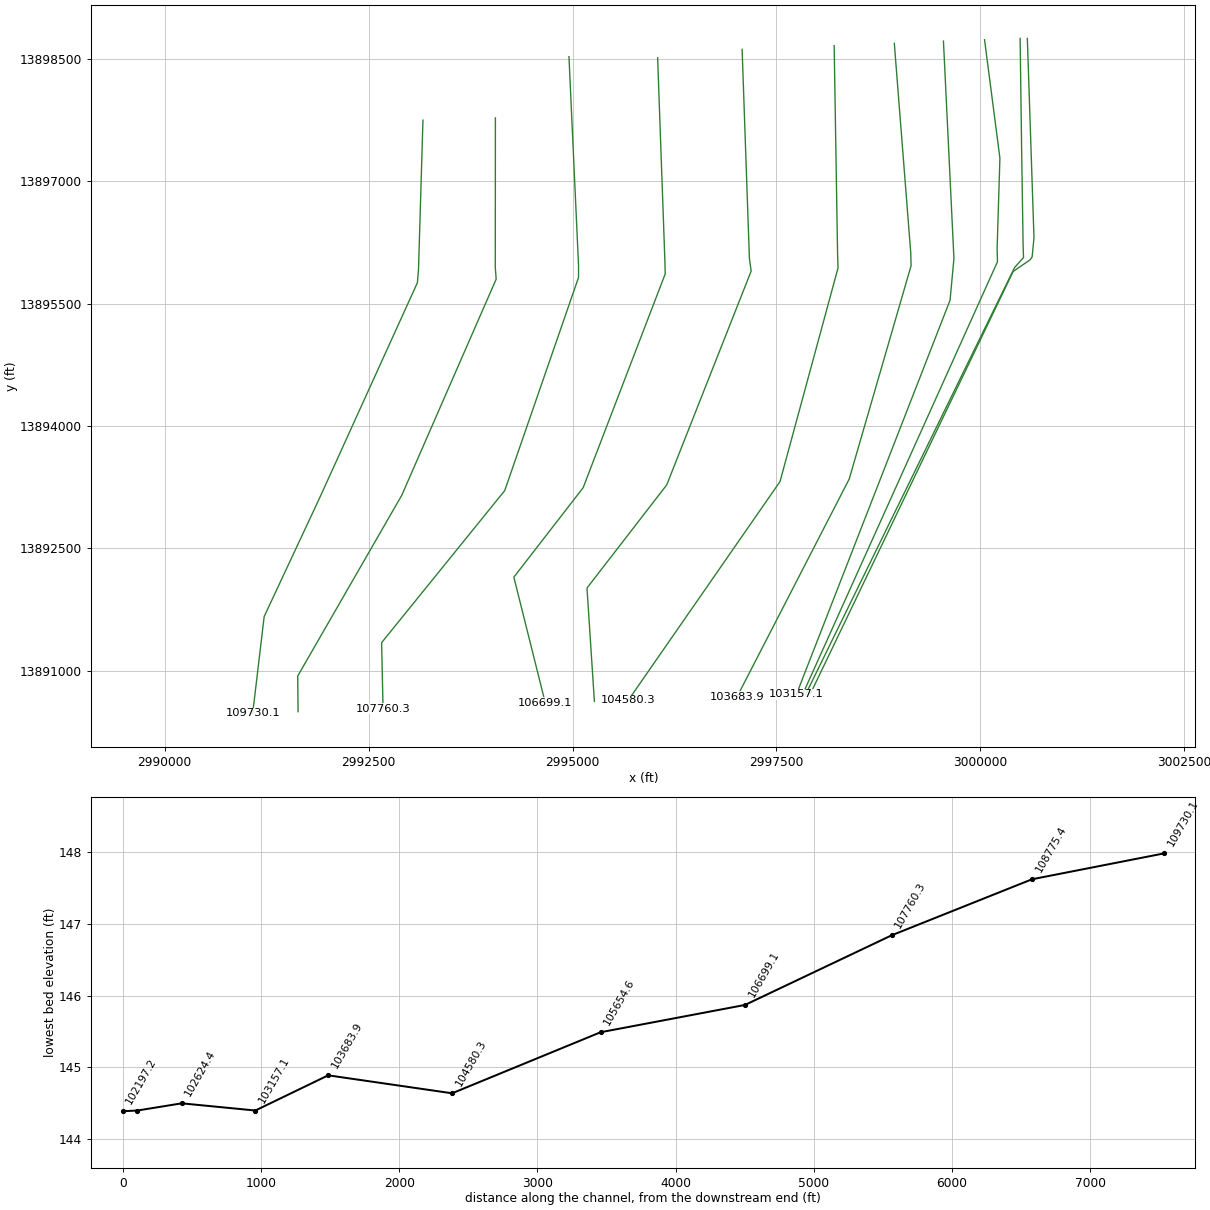
HEC-RAS study U100-00-00.prj: U100-00-00

--- U100-00-00.g01 (geometry) --- (continued)

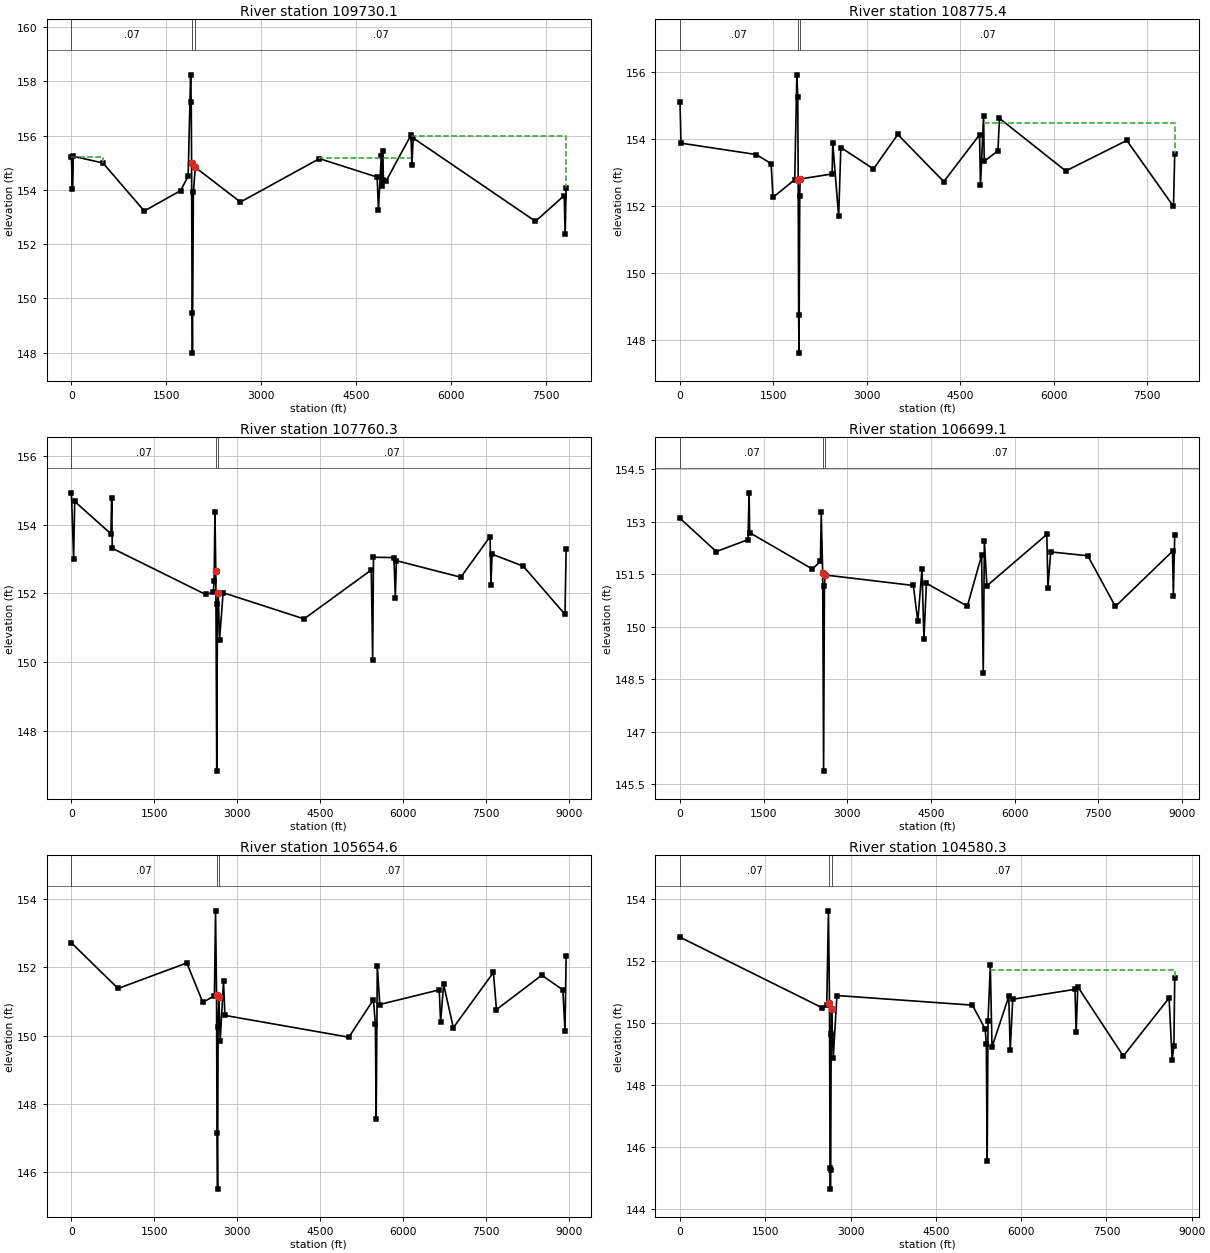
Type RM Length L Ch R = 1 ,109730.1,958.45,954.68,967.28
XS GIS Cut Line= 6
  2993167.03353113897748.4753419  2993112.55004513895918.5400254
 2993099.190163613895756.3700742 2991899.194532113893115.0167611
    2991221.0208   13891664.7626   2991080.28808   13890477.7968
#Sta/Elev= 30
       0  155.21   14.97  154.04   24.94  155.24  498.84  154.99 1152.32  153.22
 1725.99  153.97 1845.53   154.5 1884.98  158.24 1894.84  157.22 1900.34  154.99
 1908.42  149.46 1913.37  147.98 1928.59  153.91 1958.95  154.83 2672.56  153.55
 3920.91  155.15 4834.69  154.47 4854.66  153.25  4899.6  155.25  4909.6  154.14
 4919.59  155.43 4934.58  154.37 4979.54  154.34 5369.24  156.02 5384.22  154.92
 5404.21  155.91  7337.7  152.84 7792.34  153.79 7807.33  152.36 7822.32  154.08
#Mann= 3 , 0 , 0
       0     .07       0 1900.34     .04       0 1958.95     .07       0
#XS Ineff= 3 ,-1
       0  498.84  155.21 3920.91 5369.21  155.19 5369.21 7822.32     156
Permanent Ineff=
       F       F       F
#Block Obstruct= 2 , 0
       0   24.94  155.24               0
Bank Sta=1900.34,1958.95
XS Rating Curve= 0 ,0
Exp/Cntr=0.3,0.1

Type RM Length L Ch R = 1 ,108775.4,1039.28,1015.05,1084.19
XS GIS Cut Line= 6
  2994054.86968213897775.5950384 2994053.530118513895944.3798688
 2994064.229900213895799.1400018 2992907.186282513893150.5114408
   2991632.13998   13890935.6963   2991636.61025   13890498.6965
#Sta/Elev= 30
       0  155.12   14.97  153.89 1222.47  153.55 1461.98  153.28 1491.92  152.27
 1840.93   152.8 1874.91  155.93 1889.47  155.27 1896.46   152.8 1904.07  148.76
 1909.52  147.62 1921.66   152.3 1928.31  152.82 2441.11  152.97 2451.09  153.89
 2545.94   151.7 2580.88  153.76 3105.04  153.12 3494.41  154.15 4233.21  152.74
 4807.26  154.14 4822.24  152.63 4872.16  154.71 4882.15  153.35 5101.97  153.66
 5126.95  154.63 6191.08  153.06 7170.28  153.97 7919.67     152 7939.65  153.58
#Mann= 3 , 0 , 0
       0     .07       0 1896.46     .04       0 1928.31     .07       0
#XS Ineff= 2 ,-1
 3494.41 4872.16  154.15 4872.16 7939.65   154.5
Permanent Ineff=
       F       F
Bank Sta=1896.46,1928.31
XS Rating Curve= 0 ,0
Exp/Cntr=0.3,0.1

Type RM Length L Ch R = 1 ,107760.3,1060.49,1061.26,981.47
Node Name=AH
XS GIS Cut Line= 6
  2994956.45219713898526.2349413 2995073.8200726 13895967.550098
 2995073.820072613895820.5198803  2994169.37076613893208.4306163
   2992660.40112   13891344.6536   2992677.88032   13890536.8024
#Sta/Elev= 30
       0  154.92   39.94     153   59.92  154.67  713.99  153.73  728.97  154.77
  738.95  153.31 2426.57  151.97 2566.28  152.03 2580.98  152.35 2595.68  154.35
 2611.03  152.66 2628.58  146.84 2640.96  151.68 2654.49  152.02    2679  150.66
  2743.4  152.02 4207.99  151.26 5422.66  152.68 5447.65  150.08 5462.65  153.05
 5832.47  153.04 5857.46  151.88 5877.45  152.95 7041.88  152.47 7571.61  153.65
 7586.61  152.24  7606.6  153.14 8171.32  152.79 8925.96  151.39 8945.95  153.29
#Mann= 3 , 0 , 0
       0     .07       0 2611.03     .04       0 2654.49     .07       0
#XS Ineff= 1 ,-1
 5462.65 8945.95  153.05
Permanent Ineff=
       F
Bank Sta=2611.03,2654.49
XS Rating Curve= 0 ,0
Exp/Cntr=0.3,0.1

Type RM Length L Ch R = 1 ,106699.1,1036.6,1044.52,1005.47
XS GIS Cut Line= 6
  2996043.22134913898511.7825423 2996132.419989513896011.2101157
 2996135.989864313895863.2999784 2995130.431179913893243.6943253
   2994281.01615   13892147.1034   2994666.72365   13890604.2904
#Sta/Elev= 30
       0   153.1  649.26  152.15 1218.62  152.49  1238.6  153.83 1248.58  152.69
 2372.31  151.65 2516.96  151.87 2531.75  153.28 2557.39  151.53 2573.84  145.87
 2588.93  151.16  2600.8  151.48 4182.92  151.18 4262.81  150.15  4337.7  151.65
 4372.65  149.65 4417.59  151.24 5151.54  150.59 5406.18  152.04 5436.13  148.68
 5456.11  152.46 5501.07  151.17 6575.34  152.64 6595.32  151.12 6645.29  152.14
 7309.83  152.03 7804.49  150.58 8828.74  152.16 8843.73  150.88 8868.71  152.63
#Mann= 3 , 0 , 0
       0     .07       0 2557.39     .04       0  2600.8     .07       0
#XS Ineff= 1 ,-1
 5456.11 8868.71  152.46
Permanent Ineff=
       F
Bank Sta=2557.39,2600.8
XS Rating Curve= 0 ,0
Exp/Cntr=0.3,0.1

Type RM Length L Ch R = 1 ,105654.6,1083.05,1074.21,1230.57
XS GIS Cut Line= 6
  2997078.59887113898615.8830559 2997167.859847813896055.7700659
 2997189.240054413895898.0499089 2996155.261807413893278.9573781
   2995177.41008   13892014.0212   2995268.20786    13890624.104
#Sta/Elev= 30
       0  152.72   843.9  151.38 2087.29  152.13 2376.91  150.97 2586.53  151.17
 2606.43  153.66 2624.95   151.2 2633.03  147.15 2643.65  145.49 2652.71  150.26
 2666.12  151.14 2690.99  149.85 2750.78   151.6 2775.75  150.59  5017.4  149.95
 5461.75  151.05  5496.7  150.33 5511.68  147.56 5531.65  152.05 5576.63  150.91
 6651.53  151.34 6676.53   150.4 6731.52   151.5  6906.5  150.23 7631.43  151.85
 7686.43  150.76 8506.32  151.77 8886.25  151.34 8926.24  150.14 8946.23  152.32
#Mann= 3 , 0 , 0
       0     .07       0 2624.95     .04       0 2666.12     .07       0
#XS Ineff= 1 ,-1
 5531.65 8946.23  152.05
Permanent Ineff=
       F
Bank Sta=2624.95,2666.12
XS Rating Curve= 0 ,0
Exp/Cntr=0.3,0.1

Type RM Length L Ch R = 1 ,104580.3,892.28,896.41,865.2
XS GIS Cut Line= 5
2998206.8229929513898660.89937012998248.7399038713896100.3198456
2998254.0801162713895936.35987172997543.1615906113893318.7519179
2995682.4920836113890637.1995383
#Sta/Elev= 30
       0  152.76 2496.04  150.49 2580.82  150.56 2610.65  153.61 2628.97  150.63
 2638.58  145.32 2644.99  144.64 2650.78  145.25 2658.12  149.63 2665.33  150.43
 2695.16  148.88 2759.95  150.88 5142.69  150.57 5367.48   149.8 5387.46  149.33
 5402.45  145.56 5417.43  150.06 5457.41  151.85  5487.4  149.22  5782.3  150.85
 5807.29  149.12 5852.28  150.76 6946.92  151.08 6966.92   149.7 6996.91  151.16
 7796.65  148.93 8601.36   150.8 8656.34  148.81 8686.33  149.25 8701.32  151.45
#Mann= 3 , 0 , 0
       0     .07       0 2628.97     .04       0 2665.33     .07       0
#XS Ineff= 1 ,-1
 5457.41 8701.32   151.7
Permanent Ineff=
       F
Bank Sta=2628.97,2665.33
XS Rating Curve= 0 ,0
Exp/Cntr=0.3,0.1

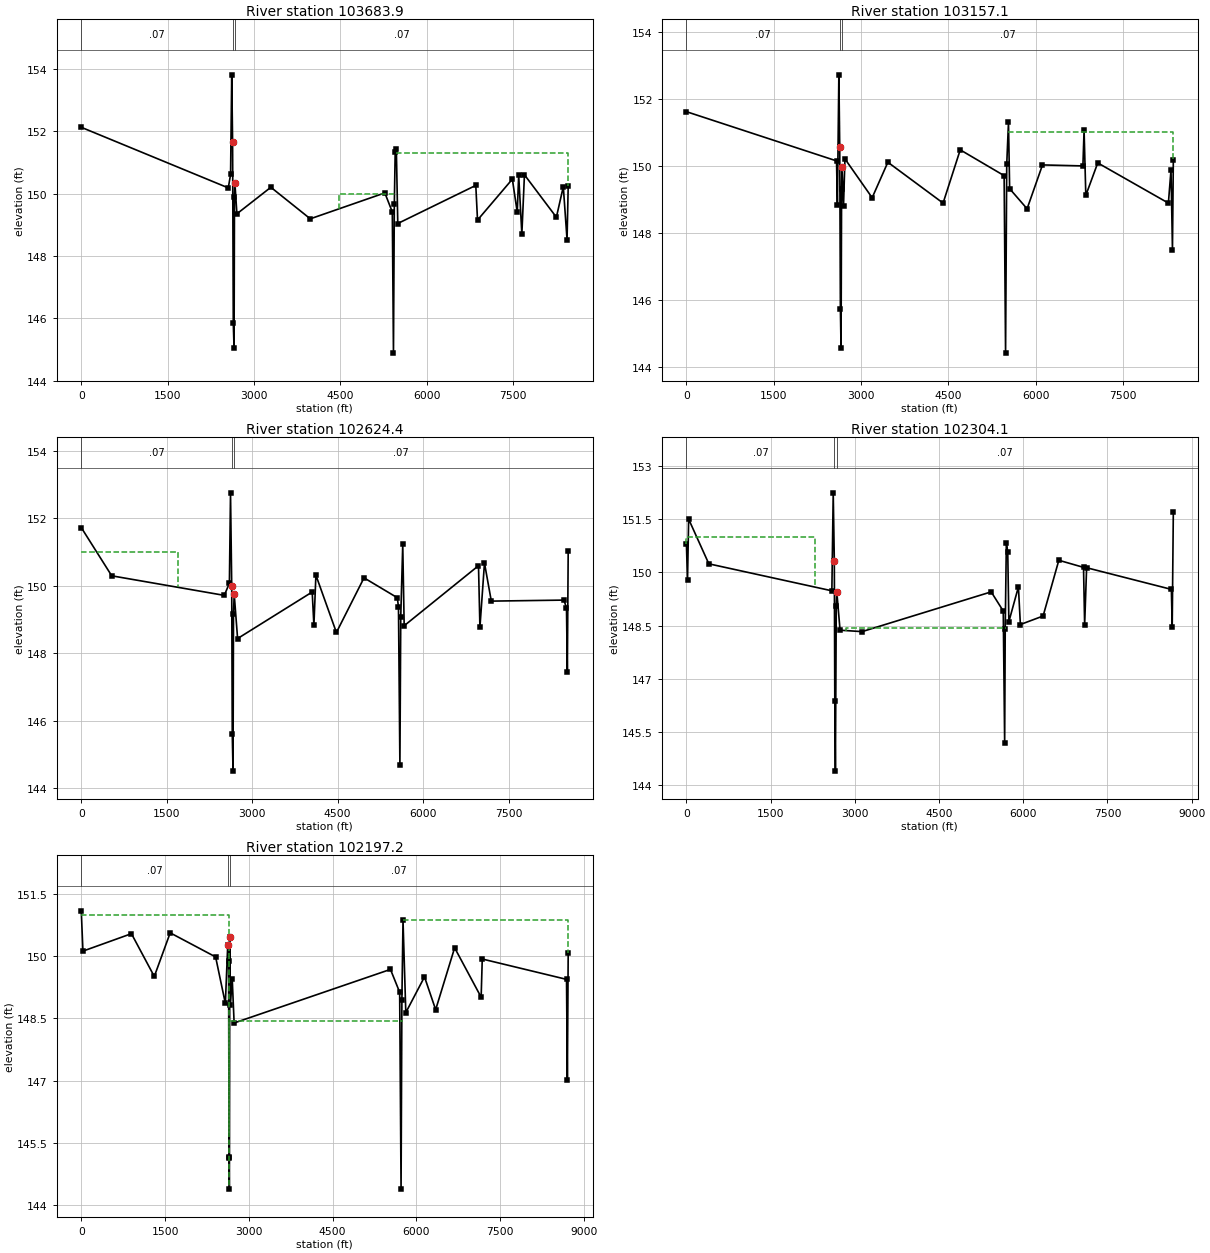
Type RM Length L Ch R = 1 ,103683.9,527.81,526.79,487.89
Node Name=AG
XS GIS Cut Line= 5
2998943.9668598613898689.03481252999145.1600270313896124.3798369
2999149.6199918513895964.88015582998390.8902101113893349.3844026
2997017.7810796913890683.4123724
#Sta/Elev= 30
       0  152.12 2552.55  150.18 2592.48  150.61 2612.42   153.8 2627.38  151.65
 2639.55  145.84 2653.03  145.04 2660.27   149.9 2667.27  150.34 2702.18  149.35
 3291.75   150.2 3976.33  149.19 5270.52  150.02 5400.44  149.41 5420.43  144.89
 5435.42  149.66 5450.41  151.32  5470.4  151.42 5495.39  149.04 6849.87  150.26
 6879.86  149.15 7484.62  150.46 7569.59   149.4 7594.58  150.59 7649.56   148.7
 7694.54   150.6 8249.33  149.24 8369.28  150.22 8434.26  148.52 8454.25  150.23
#Mann= 3 , 0 , 0
       0     .07       0 2627.38     .04       0 2667.27     .07       0
#XS Ineff= 2 ,-1
 4481.01  5470.4     150  5470.4 8454.25   151.3
Permanent Ineff=
       F       F
Bank Sta=2627.38,2667.27
XS Rating Curve= 0 ,0
Exp/Cntr=0.3,0.1

Type RM Length L Ch R = 1 ,103157.1,541.78,532.77,295.32
XS GIS Cut Line= 5
2999546.0617842813898717.16992692999674.5900705313896051.7599034
 2999627.149876713895541.83014892998778.7644343713893364.9542533
2997745.2133518613890712.9615259
#Sta/Elev= 30
       0  151.61 2578.56  150.14 2593.55  148.82 2618.54  152.71 2633.53  150.56
 2644.99  145.71 2656.41  144.56 2665.61  149.29 2672.41  149.97 2698.34  148.78
 2723.21   150.2 3190.63  149.04 3460.21   150.1 4408.72  148.88 4703.26  150.47
 5457.08   149.7 5482.04   144.4 5502.01  150.04 5531.97  151.29 5551.94  149.31
 5851.56  148.71 6116.23  150.02 6810.35  149.99 6830.32  151.06 6860.28  149.11
 7065.02  150.08 8278.47  148.88 8323.41  149.87 8348.38  147.49 8363.35  150.17
#Mann= 3 , 0 , 0
       0     .07       0 2633.53     .04       0 2672.41     .07       0
#XS Ineff= 3 ,-1
       0  340.88  150.99 3715.07 5531.97  148.43 5531.97 8363.35     151
Permanent Ineff=
       F       F       F
Bank Sta=2633.53,2672.41
XS Rating Curve= 0 ,0
Exp/Cntr=0.3,0.1

Type RM Length L Ch R = 1 ,102624.4,315.18,320.3,177.08
XS GIS Cut Line= 5
3000049.6828242813898734.05112673000238.03579402 13897282.102587
3000203.7701145313896171.61005743000208.2199087713896013.0001384
2997821.5750757813890712.9615259
#Sta/Elev= 30
       0  151.72  534.68  150.29 2510.37  149.71 2599.93  150.07 2619.76  152.75
 2640.66  149.99 2650.41  145.59 2663.82   144.5 2671.84  149.16 2684.22  149.75
  2743.8  148.43 4053.25  149.81 4083.24  148.82 4118.23  150.31 4478.08  148.61
 4962.89  150.23 5547.66  149.64 5567.65  149.36 5592.65  144.67 5607.64  149.08
 5642.62  151.22 5667.62  148.81  6972.1  150.59 6997.09  148.76 7077.06  150.67
 7197.01  149.54 8471.51  149.57  8516.5  149.34 8531.49  147.44 8546.48  151.02
#Mann= 3 , 0 , 0
       0     .07       0 2640.66     .04       0 2684.22     .07       0
#XS Ineff= 3 ,-1
       0 1706.63  150.99 3220.86 5642.62  148.43 5642.62 8546.48  150.85
Permanent Ineff=
       F       F       F
Bank Sta=2640.66,2684.22
XS Rating Curve= 0 ,0
Exp/Cntr=0.3,0.1

Type RM Length L Ch R = 1 ,102304.1,133.8,106.87,18.03
XS GIS Cut Line= 6
3000485.7793930313898750.93232653000504.4699724513897372.8799645
3000522.3200023613896218.6499895 3000527.411527613896063.2999065
3000418.9927811913895943.85263892997858.7246077813890713.5629026
#Sta/Elev= 30
       0  150.81   19.97  149.78   39.95   151.5  399.47  150.24 2590.84  149.48
 2615.12  152.24 2634.55  150.33 2643.15  146.37 2653.79   144.4 2669.23  149.06
 2678.27  149.46 2736.86  148.37 3129.21  148.33 5428.55  149.45 5643.49  148.91
 5668.48  145.19 5678.48  148.41 5698.47  150.83 5723.46  150.57 5743.46  148.61
 5913.41  149.59  5948.4  148.53 6353.28  148.77  6633.2  150.34 7073.07  150.14
 7093.07  148.52 7128.06  150.13 8637.62  149.52 8652.62  148.46 8672.61  151.71
#Mann= 3 , 0 , 0
       0     .07       0 2634.55     .04       0 2678.27     .07       0
#XS Ineff= 3 ,-1
       0 2287.76  150.99  2849.3 5698.47  148.43 5698.47 8672.61  150.83
Permanent Ineff=
       F       F       F
Bank Sta=2634.55,2678.27
XS Rating Curve= 0 ,0
Exp/Cntr=0.5,0.3

Type RM Length L Ch R = 1 ,102197.2,101.02,80.73,83.13
BEGIN DESCRIPTION:
Upstream Section - ROAD NORTH OF MCGILL
END DESCRIPTION:
XS GIS Cut Line= 6
3000574.2273788613898749.65411393000655.6524128613896305.3798029
3000632.9729962813896071.64798693000607.0583499413896035.5758806
3000400.2014801913895893.45247722997915.7740343713890718.4195202
#Sta/Elev= 30
       0  151.09   29.95  150.12   898.4  150.54 1307.66  149.51 1592.16  150.56
  2405.7  149.98 2580.07  148.86 2622.84  150.27 2637.96  149.89 2646.22  145.17
 2651.02  144.39  2653.5  145.15 2659.62  150.46 2670.89  148.83 2702.58  149.46
  2737.1  148.39 5536.24  149.68 5701.11  149.13 5726.09  144.39 5741.08  148.95
 5761.06  150.86 5811.02  148.64 6145.76   149.5 6345.61  148.71 6685.34   150.2
 7159.97  149.01 7179.96  149.93 8688.78  149.44 8703.77  147.02 8718.76  150.08
#Mann= 3 ,-1 , 0
       0     .07       0 2622.84     .04       0 2659.62     .07       0
#XS Ineff= 3 ,-1
       0 2650.67  150.99 2654.17 5761.06  148.43 5761.06 8718.76  150.86
Permanent Ineff=
       F       F       F
Bank Sta=2622.84,2659.62
XS Rating Curve= 0 ,0
Exp/Cntr=0.5,0.3