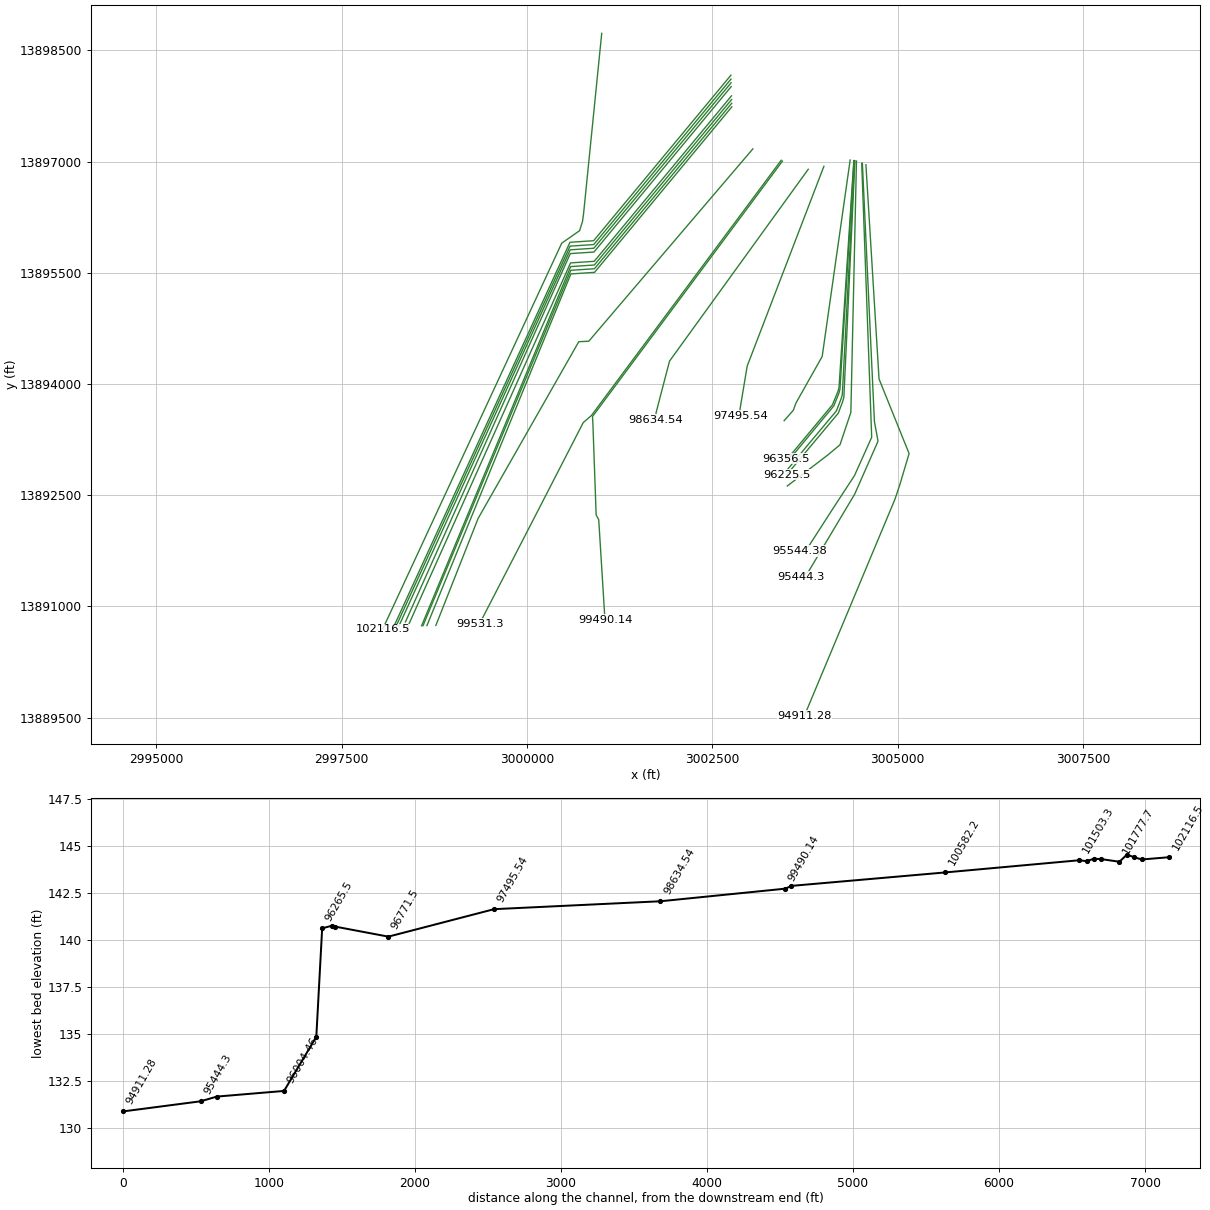
HEC-RAS study U100-00-00.prj: U100-00-00

--- U100-00-00.g01 (geometry) --- (continued)

Type RM Length L Ch R = 2 ,102144.1,,,
BEGIN DESCRIPTION:
ROAD NORTH OF MCGILL
END DESCRIPTION:
Node Name=NORTH OF MCGILL
Bridge Culvert--1,0,-1,-1, 0
Deck Dist Width WeirC Skew NumUp NumDn MinLoCord MaxHiCord MaxSubmerge Is_Ogee
15.5,59,2.6,0, 60, 60, , , 0.98, 0, 0,0,,
       0    9.98   29.95   94.83  284.49  294.47  319.43  339.39  349.38   394.3
  414.26  434.22  459.18  469.16  484.13  529.05  554.01  573.97  593.94  608.91
  618.89  633.87  643.85  658.82  688.77  708.73  738.68  753.65  778.61  788.59
  808.56  828.52  863.46  878.43   893.4  913.37  923.35  948.31  963.28  983.24
 1043.14 1058.11 1137.97 1242.78 1332.62 1427.45 1502.32 1602.14 1711.94 1851.69
 2136.19 2265.95 2340.82 2435.65 2500.34 2585.07 2618.58 2631.71 2678.07 2702.58
   151.6  151.86  151.99   151.9  152.09  152.38  151.99  152.26   152.1  152.33
  152.11  152.22  151.94  152.26  151.97     152  151.68   151.9  151.67  151.86
  151.52  151.43  151.68  151.49  151.78  151.67  151.95  151.66   151.9   151.7
  151.95  151.73  151.77  152.04  151.79  152.06  151.81  152.01  151.83  151.99
  151.71  152.04  151.63  151.69  151.36  151.97  152.18  151.84   151.9  151.43
  151.76  151.53  151.05  151.24  150.99   151.3  151.08  151.38  151.18  150.56
       0       0       0       0       0       0       0       0       0       0
       0       0       0       0       0       0       0       0       0       0
       0       0       0       0       0       0       0       0       0       0
       0       0       0       0       0       0       0       0       0       0
       0       0       0       0       0       0       0       0       0       0
       0       0       0       0       0       0       0       0       0       0
       0    9.98   29.95   94.83  284.49  294.47  319.43  339.39  349.38   394.3
  414.26  434.22  459.18  469.16  484.13  529.05  554.01  573.97  593.94  608.91
  618.89  633.87  643.85  658.82  688.77  708.73  738.68  753.65  778.61  788.59
  808.56  828.52  863.46  878.43   893.4  913.37  923.35  948.31  963.28  983.24
 1043.14 1058.11 1137.97 1242.78 1332.62 1427.45 1502.32 1602.14 1711.94 1851.69
 2136.19 2265.95 2340.82 2435.65 2500.34 2585.07 2618.58 2631.71 2678.07 2702.58
   151.6  151.86  151.99   151.9  152.09  152.38  151.99  152.26   152.1  152.33
  152.11  152.22  151.94  152.26  151.97     152  151.68   151.9  151.67  151.86
  151.52  151.43  151.68  151.49  151.78  151.67  151.95  151.66   151.9   151.7
  151.95  151.73  151.77  152.04  151.79  152.06  151.81  152.01  151.83  151.99
  151.71  152.04  151.63  151.69  151.36  151.97  152.18  151.84   151.9  151.43
  151.76  151.53  151.05  151.24  150.99   151.3  151.08  151.38  151.18  150.56
       0       0       0       0       0       0       0       0       0       0
       0       0       0       0       0       0       0       0       0       0
       0       0       0       0       0       0       0       0       0       0
       0       0       0       0       0       0       0       0       0       0
       0       0       0       0       0       0       0       0       0       0
       0       0       0       0       0       0       0       0       0       0
BR Coef=-1 , 0 , 0 ,, 0 ,,,0.8,-1,,0,
WSPro=,,,, 1 ,,,, 0 ,,,, 0 ,,,,-1 ,-1 ,-1 , 0 , 0 , 0 , 0 , 0
Culvert=1,3.5,,59,0.013,0.5,1,1,3,144.19,2652.42,144.45,2652.42,Culvert #1  , 0 ,15.5
Culvert Bottom n=0.013
BC Design=,, 0 ,, 0 ,,,,,,
BC Use User HTab Curves=0
BC User HTab FreeFlow(D)= 0

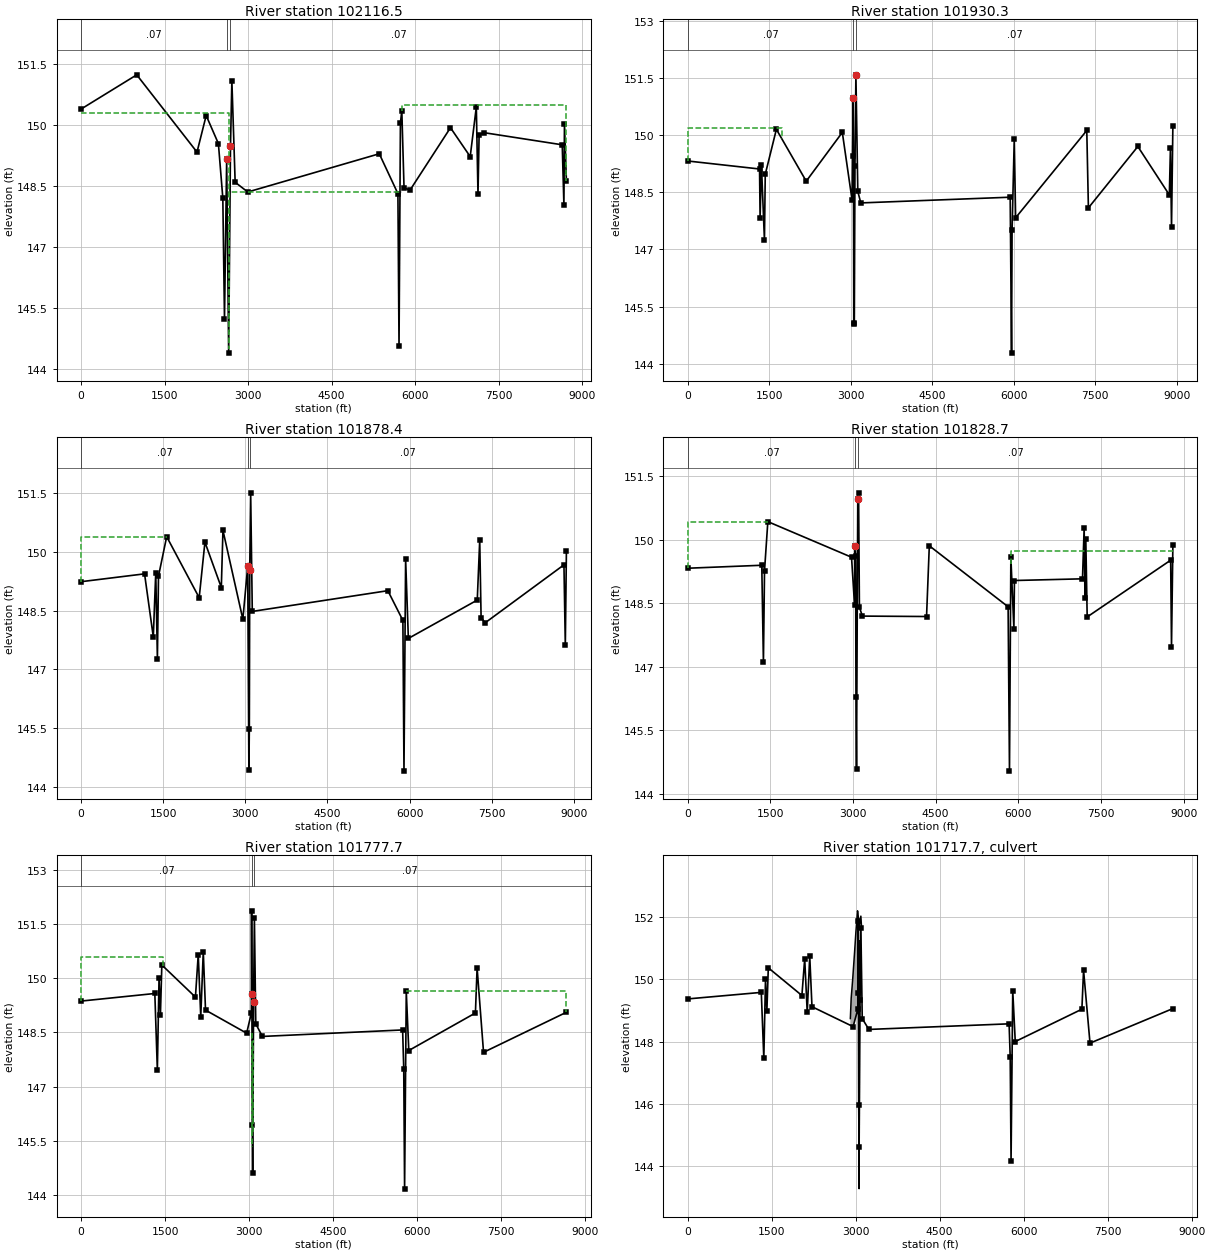
Type RM Length L Ch R = 1 ,102116.5,360.02,186.18,108.23
BEGIN DESCRIPTION:
Downstream Section - ROAD NORTH OF MCGILL
END DESCRIPTION:
XS GIS Cut Line= 6
3001007.4213943613898730.14923163000762.5432751913896296.8099382
3000748.1768341113896193.36132623000708.9328181113896068.1814584
3000467.7902557713895899.4504967 2998051.983735713890692.0298092
#Sta/Elev= 30
       0   150.4  998.22  151.24 2081.28  149.34 2245.99  150.24 2465.52  149.55
  2545.1  148.21 2575.07  145.24 2614.32  149.17 2650.01   144.4 2682.84  149.49
 2707.51   151.1 2766.62   148.6 2993.21  148.36 5356.36   149.3  5691.1  148.32
 5711.08  144.57 5736.06  150.05 5761.05  150.36 5801.01  148.47 5905.93   148.4
 6635.36  149.94 6990.08  149.23    7100  150.45 7129.97   148.3 7149.96  149.76
 7229.89  149.82 8643.79  149.52 8673.76  148.04 8683.76  150.04 8718.73  148.62
#Mann= 3 , 0 , 0
       0     .07       0 2614.32     .04       0 2682.84     .07       0
#XS Ineff= 3 ,-1
       0 2650.67   150.3 2654.17 5761.05  148.36 5761.05 8718.73   150.5
Permanent Ineff=
       F       F       F
Bank Sta=2614.32,2682.84
XS Rating Curve= 0 ,0
Exp/Cntr=0.5,0.3

Type RM Length L Ch R = 1 ,101930.3,36.99,51.84,24.81
XS GIS Cut Line= 4
3002749.8362166113898164.83277693000898.3546833513895932.7896689
3000579.0685765313895911.42980342998201.5529903613890725.0067773
#Sta/Elev= 30
       0  149.32 1322.72  149.11  1332.7  147.83 1357.66  149.21 1412.56  147.24
 1427.54  148.97 1632.18  150.15 2181.24  148.79 2845.09  150.07    3025  148.29
    3045  150.97 3050.03  149.45  3055.8  145.04 3065.85  145.08 3077.76   149.2
    3095  151.58    3130  148.52    3185  148.22 5932.78  148.37 5957.76  144.28
 5967.75  147.51 6007.72   149.9  6032.7  147.83 7341.62  150.12  7371.6  148.09
 8280.86   149.7  8860.4  148.43 8880.39  149.66 8900.37  147.58 8925.35  150.25
#Mann= 3 ,-1 , 0
       0     .07       0    3045     .04       0    3095     .07       0
#XS Ineff= 2 ,-1
       0    1737  150.19 6007.72 8925.35   149.9
Permanent Ineff=
       F       F
Bank Sta=3045,3095
XS Rating Curve= 0 ,0
Exp/Cntr=0.3,0.1

Type RM Length L Ch R = 1 ,101878.4,35.52,49.78,26.29
Node Name=AF
XS GIS Cut Line= 4
3002751.34179103 13898113.0182483000899.8605858513895880.9748119
3000580.5741509513895859.61527452998230.0785238613890725.9677334
#Sta/Elev= 30
       0  149.24    1158  149.44 1317.73  147.83 1362.65  149.47  1392.6  147.27
 1412.56  149.38  1562.3  150.39 2156.28  148.83  2261.1  150.25 2560.58  149.09
 2590.53  150.55 2954.15  148.28 3042.77  149.63 3064.53  144.42 3072.46  145.47
 3079.95  149.55 3096.92  151.51 3126.46  148.48 5603.38  149.01  5878.2  148.25
 5898.18   144.4 5928.16  149.82 5978.13  147.79 7237.27  148.77 7282.24   150.3
 7307.23  148.32 7382.17  148.19 8821.17  149.67 8846.15  147.61 8866.14  150.03
#Mann= 3 , 0 , 0
       0     .07       0 3042.77     .04       0 3079.95     .07       0
#XS Ineff= 2 ,-1
       0  1562.3  150.39 5928.16 8866.14  149.82
Permanent Ineff=
       F       F
Bank Sta=3042.77,3079.95
XS Rating Curve= 0 ,0
Exp/Cntr=0.3,0.1

Type RM Length L Ch R = 1 ,101828.7,35.9,51,33.12
XS GIS Cut Line= 4
3002752.78798236 13898063.2585053000901.3067771913895831.2153969
3000582.0203422813895809.85585962998267.6755615313890727.3584787
#Sta/Elev= 30
       0  149.33    1345   149.4    1375  147.11    1395  149.27    1455  150.43
 2973.84  149.59 3027.99  148.47 3037.84  149.86 3047.79  149.62  3054.2  146.29
 3063.91   144.6 3087.07  150.96 3101.84  151.11 3116.61  148.41 3170.76   148.2
 4334.92  148.19 4384.92  149.86 5814.81  148.42  5839.8  144.54  5864.8  149.59
  5919.8   147.9  5929.8  149.04  7164.7  149.08  7194.7  150.29  7209.7  148.62
  7224.7  150.01 7249.69  148.18 8764.61  149.52 8779.61  147.47 8804.61  149.88
#Mann= 3 , 0 , 0
       0     .07       0 3037.84     .04       0 3087.07     .07       0
#XS Ineff= 2 ,-1
       0    1455  150.43  5869.8 8804.61  149.73
Permanent Ineff=
       F       F
Bank Sta=3037.84,3087.07
XS Rating Curve= 0 ,0
Exp/Cntr=0.5,0.3

Type RM Length L Ch R = 1 ,101777.7,86.37,125.48,57.07
BEGIN DESCRIPTION:
Upstream Section - DIRT ROAD
END DESCRIPTION:
XS GIS Cut Line= 5
3002754.2696066913898012.27796393000902.7884015313895780.2348558
3000739.6821004513895769.32313233000583.5019666113895758.8749904
2998359.6432253613890790.1736418
#Sta/Elev= 30
       0  149.37    1315  149.58    1360  147.46    1390     150    1415  148.99
    1440  150.37 2040.01  149.48 2090.01  150.66 2135.01  148.94 2180.01  150.74
    2220  149.12 2954.48  148.48 3038.75  149.04  3042.4  151.87 3047.96  149.56
 3054.09  145.95 3061.56   144.6 3078.09  149.34 3092.81  151.66 3117.27  148.74
 3234.99  148.39 5739.35  148.57 5759.34  147.49 5774.34  144.16 5804.33  149.64
 5849.32     148 7039.01  149.04    7069  150.29 7183.97  147.95 8663.61  149.06
#Mann= 3 , 0 , 0
       0     .07       0 3047.96     .04       0 3078.09     .07       0
#XS Ineff= 4 ,-1
       0    1455  150.59 3047.96 3057.56  148.48 3065.56 3078.09  148.26
 5804.33 8663.61  149.64
Permanent Ineff=
       F       F       F       F
Bank Sta=3047.96,3078.09
XS Rating Curve= 0 ,0
Exp/Cntr=0.5,0.3

Type RM Length L Ch R = 2 ,101717.7,,,
BEGIN DESCRIPTION:
DIRT ROAD
U00_1900
END DESCRIPTION:
Node Name=DIRT ROAD
Bridge Culvert--1,0,-1,-1, 0
Deck Dist Width WeirC Skew NumUp NumDn MinLoCord MaxHiCord MaxSubmerge Is_Ogee
55,14.5,2.6,0, 10, 10, , , 0.98, 0, 0,0,,
 2904.95 2919.81 2944.58 2979.25 3004.02 3033.74  3048.6 3063.46 3092.81 3107.49
  148.74  149.39  149.95  150.84  151.52   152.2  151.99   151.7  152.03  151.61
       0       0       0       0       0       0       0       0       0       0
 2904.95 2919.81 2944.58 2979.25 3004.02 3033.74  3048.6 3063.46 3092.81 3107.49
  148.74  149.39  149.95  150.84  151.52   152.2  151.99   151.7  152.03  151.61
       0       0       0       0       0       0       0       0       0       0
BR Coef=-1 , 0 , 0 ,, 0 ,,,0.8,-1,,0,
WSPro=,,,, 1 ,,,, 0 ,,,, 0 ,,,,-1 ,-1 ,-1 , 0 , 0 , 0 , 0 , 0
Culvert=1,8,,29.3,0.013,0.5,1,1,3,143.26,3061.56,143.56,3061.56,Culvert #1  , 0 ,48.4
Culvert Bottom n=0.013
BC Design=,, 0 ,, 0 ,,,,,,
BC Use User HTab Curves=0
BC User HTab FreeFlow(D)= 0

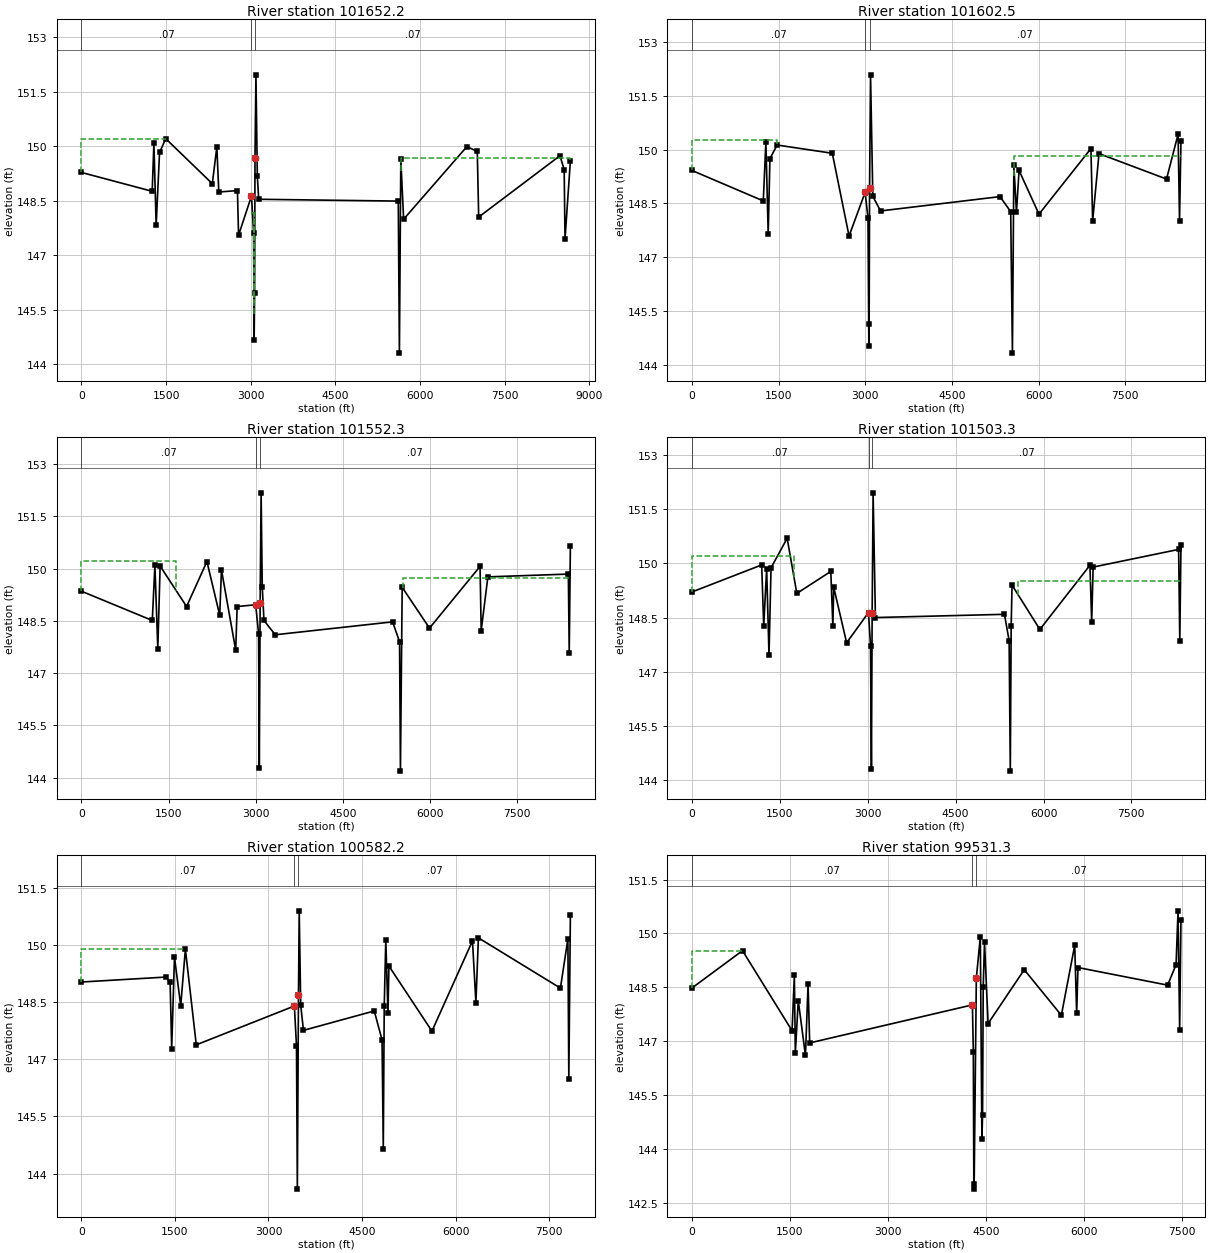
Type RM Length L Ch R = 1 ,101652.2,37.02,49.73,57.65
BEGIN DESCRIPTION:
Downstream Section - DIRT ROAD
END DESCRIPTION:
XS GIS Cut Line= 5
3002757.9149406113897886.85170563000906.4337354513895654.8085975
3000743.3274343613895643.89687393000587.1473005313895633.4487321
2998363.2885592713890664.7473834
#Sta/Elev= 30
       0  149.28    1255  148.76    1285  150.09    1325  147.82    1385  149.83
    1495  150.21    2320  148.97    2400  149.98    2435  148.74    2765  148.78
    2785  147.55 3013.93  148.63 3051.15  147.62 3060.93  144.65 3069.22  145.97
 3076.05  149.69 3092.81  151.97 3117.27  149.18 3141.73  148.54 5614.38  148.49
 5634.37   144.3 5659.37  149.64 5709.35  147.99 6829.06  149.99 7014.01  149.86
 7039.01  148.05 8478.65  149.74 8553.63  149.36 8568.63  147.45 8663.61   149.6
#Mann= 3 , 0 , 0
       0     .07       0 3013.93     .04       0 3076.05     .07       0
#XS Ineff= 4 ,-1
       0    1495  150.21 3013.93 3057.56  148.16 3065.56 3076.05  148.16
 5669.36 8663.61  149.67
Permanent Ineff=
       F       F       F       F
Bank Sta=3013.93,3076.05
XS Rating Curve= 0 ,0
Exp/Cntr=0.5,0.3

Type RM Length L Ch R = 1 ,101602.5,37.36,50.18,20.44
XS GIS Cut Line= 4
3002759.3594915313897837.13986283000907.8782863613895605.0967547
3000588.5918514413895583.73721742998577.4406900313890737.9437594
#Sta/Elev= 30
       0  149.42    1235  148.57    1280  150.22    1320  147.65    1350  149.75
    1475  150.13    2430   149.9    2720  147.59 2998.46  148.81 3047.69  148.09
 3062.61  144.53 3068.07  145.13    3075  148.92 3091.99  152.09 3131.38   148.7
 3264.97  148.29 5333.59  148.69 5518.46  148.27 5548.44  144.32 5573.42  149.56
 5618.39  148.25 5663.36  149.42 6008.13   148.2 6907.52  150.03  6937.5  148.01
 7047.42  149.89 8216.63  149.18  8416.5  150.43 8441.49  148.01 8466.47  150.23
#Mann= 3 , 0 , 0
       0     .07       0 2998.46     .04       0    3075     .07       0
#XS Ineff= 2 ,-1
       0    1475  150.27 5583.42 8466.47  149.83
Permanent Ineff=
       F       F
Bank Sta=2998.46,3075
XS Rating Curve= 0 ,0
Exp/Cntr=0.3,0.1

Type RM Length L Ch R = 1 ,101552.3,36.62,48.97,27.34
XS GIS Cut Line= 4
3002760.8174938613897786.96935943000909.3362886913895554.9262514
3000590.04985377 13895533.5667142998595.97313328 13890739.095988
#Sta/Elev= 30
       0  149.35    1220  148.51    1265  150.09    1315   147.7    1355  150.07
 1810.01  148.91 2160.01   150.2    2380  148.66    2410  149.96    2655  147.66
    2680  148.91 2998.46  148.96 3048.86  148.13 3060.78  144.27 3075.64     149
 3091.99  152.17 3111.69  149.48 3141.23  148.51 3334.94   148.1    5354  148.47
 5473.94   147.9 5488.93  144.19 5518.92  149.46 5988.69  148.29 6858.27  150.06
 6878.26  148.22  6993.2  149.76 8377.55  149.84 8392.54  147.59 8412.53  150.64
#Mann= 3 , 0 , 0
       0     .07       0 2998.46     .04       0 3075.64     .07       0
#XS Ineff= 2 ,-1
       0    1635  150.21 5528.91 8412.53  149.72
Permanent Ineff=
       F       F
Bank Sta=2998.46,3075.64
XS Rating Curve= 0 ,0
Exp/Cntr=0.3,0.1

Type RM Length L Ch R = 1 ,101503.3,747.48,921.12,413.23
XS GIS Cut Line= 4
3002762.2403912813897738.0081713 3000910.759186113895505.9650632
 3000591.472751213895484.60519782998649.3437614413890740.6005782
#Sta/Elev= 30
       0  149.21    1190  149.96    1225  148.26    1275  149.86    1315  147.46
    1350  149.88    1625   150.7 1790.01  149.17    2370  149.78    2405  148.26
    2420  149.34    2640   147.8 3013.23  148.64 3047.69  147.72 3063.02  144.31
  3075.6  148.64 3091.99  151.96 3131.38   148.5 5333.41  148.59 5413.35  147.86
 5433.33  144.24 5448.32  148.26 5463.31   149.4 5937.95  148.17 6792.31  149.95
 6822.29  148.38 6847.27   149.9 8306.17  150.39 8326.16  147.85 8346.14  150.51
#Mann= 3 , 0 , 0
       0     .07       0 3013.23     .04       0  3075.6     .07       0
#XS Ineff= 2 ,-1
       0    1745  150.21 5568.23 8346.14  149.51
Permanent Ineff=
       F       F
Bank Sta=3013.23,3075.6
XS Rating Curve= 0 ,0
Exp/Cntr=0.3,0.1

Type RM Length L Ch R = 1 ,100582.2,665.75,1050.88,808.34
XS GIS Cut Line= 5
3003046.2234191113897171.74978943000833.1799449513894577.2700702
3000697.7901238713894570.29993982999339.4624599413892185.3909957
2998770.3907634513890744.0680909
#Sta/Elev= 30
       0  149.03 1353.06  149.16 1422.96  149.03 1447.93  147.28 1492.86  149.68
 1592.72  148.41 1667.61  149.89 1842.37  147.38 3414.94   148.4 3448.84  147.35
 3462.55  143.59 3480.84   148.7 3492.41   150.9 3516.62  148.42 3560.67  147.76
 4695.53  148.27 4820.51  147.51 4840.51  144.65 4855.51  148.39 4880.51  150.14
  4915.5  148.22  4930.5  149.45 5620.42  147.74 6270.35  150.11 6325.34  148.49
 6365.33  150.19 7680.01  148.87 7799.98  150.16 7814.97  146.48 7839.97   150.8
#Mann= 3 , 0 , 0
       0     .07       0 3414.94     .04       0 3480.84     .07       0
#XS Ineff= 2 ,-1
       0 1667.61  149.89 4880.51 7839.97  150.14
Permanent Ineff=
       F       F
Bank Sta=3414.94,3480.84
XS Rating Curve= 0 ,0
Exp/Cntr=0.3,0.1

Type RM Length L Ch R = 1 ,99531.3 ,22.18,41.16,78.09
BEGIN DESCRIPTION:
Channel data copied from RS 99490.14 to avoid lateral channel
END DESCRIPTION:
XS GIS Cut Line= 5
3003428.9195041113897018.20678943000868.0601245313893574.4699104
3000758.0701870313893479.47895873000103.3513521113892206.2242873
2999358.9145207713890764.4361604
#Sta/Elev= 30
       0  148.48  774.38  149.52 1533.77  147.29 1568.74  148.83 1583.72  146.67
 1628.69  148.13  1738.6   146.6 1778.57  148.58 1803.55  146.95 4296.36  148.01
 4310.47 146.687    4318 143.007  4322.5 142.877 4356.49 148.757 4417.47   149.9
 4441.83  144.26 4451.81  144.95 4461.79   148.5 4481.74  149.75 4536.61  147.49
 5090.34  148.99 5659.03  147.72 5863.56  149.67 5893.51  147.77 5913.48  149.05
 7286.46  148.56 7416.26  149.13 7446.22  150.63 7471.18  147.31 7491.15  150.37
#Mann= 3 , 0 , 0
       0     .07       0 4296.36     .04       0 4356.49     .07       0
#XS Ineff= 2 ,-1
       0  774.38  149.52 5863.56 7491.15  149.67
Permanent Ineff=
       F       F
Bank Sta=4296.36,4356.49
XS Rating Curve= 0 ,0
Exp/Cntr=0.3,0.1

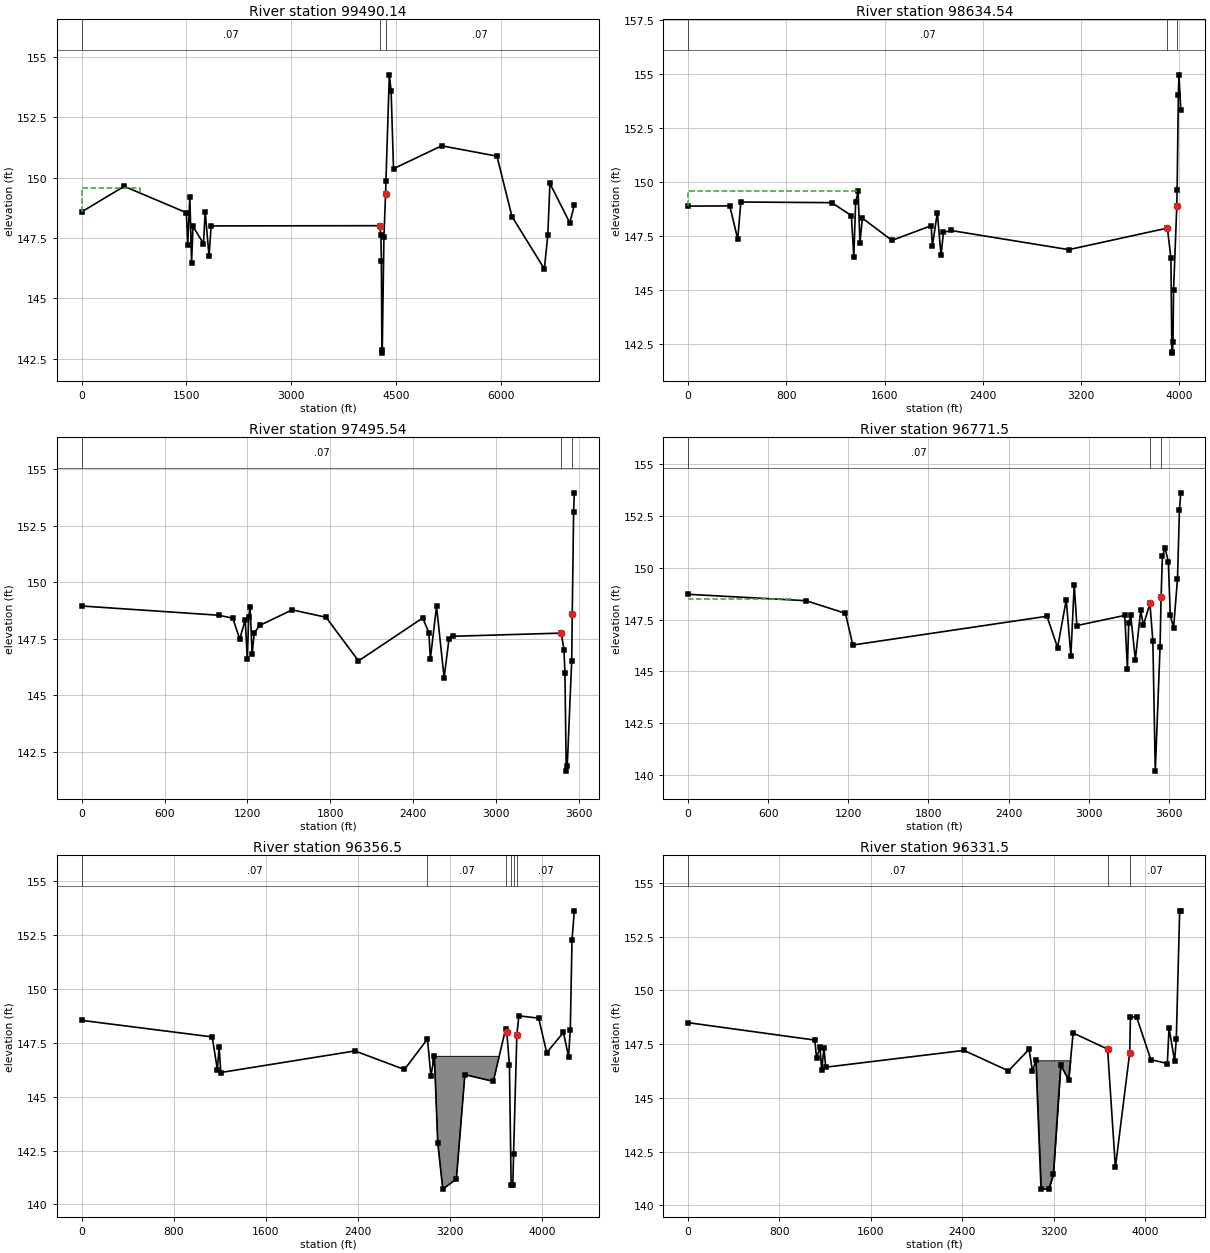
Type RM Length L Ch R = 1 ,99490.14,389.02,855.6,849.62
XS GIS Cut Line= 6
3003444.96835652  13897006.272433000882.7969716913893560.7707908
3000887.7329854413893480.19385233000932.2483163613892233.3101912
3000967.0195722713892168.90907333001051.3448629413890815.4865833
#Sta/Elev= 30
       0  148.58  609.82  149.64 1499.56  148.55 1519.56  147.23 1549.55  149.18
 1574.54  146.47 1594.54  147.98 1744.49  147.27 1769.48  148.58 1824.47  146.74
 1854.46     148 4268.76  148.01 4283.76  147.61 4290.47  146.54    4298  142.86
  4302.5  142.73    4327  147.55 4350.74  149.34 4355.49  149.85 4404.43  154.26
 4429.38  153.61 4464.32  150.37 5153.04  151.32 5944.63  150.89 6159.01  148.39
 6622.66  146.22 6672.52  147.63 6702.43  149.76  6986.6  148.13 7051.42  148.86
#Mann= 3 ,-1 , 0
       0     .07       0 4268.76     .04       0 4355.49     .07       0
#XS Ineff= 1 ,-1
       0  829.76  149.56
Permanent Ineff=
       F
#Block Obstruct= 2 , 0
       0                 4464.32       0  150.37
Bank Sta=4268.76,4350.74
XS Rating Curve= 0 ,0
Exp/Cntr=0.3,0.1

Type RM Length L Ch R = 1 ,98634.54,1013.93,1139,1156.61
Node Name=AE
XS GIS Cut Line= 4
 3003793.5998771 13896896.6466653001921.9992896213894308.4969857
3001742.0898725213893618.37008513001730.8198819513893515.0300687
#Sta/Elev= 30
       0  148.88  339.89  148.89  404.87  147.34  429.86  149.07 1169.62  149.04
 1329.57  148.44 1349.56  146.53 1364.56  149.07 1384.55  149.56 1399.55  147.18
 1419.54  148.32 1659.46  147.29 1979.36  147.97 1989.35  147.04 2029.34  148.58
 2059.33   146.6 2079.32  147.66  2139.3  147.75 3098.99  146.86 3902.16  147.86
  3930.7  146.48 3938.36  142.12 3942.94  142.06 3947.67  142.57 3952.34  144.99
 3978.61  148.88  3981.4  149.64  3991.3  154.02 3996.25  154.97  4011.1  153.36
#Mann= 3 ,-1 , 0
       0     .07       0 3902.16     .04       0  3981.4     .07       0
#XS Ineff= 1 ,-1
       0 1384.55  149.56
Permanent Ineff=
       F
Bank Sta=3902.16,3978.61
XS Rating Curve= 0 ,0
Exp/Cntr=0.3,0.1

Type RM Length L Ch R = 1 ,97495.54,914.46,724.04,697.53
XS GIS Cut Line= 4
3004004.6119222813896936.55570593002969.7547400313894241.7103738
3002873.2998804513893662.91002233002879.1400918713893573.2300835
#Sta/Elev= 30
       0  148.95  993.87  148.54 1093.75  148.41  1143.7  147.49 1183.65  148.33
 1198.63   146.6 1208.62  148.45 1218.61  148.91 1233.59  146.82 1248.58  147.76
 1288.53  148.09 1523.26  148.78 1767.98  148.45 2002.71  146.52 2467.18  148.42
 2512.13  147.76 2522.12   146.6 2567.07  148.93 2622.01  145.77 2656.97  147.49
 2686.93  147.61 3468.52  147.75 3488.47  147.02 3495.43     146 3504.98  141.64
  3512.2  141.85 3544.61  146.53 3548.53   148.6 3558.37  153.11 3563.37  153.96
#Mann= 3 ,-1 , 0
       0     .07       0 3468.52     .04       0 3548.53     .07       0
#XS Ineff= 1 ,-1
       0 1218.61  148.91
Permanent Ineff=
       F
Bank Sta=3468.52,3548.53
XS Rating Curve= 0 ,0
Exp/Cntr=0.3,0.1

Type RM Length L Ch R = 1 ,96771.5 ,329.29,362.48,360.57
XS GIS Cut Line= 5
3004358.7975656113897021.56012913003981.40002644 13894371.009984
3003627.2199605313893742.33998153003591.8000838613893644.9399139
 3003468.216669613893505.1915057
#Sta/Elev= 30
       0  148.72   884.1  148.41  1178.8   147.8 1233.75  146.27 2687.24  147.66
 2766.86  146.15 2831.55  148.45 2866.39  145.76 2891.27  149.19 2911.18  147.21
 3269.47   147.7 3289.38  145.13 3299.33  147.34 3314.26   147.7  3349.1  145.56
 3388.91  147.95 3408.73  147.22 3458.08  148.28    3480  146.46 3498.29  140.18
 3533.97  146.18 3541.78  148.61 3551.59  150.55 3571.23  150.96 3595.78   150.3
 3610.51  147.71 3635.06  147.09 3664.51  149.48 3679.24  152.81 3689.06  153.62
#Mann= 3 ,-1 , 0
       0     .07       0 3458.08     .04       0 3541.78     .07       0
#XS Ineff= 1 ,-1
       0  779.21   148.5
Permanent Ineff=
       F
Bank Sta=3458.08,3541.78
XS Rating Curve= 0 ,0
Exp/Cntr=0.3,0.1

Type RM Length L Ch R = 1 ,96356.5 ,22.07,25,25.87
BEGIN DESCRIPTION:
Updated (March 2016)
END DESCRIPTION:
XS GIS Cut Line= 6
     3004408.113     13897013.34     3004208.497     13893952.59
     3004194.866     13893900.97     3004119.841     13893719.31
     3003578.938     13893069.89     3003493.052     13892994.15
#Sta/Elev= 30
       0  148.54 1133.98  147.77 1178.94  146.25 1193.93  147.32 1208.92  146.12
 2372.88  147.12 2802.49  146.26 3002.31  147.67 3032.29  145.96 3062.26  146.88
 3091.52  142.87 3135.39  140.71 3253.31  141.18 3327.16  146.02 3573.93  145.71
 3680.82  148.15 3691.15  147.98 3713.82  146.45 3728.57   140.9 3743.33  140.92
 3749.68  142.35 3778.18  147.87  3795.8  148.75 3967.51  148.64 4037.46  147.04
 4182.29  147.98  4227.1  146.86 4242.03  148.11 4256.97  152.26 4276.89  153.62
#Mann= 6 ,-1 , 0
       0     .07       0 3002.31     .07       0 3680.82     .04       0
 3728.57    .035       0 3749.68     .04       0 3778.18     .07       0
#XS Ineff= 1 ,-1
    3968    4276   148.6
Permanent Ineff=
       F
#Block Obstruct= 1 ,-1
 3047.27 3638.69  146.87
Bank Sta=3691.15,3778.18
XS Rating Curve= 0 ,0
Exp/Cntr=0.3,0.1

Type RM Length L Ch R = 1 ,96331.5 ,58.27,66,68.31
BEGIN DESCRIPTION:
Updated (March 2016)
END DESCRIPTION:
XS GIS Cut Line= 6
     3004410.884     13897012.88     3004220.632     13893925.75
     3004206.597     13893873.78     3004137.778     13893704.37
     3003624.707      13893085.5     3003494.448     13892965.44
#Sta/Elev= 30
       0   148.5 1109.43  147.69 1124.42  146.85 1154.41  147.37  1169.4  146.28
 1189.39  147.33 1204.38  146.43 2413.75  147.21 2803.55  146.26 2983.46  147.26
 3013.44  146.25 3043.43  146.75 3088.19  140.77 3156.71  140.76 3196.27  141.45
 3260.56  146.52 3329.79  145.84 3369.35  148.02 3670.59  147.27 3738.85  141.77
 3864.25  147.11 3870.43  148.77 3925.05  148.75 4049.19  146.78 4193.35   146.6
 4208.05  148.25 4257.02  146.71 4271.72  147.76 4301.11  153.68  4310.9   153.7
#Mann= 3 ,-1 , 0
       0     .07       0 3670.59    .015       0 3864.25     .07       0
#XS Ineff= 1 ,-1
    3924    4310   148.7
Permanent Ineff=
       F
#Block Obstruct= 1 ,-1
 3043.43 3354.51  146.75
Bank Sta=3670.59,3864.25
XS Rating Curve= 0 ,0
Exp/Cntr=0.3,0.1

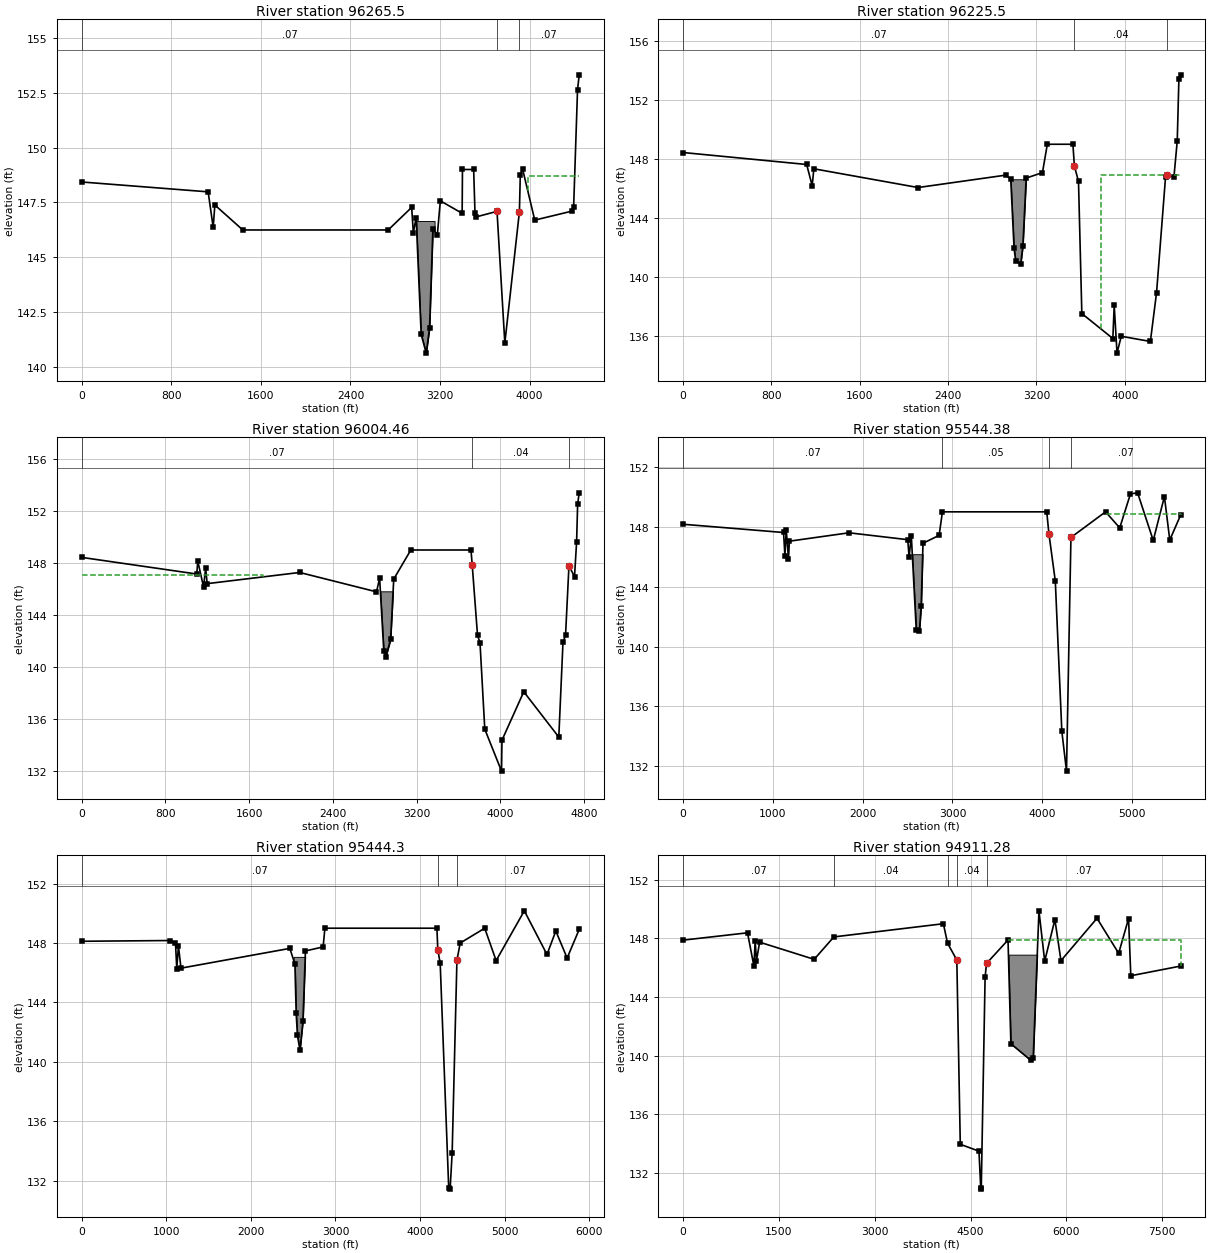
Type RM Length L Ch R = 1 ,96265.5 ,35.31,40,41.4
BEGIN DESCRIPTION:
Updated (March 2016)
END DESCRIPTION:
XS GIS Cut Line= 6
     3004418.198     13897011.66     3004252.629     13893854.79
     3004237.528     13893801.89     3004173.715     13893637.84
     3003776.278     13893163.83     3003500.853     13892831.25
#Sta/Elev= 30
       0  148.43 1128.57  147.98 1173.51  146.36 1188.49  147.38 1438.18  146.24
 2736.53  146.24 2946.27  147.27 2961.25  146.12 2986.22   146.8 3031.16  141.48
  3076.1  140.62 3106.07  141.76 3136.03   146.3    3175  145.99 3202.51  147.57
 3397.19     147    3400     149    3500     149    3512     147 3524.95  146.84
 3708.62  147.09 3778.38  141.08 3908.57  147.07 3916.67  148.77  3936.5  149.03
 4045.62  146.69 4378.17   147.1 4393.06   147.3  4427.8  152.64 4442.69  153.32
#Mann= 3 ,-1 , 0
       0     .07       0 3708.62    .015       0 3908.57     .07       0
#XS Ineff= 2 ,-1
       0    1128   147.9    3983    4442   148.7
Permanent Ineff=
       F       F
#Block Obstruct= 1 ,-1
 2986.22 3151.01  146.65
Bank Sta=3708.62,3908.57
XS Rating Curve= 0 ,0
Exp/Cntr=0.3,0.1

Type RM Length L Ch R = 1 ,96225.5 ,195.14,221.04,228.76
BEGIN DESCRIPTION:
Updated (March 2016)
END DESCRIPTION:
XS GIS Cut Line= 6
     3004422.631     13897010.92     3004273.875      13893822.8
     3004271.966     13893811.62     3004256.219     13893758.16
     3004198.528     13893605.94     3003503.042     13892775.55
#Sta/Elev= 30
       0  148.44  1118.8  147.63 1168.75  146.19 1183.73  147.34 2127.72  146.07
 2921.88  146.91 2966.83  146.63  2996.8  141.96 3011.78  141.09 3056.73  140.88
 3076.71  142.11 3106.68  146.71 3254.02  147.08 3298.13     149    3530     149
 3543.09  147.53 3580.51  146.48 3610.74  137.54 3891.49  135.85 3903.82  138.09
  3929.3  134.86 3967.72     136 4231.44  135.65 4287.34  138.95 4369.03  146.81
 4385.24  146.92 4444.73  146.78 4474.68  149.22 4489.65  153.39 4504.63   153.7
#Mann= 3 ,-1 , 0
       0     .07       0 3543.09     .04       0 4385.24     .07       0
#XS Ineff= 2 , 0
       0                    3787       0  146.92
Permanent Ineff=
       F       F
#Block Obstruct= 1 ,-1
 2966.83 3106.68  146.63
Bank Sta=3543.09,4385.24
XS Rating Curve= 0 ,0
Exp/Cntr=0.3,0.1

Type RM Length L Ch R = 1 ,96004.46,649.07,460.08,554.16
BEGIN DESCRIPTION:
Updated (March 2016)
END DESCRIPTION:
Node Name=AD
XS GIS Cut Line= 5
3004443.8023168613897007.39283463004368.1617201113893616.8960067
 3004221.430058213893179.41984753004060.5901567813893044.9001034
3003511.0253110213892624.3222044
#Sta/Elev= 30
       0  148.43 1098.81  147.15  1108.8  148.14 1163.74  146.16 1183.72  147.59
 1198.71  146.41 2082.75  147.27 2816.95  145.78 2846.92  146.82 2886.88  141.19
 2906.85   140.8 2951.81  142.12 2981.77  146.76    3145     149    3720     149
 3731.89  147.84 3782.74  142.42 3806.22  141.87 3851.96  135.21 4012.02  131.98
 4016.25  134.36 4224.62  138.09 4559.47   134.6 4599.39  141.89 4623.92  142.44
 4656.49  147.78 4709.68  146.95 4729.59  149.61 4739.55  152.54 4754.48   153.4
#Mann= 3 ,-1 , 0
       0     .07       0 3731.89     .04       0 4656.49     .07       0
#XS Ineff= 1 ,-1
       0 1733.13  147.09
Permanent Ineff=
       F
#Block Obstruct= 1 ,-1
 2846.92 2981.77  145.82
Bank Sta=3731.89,4656.49
XS Rating Curve= 0 ,0
Exp/Cntr=0.3,0.1

Type RM Length L Ch R = 1 ,95544.38,125.59,110.94,131.34
BEGIN DESCRIPTION:
Updated (March 2016)
END DESCRIPTION:
XS GIS Cut Line= 6
3004514.6394455313896979.05791753004649.2300556213893281.3579638
3004417.3699550313892764.37015273004134.6999166913892332.0501512
3003795.4991515313891804.88946013003679.4367196113891746.3557845
#Sta/Elev= 30
       0  148.17 1118.53  147.62 1133.51  146.08  1148.5  147.78 1173.46  145.88
 1183.45  147.04 1847.57   147.6 2501.71  147.14 2516.69  145.98 2541.66  147.39
 2596.58  141.12 2631.54  141.02 2651.51  142.72 2671.48   146.9 2851.25  147.43
    2888     149    4050     149 4073.81  147.55 4145.28  144.37 4217.89  134.34
 4269.99  131.68 4319.35  147.29    4705     149 4862.85  147.93 4982.26   150.2
 5061.86  150.27 5235.99  147.09 5360.37  150.02 5420.12  147.12 5540.11  148.77
#Mann= 4 ,-1 , 0
       0     .07       0    2888     .05       0 4073.81     .04       0
 4319.35     .07       0
#XS Ineff= 3 ,-1
       0 1847.57   147.6                         4708.75 5540.11  148.83
Permanent Ineff=
       F       F       F
#Block Obstruct= 1 ,-1
 2541.66 2686.46  146.17
Bank Sta=4073.81,4319.35
XS Rating Curve= 0 ,0
Exp/Cntr=0.3,0.1

Type RM Length L Ch R = 1 ,95444.3 ,648.25,533.1,582.79
BEGIN DESCRIPTION:
Updated (March 2016)
END DESCRIPTION:
XS GIS Cut Line= 6
     3004523.591      13896975.7     3004686.167      13893492.6
     3004734.683     13893228.28     3004419.891     13892513.88
     3003798.269     13891471.72       3003689.4      13891395.8
#Sta/Elev= 30
       0  148.12 1048.36  148.17 1108.26  147.98 1123.24  146.28 1143.21  147.79
 1173.16  146.31  2460.6  147.64 2520.39  146.58 2535.34  143.27 2550.29  141.78
 2580.18  140.79 2615.06  142.72 2644.95  147.47 2854.21  147.74    2875     149
    4200     149 4210.12  147.56  4238.6  146.64  4339.2  131.53 4355.69  131.43
 4379.89  133.84 4436.55  146.84    4475     148    4765     149 4900.13  146.82
 5233.46  150.17 5501.59  147.23 5605.86  148.81 5739.92  146.99 5882.58  148.92
#Mann= 3 ,-1 , 0
       0     .07       0 4210.12     .04       0 4436.55     .07       0
#Block Obstruct= 1 ,-1
 2505.44 2692.83  147.07
Bank Sta=4210.12,4436.55
XS Rating Curve= 0 ,0
Exp/Cntr=0.3,0.1

Type RM Length L Ch R = 1 ,94911.28,396.93,394.92,443.22
BEGIN DESCRIPTION:
Updated (March 2016)
END DESCRIPTION:
XS GIS Cut Line= 6
3004571.3089516213896957.80664773004748.4021013513894067.6506826
 3005153.770713213893061.54606753005029.2899910213892642.9199363
3004962.2701119513892443.08011293003742.5143493613889526.9885041
#Sta/Elev= 30
       0  147.88 1008.46  148.38 1108.31   146.1 1128.28  147.84 1148.25  146.49
 1198.17  147.74 2051.87  146.57    2360   148.1    4075     149 4140.41  147.67
 4285.58  146.52 4339.78  133.95 4632.17  133.48 4660.84  130.89 4668.41  130.97
 4728.27  145.35  4750.5  146.29  5087.2  147.89 5132.14  140.81 5446.73  139.67
 5481.69  139.84 5571.57  149.88 5661.45  146.45 5821.24  149.28 5916.12  146.48
 6480.38  149.37 6819.94  146.98 6974.74  149.35 7009.69  145.45 7788.68  146.11
#Mann= 5 ,-1 , 0
       0     .07       0    2360     .04       0 4140.41     .07       0
 4285.58     .04       0  4750.5     .07       0
#XS Ineff= 2 ,-1
       0 2331.44  147.46  5087.2 7788.68  147.89
Permanent Ineff=
       F       F
#Block Obstruct= 2 ,-1
 2391.35 2521.15   146.3  5087.2  5546.6  146.89
Bank Sta=4285.58,4750.5
XS Rating Curve= 0 ,0
Exp/Cntr=0.3,0.1