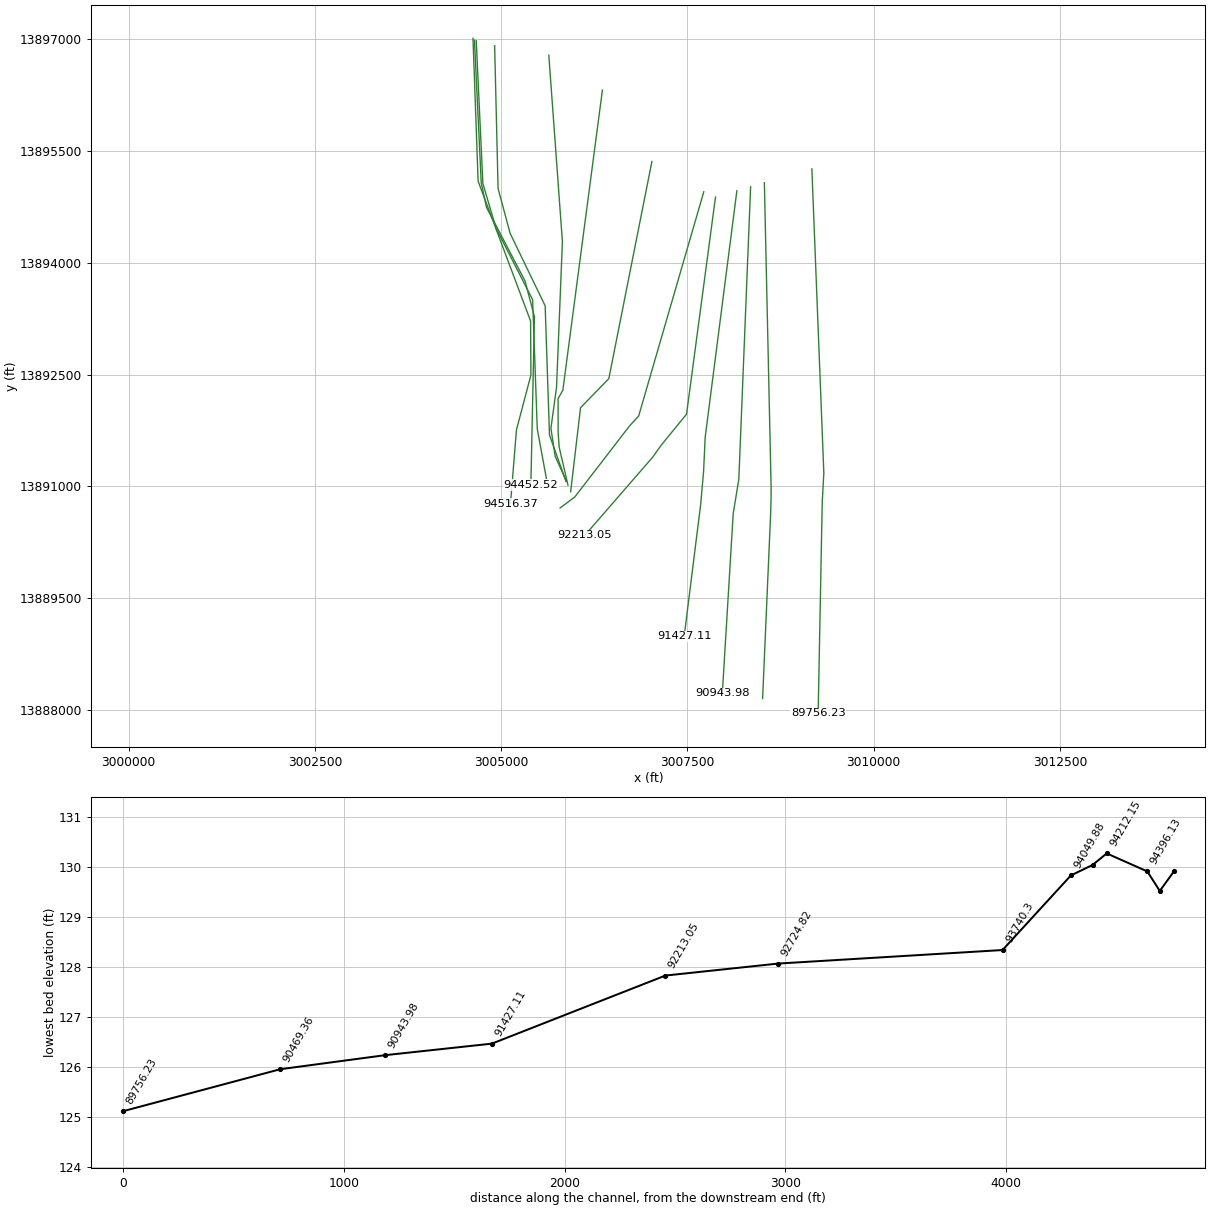
HEC-RAS study U100-00-00.prj: U100-00-00

--- U100-00-00.g01 (geometry) --- (continued)

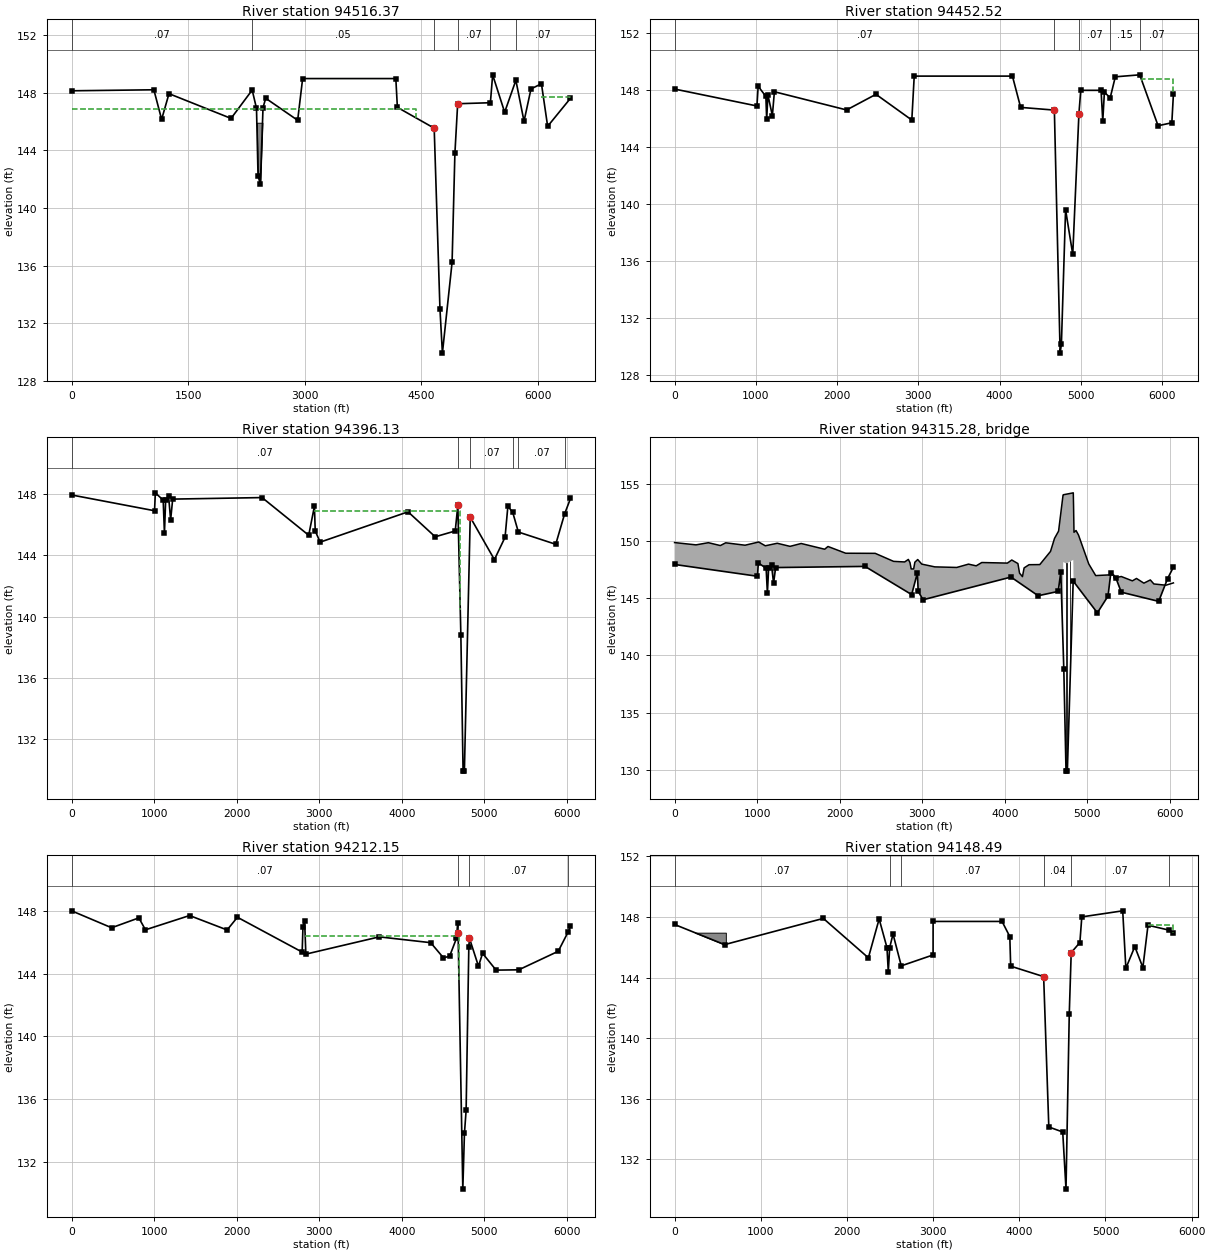
Type RM Length L Ch R = 1 ,94516.37,62.9,63.84,107.48
BEGIN DESCRIPTION:
Updated (March 2016)
END DESCRIPTION:
XS GIS Cut Line= 6
3004621.5142317713897013.08114343004690.2857477813895095.8162772
3005394.6721342813893218.14713233005398.8401049413892493.1249603
3005204.6000078613891756.87938553005125.2418988613890767.5965872
#Sta/Elev= 30
       0  148.15 1059.17  148.22 1159.09  146.16 1254.02  147.95 2053.06  146.23
 2325.28   148.2 2380.86  146.93 2400.62  142.25 2430.26  141.65 2464.84  146.98
 2499.42  147.63 2910.93   146.1    2975     149    4175     149    4195     147
 4669.07  145.55 4743.26  132.99 4774.81  129.91 4899.43  136.22 4935.66  143.79
 4971.41  147.25 5392.87  147.32 5421.88  149.26 5576.43  146.66 5720.93  148.88
  5825.8  146.03 5915.57  148.28 6050.23  148.64 6130.02  145.68 6424.27  147.63
#Mann= 6 ,-1 , 0
       0     .07       0 2325.28     .05       0 4669.07     .04       0
 4971.41     .07       0 5392.87     .15       0 5720.93     .07       0
#XS Ineff= 3 ,-1
       0 4436.07  146.88 5110.99 6050.23  146.73 6050.23 6424.27  147.74
Permanent Ineff=
       F       F       F
#Block Obstruct= 1 ,-1
 2380.86 2464.84  145.93
Bank Sta=4669.07,4971.41
XS Rating Curve= 0 ,0
Exp/Cntr=0.3,0.1

Type RM Length L Ch R = 1 ,94452.52,51.42,56.4,96
BEGIN DESCRIPTION:
Updated (March 2016)
END DESCRIPTION:
XS GIS Cut Line= 6
3004641.1250849413896989.12515463004732.1249029513895073.1250496
3004802.1250910313894746.12504743005320.1250392813893756.1250589
3005446.1251153613893277.12503273005398.17836086 13891017.241101
#Sta/Elev= 30
       0  148.09 1014.03   146.9 1029.01  148.29 1123.92  147.57 1133.91  145.95
  1148.9  147.68 1203.85  146.22 1228.82   147.9 2117.81  146.62 2479.17  147.72
  2920.5  145.91    2950     149    4159     149    4260   146.8 4675.21  146.61
  4746.2  129.52 4761.75  130.15 4813.17  139.61 4901.51  136.46 4977.52  146.36
    5000     148    5250     148 5271.09  145.86 5291.04  147.86 5362.69  147.48
 5425.44  148.95 5726.19  149.09 5952.06  145.51 6121.16  145.72 6141.06  147.77
#Mann= 5 ,-1 , 0
       0     .07       0 4675.21     .04       0 4977.52     .07       0
 5362.69     .15       0 5726.19     .07       0
#XS Ineff= 4 ,-1
       0 2955.17  147.23 2955.17 4159.06  146.88 5155.88 5753.11  146.43
 5753.11 6141.06   148.8
Permanent Ineff=
       F       F       F       F
Bank Sta=4675.21,4977.52
XS Rating Curve= 0 ,0
Exp/Cntr=0.5,0.3

Type RM Length L Ch R = 1 ,94396.13,178.17,183.98,163.51
BEGIN DESCRIPTION:
Upstream Section - FRY ROAD (Updated March 2016)
END DESCRIPTION:
XS GIS Cut Line= 6
3004665.1250369413896981.12484253004754.1248589513895064.1250676
3004930.1251631113894466.12495133005422.1251633613893504.1249068
3005484.1250393513891772.12508993005606.1251234413891107.1251076
#Sta/Elev= 30
       0  147.94 1004.51  146.91 1014.51  148.08 1109.46   147.6 1124.45  145.44
 1139.44  147.62 1174.43  147.88 1199.42  146.31  1224.4  147.67 2307.07  147.77
 2872.01  145.31 2941.24   147.2 2951.12  145.59 3010.44  144.86 4075.34  146.84
 4404.39  145.21 4647.07  145.59 4678.47  147.26 4715.13   138.8 4741.92  129.94
 4757.89  129.91 4828.64  146.49 5121.56  143.72 5250.56  145.18  5284.8  147.21
 5343.72   146.8 5411.49  145.52 5864.41  144.72 5972.28  146.71  6043.2  147.71
#Mann= 6 ,-1 , 0
       0     .07       0 4678.47     .04       0 4828.64     .07       0
 5343.72     .15       0 5411.49     .07       0 5972.28     .15       0
#XS Ineff= 3 ,-1
       0 2941.24   147.2 2941.24 4708.05  146.88 4829.99  6043.2  146.13
Permanent Ineff=
       F       F       F
Bank Sta=4678.47,4828.64
XS Rating Curve= 0 ,0
Exp/Cntr=0.5,0.3

Type RM Length L Ch R = 3 ,94315.28,,,
BEGIN DESCRIPTION:
FRY ROAD
U00_1800
END DESCRIPTION:
Node Name=FRY ROAD
Bridge Culvert--1,0,-1,-1, 0
Deck Dist Width WeirC Skew NumUp NumDn MinLoCord MaxHiCord MaxSubmerge Is_Ogee
32,106,2.6,0, 60, 60, , , 0.98, 0, 0,0,,
       0  259.76  409.62  554.49  619.43  854.22 1019.07 1098.99 1243.86 1398.72
  1533.6 1818.34  1858.3 2073.05 2430.64 2653.29  2787.1  2831.7 2851.52 2866.39
 2896.06 2910.88 2945.45 2994.83 3152.68 3417.97 3560.67 3653.65 3721.13 4031.46
 4084.72 4159.09 4179.09 4214.09 4234.09 4294.09 4424.09 4553.97 4602.82 4651.66
 4705.38 4708.05 4744.45 4829.99 4833.53 4838.49 4863.29 4893.06 5017.09 5101.43
 5318.12 5322.92 5410.96 5545.52 5595.44 5684.85 5763.12    5806 5951.99 6042.89
  149.85  149.65  149.84  149.59  149.83  149.62   149.9  149.57  149.79  149.52
  149.77  149.27  149.51  148.92  148.91  148.21  148.16  148.38  148.11  147.55
  147.55  148.14  148.37  147.97  147.73  147.68  147.97  147.82  148.11  148.06
  148.33  148.02  147.18  146.88  147.64  147.92  147.93  149.08  150.22  150.85
  153.97  154.02  154.07  154.19  152.96  150.75   150.9  150.51  147.99  146.97
  147.05  146.76  146.89  146.51  146.72  146.31  146.59  146.24  146.13  146.33
       0       0       0       0       0       0       0       0       0       0
       0       0       0       0       0       0       0       0       0       0
       0       0       0       0       0       0       0       0       0       0
       0       0       0       0       0       0       0       0       0       0
       0  148.15  148.02  148.34       0       0       0       0       0       0
       0       0       0       0       0       0       0       0       0       0
       0  259.76  409.62  554.49  619.43  854.22 1019.07 1098.99 1243.86 1398.72
  1533.6 1818.34  1858.3 2073.05 2430.64 2653.29  2787.1  2831.7 2851.52 2866.39
 2896.06 2910.88 2945.45 2994.83 3152.68 3417.97 3560.67 3653.65 3721.13 4031.46
 4084.72 4159.09 4179.09 4214.09 4234.09 4454.09 4568.63 4602.82    4637 4671.19
 4685.85 4691.61  4729.8 4814.75  4823.6 4853.37 4863.29 4893.06 5046.86  5131.2
 5337.32 5356.52 5410.96 5545.52 5595.44 5684.85 5763.12    5806 5951.99 6042.89
  149.85  149.65  149.84  149.59  149.83  149.62   149.9  149.57  149.79  149.52
  149.77  149.27  149.51  148.92  148.91  148.21  148.16  148.38  148.11  147.55
  147.55  148.14  148.37  147.97  147.73  147.68  147.97  147.82  148.11  148.06
  148.33  148.02  147.18  146.88  147.64  147.98     149  149.75  151.05  153.13
  153.41  153.44  153.63  154.06  153.38  151.07  150.78  150.84  147.87  146.89
  147.05  146.76  146.89  146.51  146.72  146.31  146.59  146.24  146.13  146.33
       0       0       0       0       0       0       0       0       0       0
       0       0       0       0       0       0       0       0       0       0
       0       0       0       0       0       0       0       0       0       0
       0       0       0       0       0       0       0       0       0       0
       0  147.79  148.29  148.11       0       0       0       0       0       0
       0       0       0       0       0       0       0       0       0       0
Pier Skew, UpSta & Num, DnSta & Num=  ,4747.05, 2 ,4729.27, 2 , 0 , 0 , 0 ,,
     1.4     1.4
     138     149
     1.4     1.4
     138     149
Pier Skew, UpSta & Num, DnSta & Num=  ,4792.3, 2 ,4774.28, 2 , 0 , 0 , 0 ,,
     1.4     1.4
     138     149
     1.4     1.4
     138     149
Abutment Skew #Up #Dn= , 2 , 2
 4706.06 4729.32
  148.07  139.83
 4690.67 4715.83
  148.21  139.91
Abutment Skew #Up #Dn= , 2 , 3
 4805.77 4831.06
  139.91  148.22
 4793.11 4814.71 4814.91
  140.03 148.115 148.115
BR Coef=-1 , 1 , 1 ,1.25, 0 ,,,0.8,-1,2,0,
WSPro=,,,, 1 ,,,, 0 ,,,, 0 ,,,,-1 ,-1 ,-1 , 0 , 0 , 0 , 0 , 0
BC Design=,, 0 ,, 0 ,,,,,,
BC Use User HTab Curves=0
BC User HTab FreeFlow(D)= 0

Type RM Length L Ch R = 1 ,94212.15,99.25,63.66,20.93
BEGIN DESCRIPTION:
Downstream Section - FRY ROAD (Updated March 2016)
END DESCRIPTION:
XS GIS Cut Line= 6
3004912.1248710313896915.12497453004958.1251071113894997.1248735
3005120.1251111913894395.12509333005590.1251554513893422.1250708
3005648.1250394413891689.12492783005870.1249235313891064.1248655
#Sta/Elev= 30
       0  148.01  484.63  146.93  814.38  147.56  894.32   146.8 1428.92  147.71
 1883.58  146.79 2008.28   147.6 2792.51  145.38 2802.46  147.01 2822.35  147.35
 2837.27  145.25 3726.25  146.35 4349.41  145.98 4504.41  145.01 4578.72  145.12
 4661.89  146.26  4676.4  147.26 4681.47  146.59 4738.44  130.27 4758.17  133.82
 4778.46  135.29 4811.22   145.7 4818.87  146.26 4928.11  144.48 4977.72   145.3
 5141.44  144.23 5416.26  144.25 5893.84  145.43 6015.77  146.68  6042.7  147.02
#Mann= 4 ,-1 , 0
       0     .07       0 4681.47     .04       0 4818.87     .07       0
 6015.77     .15       0
#XS Ineff= 3 ,-1
       0 2822.35     147 2822.35 4691.93  146.38 4818.96  6042.7  146.13
Permanent Ineff=
       F       F       F
Bank Sta=4681.47,4818.87
XS Rating Curve= 0 ,0
Exp/Cntr=0.5,0.3

Type RM Length L Ch R = 1 ,94148.49,94.99,98.61,96.51
BEGIN DESCRIPTION:
Updated (March 2016)
END DESCRIPTION:
XS GIS Cut Line= 6
3005639.2372619513896786.47234473005821.6735768613894283.2598314
3005742.8663197813892329.5685288 3005667.507874713891778.0312461
3005724.2052678613891403.2360639 3005875.007459713891069.1468371
#Sta/Elev= 30
       0   147.5  579.97  146.17 1725.96   147.9 2248.73   145.3 2373.77  147.86
 2464.85  145.97 2479.85  144.39 2496.25  145.98 2534.83  146.87 2630.49  144.77
 2999.51  145.49    3000   147.7    3800   147.7    3890   146.7    3900  144.75
 4282.62  144.06 4342.58  134.14 4503.96  133.81 4541.89  130.04 4579.79  141.59
 4602.35  145.64 4703.01  146.31 4725.31     148    5200   148.4 5236.56  144.61
 5340.23  146.04 5434.03  144.66  5493.3  147.45    5735  147.13 5788.71  146.93
#Mann= 6 ,-1 , 0
       0     .07       0 2496.25     .12       0 2630.49     .07       0
 4282.62     .04       0 4602.35     .07       0    5735     .15       0
#XS Ineff= 4 ,-1
       0 2534.83  146.87                         4709.33  5493.3   146.4
  5493.3 5788.71  147.45
Permanent Ineff=
       F       F       F       F
#Block Obstruct= 1 ,-1
       0  594.97  146.96
Bank Sta=4282.62,4602.35
XS Rating Curve= 0 ,0
Exp/Cntr=0.3,0.1

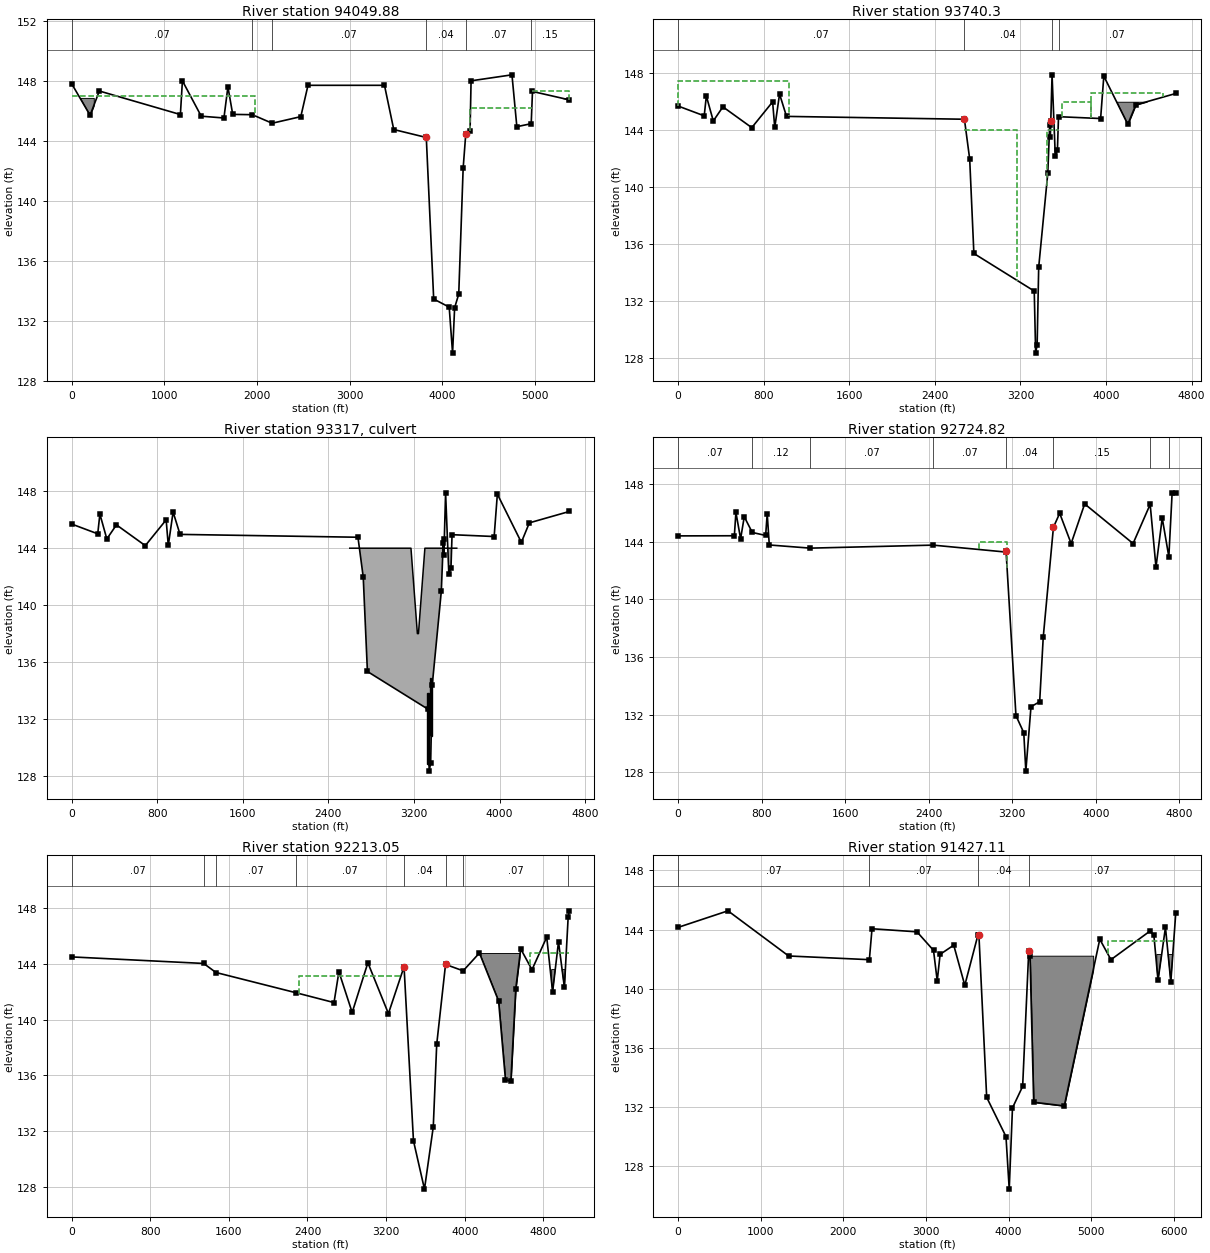
Type RM Length L Ch R = 1 ,94049.88,274.6,309.58,299.42
BEGIN DESCRIPTION:
Updated (March 2016)
END DESCRIPTION:
Node Name=AC
XS GIS Cut Line= 6
3006358.8375287813896319.15011663005827.2910196913892288.1234018
3005763.9922617813892178.24599683005763.9922617813891726.4388296
3005778.5801591113891524.29258043005896.2515116913891016.4205646
#Sta/Elev= 30
       0  147.82   199.8   145.7   299.7  147.32 1173.82  145.75 1195.62     148
  1398.6  145.64 1643.36  145.52 1686.45   147.6 1738.26  145.76 1949.66  145.74
  2163.5  145.17 2472.52  145.61    2550   147.7    3375   147.7    3475  144.75
 3825.97  144.22 3905.77  133.44 4073.05   132.9 4109.38  129.83 4131.63  132.86
 4175.97  133.77 4223.52  142.17 4251.96  144.48    4298  144.65    4309     148
    4750   148.4 4802.69  144.94 4957.48  145.14  4971.3  147.29 5368.49  146.73
#Mann= 6 ,-1 , 0
       0     .07       0 1949.66     .12       0  2163.5     .07       0
 3825.97     .04       0 4251.96     .07       0 4957.48     .15       0
#XS Ineff= 4 ,-1
       0 1983.02  146.96                            4298  4971.3   146.2
  4971.3 5368.49  147.29
Permanent Ineff=
       F       F       F       F
#Block Obstruct= 3 ,-1
       0  239.76  146.86                          4971.3 5368.49  146.84
Bank Sta=3825.97,4251.96
XS Rating Curve= 0 ,0
Exp/Cntr=0.3,0.1

Type RM Length L Ch R = 1 ,93740.3 ,854.24,1015.49,680.15
BEGIN DESCRIPTION:
Updated (March 2016)
END DESCRIPTION:
XS GIS Cut Line= 6
  3007022.957263 13895359.787534 3006444.543722213892444.9019596
 3006109.170049113892100.2418878  3006064.81154213892054.6553648
 3006061.349934813892025.1400038 3005932.359707213890926.8039459
#Sta/Elev= 30
       0   145.7  244.73  145.01  264.71   146.4  329.64  144.65  419.54  145.64
  689.24  144.18  884.02  145.99     904  144.19  948.95  146.54 1013.88  144.97
 2676.62  144.77 2725.89  141.97 2764.94  135.34 3329.04   132.7 3342.24  128.34
 3356.09  128.93 3370.72  134.38 3455.61  140.97 3473.49  144.38 3479.57  143.52
 3483.75  144.66  3495.6  147.89 3525.75   142.2 3545.75   142.6  3555.9  144.95
 3949.43  144.82 3979.32   147.8 4203.48  144.41  4278.2  145.78 4651.81  146.58
#Mann= 4 ,-1 , 0
       0     .07       0 2676.62     .04       0  3495.6     .07       0
  3555.9     .07       0
#XS Ineff= 5 ,-1
       0 1034.76  147.46 2676.62    3172     144 3583.94 3857.26     146
 3857.26 4534.73  146.58    3444    3556     144
Permanent Ineff=
       F       T       F       F       T
#Block Obstruct= 2 ,-1
                         4036.59    4479     146
Bank Sta=2676.62,3483.75
XS Rating Curve= 0 ,0
Exp/Cntr=0.5,0.3

Type RM Length L Ch R = 2 ,93317   ,,,
BEGIN DESCRIPTION:
Pipeline Easement Crossing
END DESCRIPTION:
Node Name=TN PIPELINE ESMT
Bridge Culvert--1,0,-1,-1, 0
Deck Dist Width WeirC Skew NumUp NumDn MinLoCord MaxHiCord MaxSubmerge Is_Ogee
30,259,2.6,0, 6, 6, 138, , 0.98, 0, 4,4,,
    2600    3172    3232    3242    3302    3600
     144     144     138     138     144     144
                                                
    2882    3150    3210    3220    3280    3600
     144     144     138     138     144     144
                                                
BR Coef=-1 , 0 , 0 ,, 0 ,,,0.8,-1,,0,
WSPro=,,,, 1 ,,,, 0 ,,,, 0 ,,,,-1 ,-1 ,-1 , 0 , 0 , 0 , 0 , 0
Culvert=2,5,10,310,0.013,0.5,1,8,1,128.84,3326.5,128.78,3376.5,Culvert #4  , 0 ,20
Culvert Bottom n=0.013
Culvert=2,5,10,310,0.013,0.5,1,8,1,128.86,3339.5,128.79,3389.5,Culvert #2  , 0 ,20
Culvert Bottom n=0.013
Culvert=2,4,6,310,0.013,0.5,1,8,1,130.89,3353.5,130.64,3403.5,Culvert #1  , 0 ,20
Culvert Bottom n=0.013
Culvert=2,4,6,310,0.013,0.5,1,8,1,130.78,3361.5,130.65,3411.5,Culvert #3  , 0 ,20
Culvert Bottom n=0.013
BC Design=,, 0 ,, 0 ,,,,,,
BC Use User HTab Curves=0
BC User HTab FreeFlow(D)= 0

Type RM Length L Ch R = 1 ,92724.82,559.57,511.77,496.93
BEGIN DESCRIPTION:
UPDATED (February 2017)
END DESCRIPTION:
XS GIS Cut Line= 5
3007719.2491780213894953.07345243006844.8299951113891942.2901039
 3006722.990015713891810.68997343005987.0689153713890855.7276445
3005790.9180609413890709.9241304
#Sta/Elev= 30
       0   144.4  539.17  144.41  554.15  146.03  599.08   144.2  634.03  145.73
  710.54  144.64  838.71  144.43  853.69  145.94  873.66  143.77 1265.63  143.55
 2441.39  143.76  3135.2  143.28 3140.18  143.32 3234.84  131.92 3309.56  130.74
 3329.32  128.07 3378.59  132.54 3461.75  132.89 3495.91  137.37 3593.54     145
 3653.32  145.97 3762.93  143.87 3892.45  146.62 4355.77  143.87 4519.47  146.59
 4575.04  142.23  4634.9  145.64 4698.18  142.95 4729.66  147.39 4764.58  147.35
#Mann= 8 ,-1 , 0
       0     .07       0  710.54     .12       0 1265.63     .07       0
 2441.39     .07       0  3135.2     .04       0 3593.54     .15       0
 4519.47     .07       0 4698.18     .15       0
#XS Ineff= 2 ,-1
    2880    3150     144 3653.32 4764.58   145.1
Permanent Ineff=
       F       F
#Block Obstruct= 2 , 0
       0                 4565.07       0  144.31
Bank Sta=3140.18,3593.54
XS Rating Curve= 0 ,0
Exp/Cntr=0.3,0.1

Type RM Length L Ch R = 1 ,92213.05,385.4,785.94,950.63
BEGIN DESCRIPTION:
UPDATED (February 2017)
END DESCRIPTION:
Node Name=AB
XS GIS Cut Line= 5
 3007876.631409213894882.57917093007487.91991627 13891968.569907
3007147.3799149413891551.40998023007033.6987118613891391.2229646
3006122.9803889413890342.5095108
#Sta/Elev= 30
       0  144.51 1344.07  144.04 1469.04  143.39 2286.56  141.93 2669.83  141.23
 2719.83  143.44 2854.82  140.52 3014.46  144.09 3223.45  140.44 3377.89  143.71
 3382.67  143.78 3478.32   131.3 3590.23  127.83 3679.74   132.3 3714.72  138.23
 3804.64  143.97 3983.75  143.51 4149.37  144.79 4344.23  141.34 4414.17  135.68
 4469.13  135.58  4519.1  142.23 4569.06  145.09 4683.97  143.59 4833.86  145.93
 4893.81     142 4953.77   145.6 5013.72  142.32 5052.09  147.38 5063.68  147.82
#Mann= 8 ,-1 , 0
       0     .07       0 1344.07     .12       0 1469.04     .07       0
 2286.56     .07       0 3377.89     .04       0 3804.64     .15       0
 3983.75     .07       0 5052.09     .15       0
#XS Ineff= 2 ,-1
 2316.69 3348.68  143.12 4658.99 5063.68  144.77
Permanent Ineff=
       F       F
#Block Obstruct= 2 ,-1
 4149.37 4559.07  144.79 4883.82 5063.68   143.6
Bank Sta=3382.67,3804.64
XS Rating Curve= 0 ,0
Exp/Cntr=0.3,0.1

Type RM Length L Ch R = 1 ,91427.11,471.39,483.13,469.42
BEGIN DESCRIPTION:
UPDATED (February 2017)
END DESCRIPTION:
XS GIS Cut Line= 5
3008163.3526205313894966.42086673007737.91777585 13891657.479978
3007717.01000927  13891204.669863007677.95004803 13890761.969958
3007456.2060689513888986.6798734
#Sta/Elev= 30
       0  144.15  604.31  145.27 1338.46  142.22  2315.3  141.97 2347.31  144.06
 2891.68  143.85 3091.45   142.6  3136.4  140.54 3171.35  142.33 3336.16  142.95
 3469.98  140.24 3630.77  143.67  3640.7  143.66 3734.91  132.67 3968.37  130.02
 4007.71  126.47 4047.04  131.96 4169.96  133.41 4243.87  142.56 4258.86  142.24
 4303.84  132.34 4673.65  132.09 5103.43  143.35 5238.36  141.97 5708.12  143.89
  5758.1  143.62 5808.07  140.57 5898.03  144.15    5963  140.47 6022.96  145.14
#Mann= 4 ,-1 , 0
       0     .07       0  2315.3     .07       0 3630.77     .04       0
 4243.87     .07       0
#XS Ineff= 2 ,-1
 2354.21 3632.71  143.66 5198.38 6022.96   143.2
Permanent Ineff=
       F       F
#Block Obstruct= 2 ,-1
 4243.87 5023.47  142.24 5793.08 6022.96  142.32
Bank Sta=3640.7,4243.87
XS Rating Curve= 0 ,0
Exp/Cntr=0.3,0.1

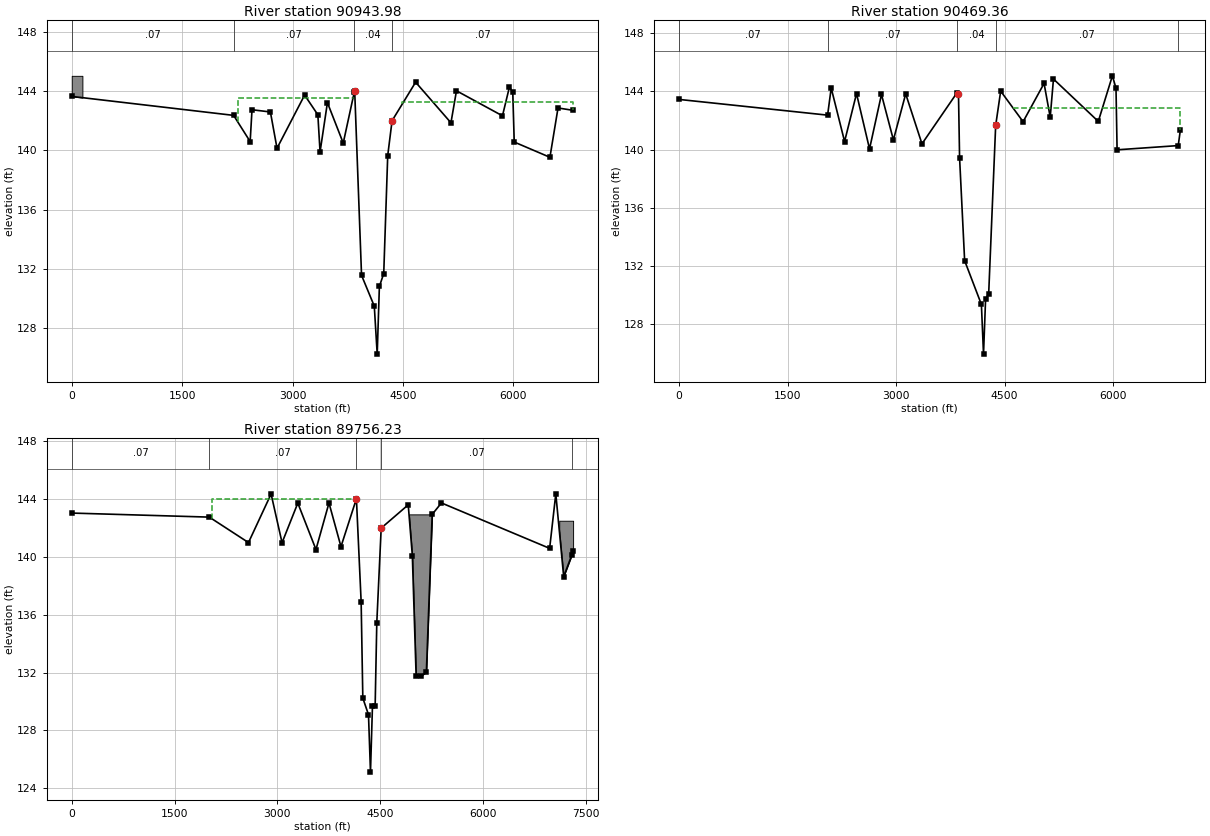
Type RM Length L Ch R = 1 ,90943.98,397.97,474.62,519.56
BEGIN DESCRIPTION:
UPDATED (February 2017)
END DESCRIPTION:
XS GIS Cut Line= 4
3008347.9677368613895020.4050107 3008189.805979713891095.9312323
3008114.11879511  13890632.348173007968.3241391913888222.2076491
#Sta/Elev= 30
       0  143.64 2199.42  142.36  2424.2  140.59  2449.2  142.74 2699.12  142.59
 2789.09  140.14 3163.97  143.73 3343.91   142.4  3373.9  139.89 3473.87  143.22
  3688.8  140.49 3839.75  143.95 3844.63  143.98 3937.56  131.56 4110.71  129.48
 4150.29  126.24 4179.88  130.81 4239.01  131.68 4293.22  139.65  4352.4     142
 4672.32   144.6 5152.25  141.86 5227.24  144.02 5852.14  142.33 5947.12  144.28
 5992.11  143.91 6012.11  140.56 6497.03  139.53 6607.02  142.86 6811.98   142.7
#Mann= 4 ,-1 , 0
       0     .07       0 2199.42     .07       0 3839.75     .04       0
  4352.4     .07       0
#XS Ineff= 2 ,-1
 2258.35 3832.78  143.53 4492.35 6811.98  143.26
Permanent Ineff=
       F       F
#Block Obstruct= 2 , 0
       0  144.91  145.03 5947.12       0   142.5
Bank Sta=3844.63,4352.4
XS Rating Curve= 0 ,0
Exp/Cntr=0.3,0.1

Type RM Length L Ch R = 1 ,90469.36,706,713.14,720.38
BEGIN DESCRIPTION:
UPDATED (February 2017)
END DESCRIPTION:
XS GIS Cut Line= 5
 3008532.582853213895074.38915473008622.6099041113891008.9199234
3008622.60990411 13890862.7099143008617.3002034413890650.3543676
 3008508.8388062 13888150.357071
#Sta/Elev= 30
       0  143.45 2053.49  142.37 2103.35  144.23  2288.2  140.56 2453.07  143.85
 2632.92  140.05 2797.79  143.79 2962.66  140.67 3132.52  143.83 3357.34   140.4
 3842.09  143.91 3862.05  143.82    3877  139.45  3946.8  132.38 4178.54  129.37
 4207.78  125.96 4236.34  129.72 4279.31  130.12 4375.68  141.66 4445.06  144.02
 4754.73  141.92 5044.41  144.55 5129.32  142.23 5174.27  144.85 5793.61  141.94
  5988.4  145.07 6038.35  144.22 6053.33  139.99 6898.05  140.28 6927.39  141.34
#Mann= 5 ,-1 , 0
       0     .07       0 2053.49     .07       0 3842.09     .04       0
 4375.68     .07       0 6898.05     .12       0
#XS Ineff= 2 ,-1
 2111.99  3859.5  143.78 4609.88 6927.39  142.89
Permanent Ineff=
       F       T
#Block Obstruct= 2 , 0
       0                  5988.4       0   142.5
Bank Sta=3862.05,4375.68
XS Rating Curve= 0 ,0
Exp/Cntr=0.3,0.1

Type RM Length L Ch R = 1 ,89756.23,175.18,156.89,155.73
BEGIN DESCRIPTION:
UPDATED (February 2017)
END DESCRIPTION:
XS GIS Cut Line= 6
3009170.0700952713895260.79987113009330.7600626113891177.1499019
3009320.1199920313890989.10008123009309.0701453513890781.0299593
3009255.7628372813888019.95641323009254.4567375313887952.3112073
#Sta/Elev= 30
       0  143.03 2007.15  142.75 2577.99  140.99 2907.74  144.35 3067.62  140.98
 3297.44  143.72 3562.23  140.51 3752.09  143.73 3926.95  140.71 4152.23  144.02
 4221.11   136.9 4245.69  130.24 4328.38  129.09  4357.4  125.12 4386.42  129.72
 4425.24  129.66 4449.54  135.46  4513.5  141.99 4908.01   143.6 4967.94  140.08
 5022.87   131.8 5087.79  131.75 5172.69  132.03 5257.58  142.94 5392.42  143.73
 6970.47  140.59 7060.36  144.36 7175.22  138.64 7292.81  140.11 7312.79  140.42
#Mann= 5 ,-1 , 0
       0     .07       0 2007.15     .07       0 4152.23     .04       0
  4513.5     .07       0 7292.81     .12       0
#XS Ineff= 1 ,-1
 2047.43 4148.78  143.99
Permanent Ineff=
       F
#Block Obstruct= 2 ,-1
 4908.01 5257.58  142.94  7110.3 7312.79   142.5
Bank Sta=4152.23,4513.5
XS Rating Curve= 0 ,0
Exp/Cntr=0.3,0.1