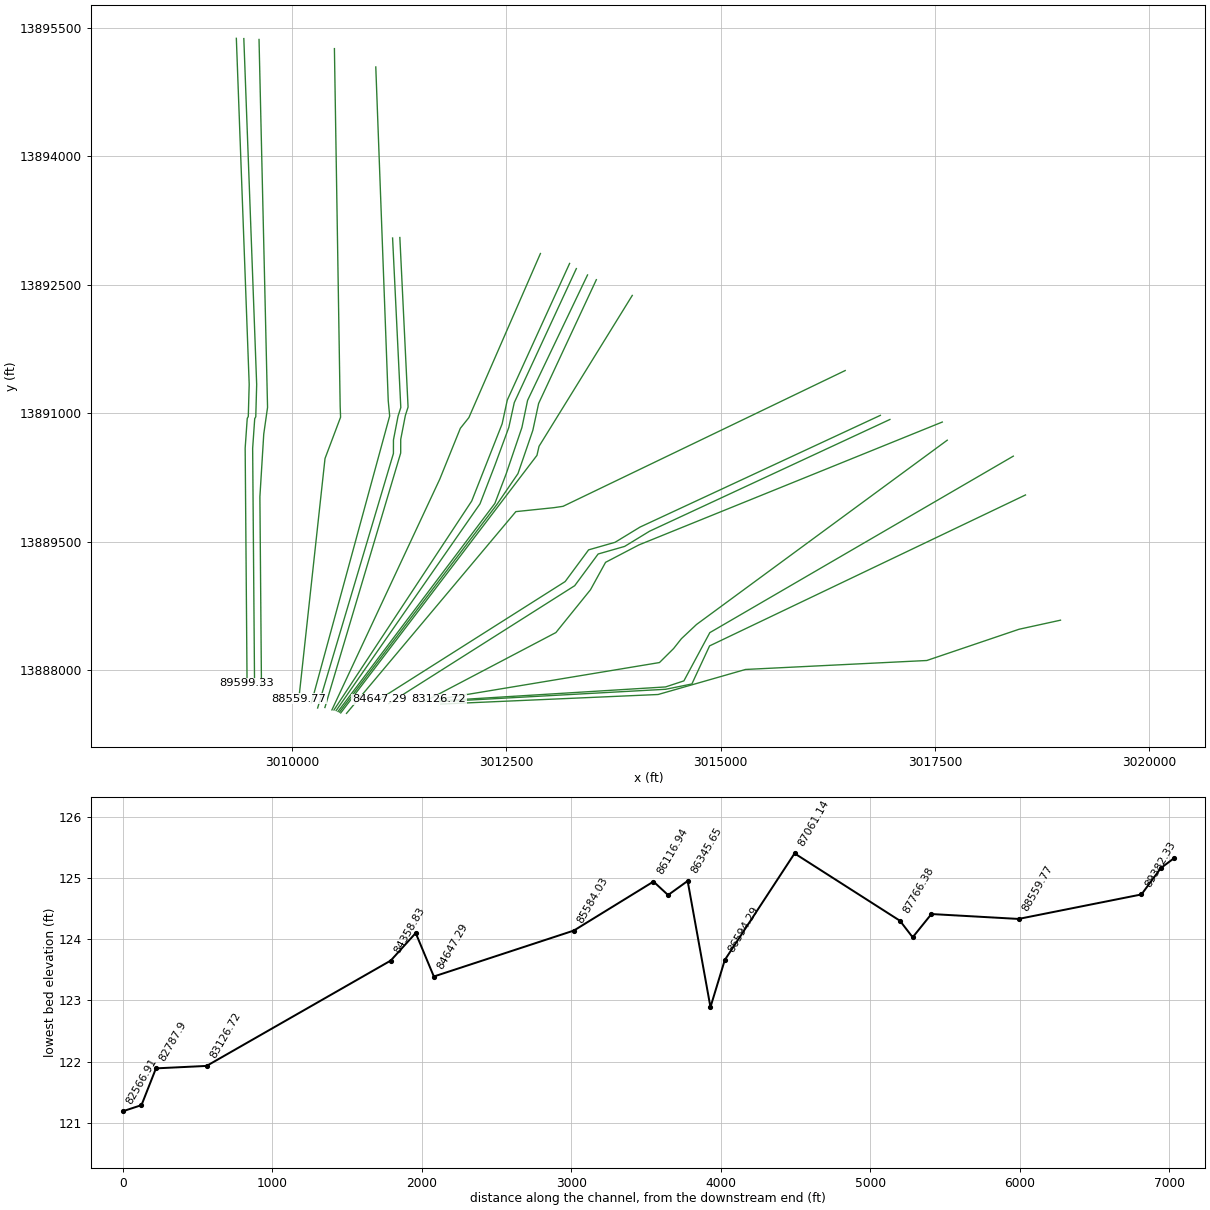
HEC-RAS study U100-00-00.prj: U100-00-00

--- U100-00-00.g01 (geometry) --- (continued)

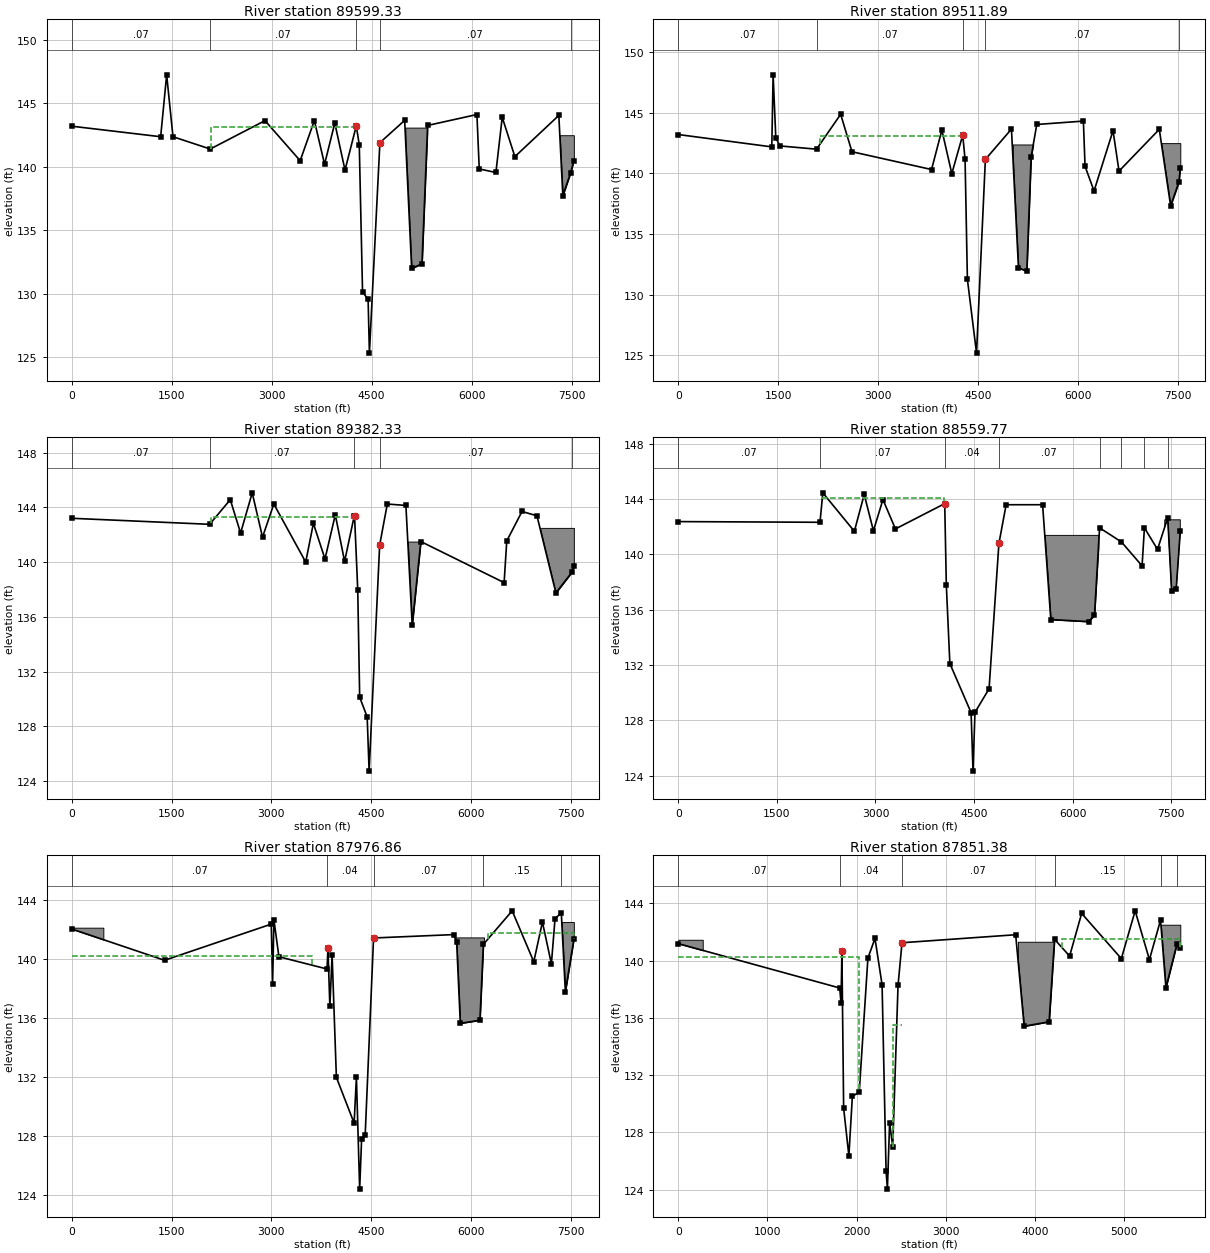
Type RM Length L Ch R = 1 ,89599.33,87.74,87.44,87.16
BEGIN DESCRIPTION:
Upstream Section - REMOVED CROSSING "C"
UPDATED (February 2017)
END DESCRIPTION:
XS GIS Cut Line= 6
3009346.83417745   13895378.36233009496.7991006113891339.8411776
3009486.2495810213890963.77007943009473.9986212713890942.1697288
3009449.8707167813890594.85907183009471.9855019513887851.1076695
#Sta/Elev= 30
       0  143.21 1334.04  142.38 1423.97  147.26 1518.91  142.38 2078.55  141.41
 2899.65  143.65 3427.72  140.49 3640.62  143.65 3793.88  140.21 3947.29  143.46
 4100.72  139.75 4269.71  143.23 4314.66  141.75 4363.96  130.15  4447.4  129.55
 4466.93  125.32 4624.26  141.91    4996  143.67 5100.94     132 5255.85  132.36
  5340.8  143.27 6080.37  144.13 6115.35  139.84  6365.2  139.56 6460.15  143.91
 6650.04  140.81 7309.65  144.06 7369.61  137.74 7487.33  139.55 7535.04   140.5
#Mann= 5 ,-1 , 0
       0     .07       0 2078.55     .07       0 4269.71     .04       0
 4624.26     .07       0 7487.33     .12       0
#XS Ineff= 1 ,-1
 2089.02 4270.48  143.18
Permanent Ineff=
       F
#Block Obstruct= 2 ,-1
    5006 5335.81   143.1 7309.65 7535.04   142.5
Bank Sta=4269.71,4624.26
XS Rating Curve= 0 ,0
Exp/Cntr=0.3,0.1

Type RM Length L Ch R = 1 ,89511.89,126.28,129.56,113.35
BEGIN DESCRIPTION:
Downstream Section - REMOVED CROSSING "C"
UPDATED (February 2017)
END DESCRIPTION:
XS GIS Cut Line= 6
3009434.18111561 13895375.3859283009584.1460387713891336.8648056
3009573.5965191913890960.79370743009561.3455594513890939.1933569
3009537.2176549413890591.88269983009559.3324401113887848.1309694
#Sta/Elev= 30
       0  143.21 1403.99  142.19 1423.97  148.14 1463.95  142.96  1523.9  142.27
 2075.55     142 2437.57  144.88 2607.56  141.79 3801.81  140.32 3956.48  143.58
 4105.66  139.98 4269.67  143.17 4304.65  141.16 4339.53  131.26 4476.69  125.16
 4609.54  141.16    5001  143.66 5105.94  132.22 5230.86  131.91 5295.83  141.35
 5380.78  144.04 6080.37  144.32 6105.35  140.59 6240.27  138.55 6525.11  143.53
 6615.05  140.19  7219.7  143.64  7389.6  137.33 7514.03  139.29 7535.04  140.47
#Mann= 5 ,-1 , 0
       0     .07       0 2075.55     .07       0 4269.67     .04       0
 4609.54     .07       0 7514.03     .12       0
#XS Ineff= 1 ,-1
 2133.53 4266.36  143.09
Permanent Ineff=
       F
#Block Obstruct= 2 ,-1
 5020.99  5335.8  142.39  7219.7 7535.04   142.5
Bank Sta=4269.67,4609.54
XS Rating Curve= 0 ,0
Exp/Cntr=0.3,0.1

Type RM Length L Ch R = 1 ,89382.33,856.05,822.55,781.87
BEGIN DESCRIPTION:
UPDATED (February 2017)
END DESCRIPTION:
Node Name=AA
XS GIS Cut Line= 6
3009611.6236741113895365.07722163009711.1339737813891070.8184217
3009666.7616871913890759.15073793009621.7227352713890026.6748407
3009639.2049837713887921.20168943009640.0406120313887820.5516283
#Sta/Elev= 30
       0   143.2 2073.21  142.76 2383.77  144.56 2538.68  142.12 2713.59  145.06
 2868.51  141.82 3038.42  144.24 3518.16     140  3633.1  142.83 3808.01  140.23
 3962.93  143.46 4102.85  140.05  4247.8  143.37 4252.56  143.38 4300.29  137.98
 4329.66  130.13 4442.28  128.69 4471.65  124.73  4630.2  141.25 4745.02  144.24
 5024.59  144.14 5119.44   135.4 5249.23   141.5 6501.63   138.5 6541.55  141.55
 6771.06   143.7 6995.58  143.38 7279.98  137.75 7529.03  139.31 7550.27   139.7
#Mann= 5 ,-1 , 0
       0     .07       0 2073.21     .07       0  4247.8     .04       0
  4630.2     .07       0 7529.03     .12       0
#XS Ineff= 1 ,-1
 2087.96  4246.9  143.32
Permanent Ineff=
       F
#Block Obstruct= 2 ,-1
 5054.54 5249.23   141.5 6995.58 7550.27   142.5
Bank Sta=4252.56,4630.2
XS Rating Curve= 0 ,0
Exp/Cntr=0.3,0.1

Type RM Length L Ch R = 1 ,88559.77,573.33,582.92,688.64
BEGIN DESCRIPTION:
UPDATED (February 2017)
END DESCRIPTION:
XS GIS Cut Line= 6
3010491.5700769413895258.39994153010558.7799162713891083.2501554
3010563.6601558613890956.52993643010381.8501520313890473.9600354
3010087.0849935313887767.75744253010076.5869830313887671.3773859
#Sta/Elev= 30
       0  142.37 2156.35  142.32 2199.26  144.45  2679.1  141.67 2829.05  144.33
    2969  141.71 3113.95  143.96 3303.89  141.84 4053.69  143.67 4078.09  137.79
 4131.75  132.11 4454.75  128.56 4484.22  124.33 4513.69  128.58 4728.24  130.28
 4878.11  140.79 4987.82  143.59 5542.46  143.59 5667.33  135.29 6241.77  135.14
 6331.68   135.6 6409.38  141.92 6741.58   140.9 7055.96  139.17 7091.45  141.92
 7290.73  140.36 7445.85  142.65 7505.52  137.35 7574.42  137.48 7637.43  141.68
#Mann= 8 ,-1 , 0
       0     .07       0 2156.35     .07       0 4053.69     .04       0
 4878.11     .07       0 6409.38     .15       0 6741.58     .07       0
 7091.45     .15       0 7445.85     .07       0
#XS Ineff= 2 ,-1
 2191.33 4038.98  144.11  6511.5 7637.43  141.53
Permanent Ineff=
       F       T
#Block Obstruct= 2 ,-1
 5577.42 6391.62  141.41 7400.62 7637.43   142.5
Bank Sta=4053.69,4878.11
XS Rating Curve= 0 ,0
Exp/Cntr=0.3,0.1

Type RM Length L Ch R = 1 ,87976.86,143.4,125.48,197.19
BEGIN DESCRIPTION:
UPDATED (February 2017)
END DESCRIPTION:
XS GIS Cut Line= 5
3010974.4513290213895044.16152483011119.8299752813891147.6601315
3011136.4798763513890970.02990943010255.2175312813887739.7351889
3010222.9265853613887621.3712524
#Sta/Elev= 30
       0  142.03 1394.72  139.91 2999.39  142.36 3019.39  138.32 3039.38  142.65
 3114.37  140.15 3837.62  139.32 3851.84  140.71 3880.26  136.78 3914.08  140.26
  3978.5  131.98 4245.18  128.88 4279.49  131.98  4328.5  124.41 4357.91  127.82
 4411.57  128.09 4537.38  141.42  5741.8  141.65 5786.77  141.12 5841.75  135.64
  6136.6  135.85 6188.63  140.99 6621.37  143.26 6946.21  139.81 7076.14   142.5
 7211.08  139.67 7266.05  142.74  7360.3  143.11 7420.98  137.79 7548.67  141.33
#Mann= 5 ,-1 , 0
       0     .07       0 3837.62     .04       0 4537.38     .07       0
 6188.63     .15       0  7360.3     .07       0
#XS Ineff= 3 ,-1
       0 3615.31  140.23  4579.5 6261.54   138.4 6261.54 7548.67  141.77
Permanent Ineff=
       F       F       F
#Block Obstruct= 3 ,-1
       0   474.9  142.12 5771.78 6196.57  141.46    7371 7548.67   142.5
Bank Sta=3851.84,4537.38
XS Rating Curve= 0 ,0
Exp/Cntr=0.5,0.3

Type RM Length L Ch R = 1 ,87851.38,89.27,85,85.07
BEGIN DESCRIPTION:
Upstream Section - CROSSING "B"
UPDATED (February 2017)
END DESCRIPTION:
XS GIS Cut Line= 6
3011170.5844669513893047.58612173011266.4054695213891068.9532679
3011234.4727906113890968.76613243011180.6832000313890690.8693784
3011180.3095131113890532.34410493010295.8319513613887561.7673689
#Sta/Elev= 30
       0  141.18 1809.89  138.08 1824.55  137.02 1834.33  140.63 1853.88  129.68
 1912.53  126.36 1951.63  130.51 2028.75  130.81 2125.83  140.17 2205.29  141.54
 2284.74   138.3 2329.44   125.3 2344.33  124.03 2369.16  128.68 2404.09  126.99
 2463.45  138.26 2508.03  141.24 3782.03   141.8 3876.97  135.41 4156.79  135.72
 4217.69  141.48 4386.63  140.31 4521.54  143.29 4966.24  140.13 5121.14  143.47
 5281.03  140.06 5405.76  142.82 5465.91   138.1 5587.83  141.12 5627.28   140.9
#Mann= 6 ,-1 , 0
       0     .07       0 1809.89     .04       0 2508.03     .07       0
 4217.69     .15       0 5405.76     .07       0 5587.83     .12       0
#XS Ineff= 4 ,-1
       0 2023.35  140.23  2404.1 2508.03   135.5 2508.03 4306.69   138.4
 4306.69 5627.28  141.52
Permanent Ineff=
       F       F       F       F
#Block Obstruct= 3 ,-1
       0  274.44  141.45 3807.02 4217.69  141.31 5405.76 5627.28   142.5
Bank Sta=1834.33,2508.03
XS Rating Curve= 0 ,0
Exp/Cntr=0.5,0.3

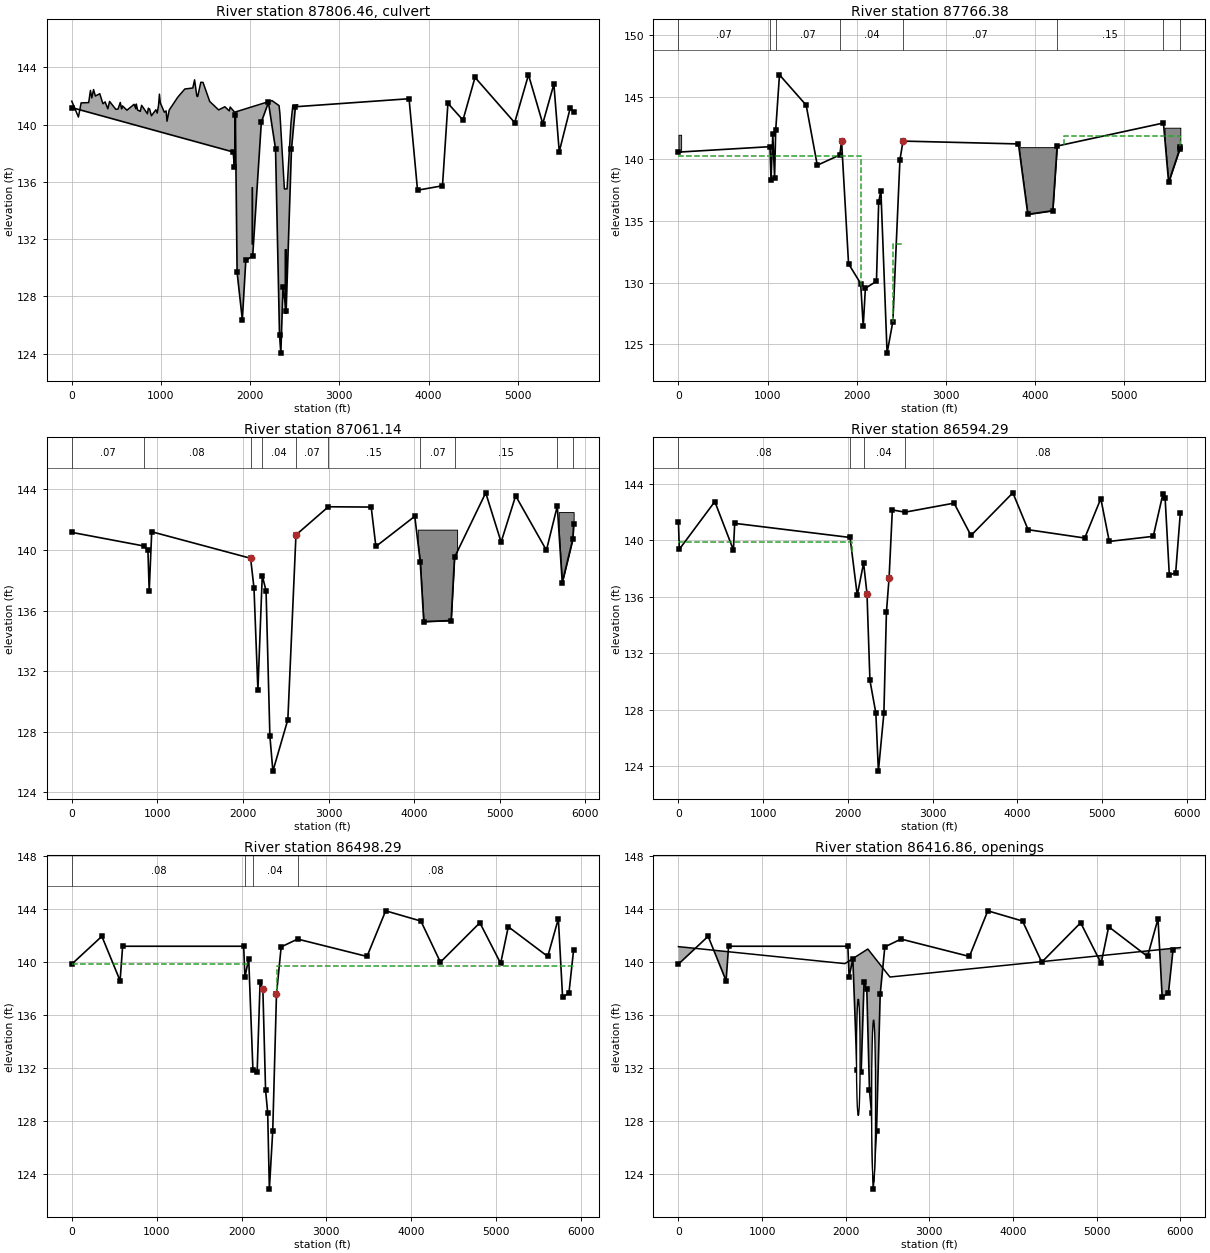
Type RM Length L Ch R = 2 ,87806.46,,,
BEGIN DESCRIPTION:
CROSSING "B"
END DESCRIPTION:
Node Name=CROSSING "B"
Bridge Culvert--1,0,-1,-1, 0
Deck Dist Width WeirC Skew NumUp NumDn MinLoCord MaxHiCord MaxSubmerge Is_Ogee
30,20,2.6,0, 60, 60, , , 0.98, 0, 3,3,,
       0   74.85  104.79  189.61  209.57  224.54   244.5  264.46  314.36  349.29
  374.24  404.17  424.13  493.99  518.94  543.89  558.86  568.84  618.73  698.57
  718.53  723.52  738.49  768.43   783.4  848.27  858.25  873.21  893.17  943.07
  958.04  973.01  982.99  992.97 1037.88 1057.84 1067.82 1092.77 1187.57 1267.41
 1357.23 1377.18 1402.13 1412.11 1447.04 1471.99 1546.84 1646.63 1716.49 1766.39
 1776.37 1826.27 2245.01 2324.46  2334.4 2384.15 2413.96 2458.49  2478.3 2532.84
  141.63  140.52  141.51  141.53  142.38  141.86  142.44  141.99  142.15  141.45
  141.58   141.1  141.61  141.06  141.08  141.54  141.09   141.3     141  141.41
   141.1  141.43  141.01  140.92  141.34  140.75  141.14  141.07  140.61  141.03
   140.8  141.34  142.12  141.51  140.86  140.95  140.23  141.01   141.9  142.48
  142.55  143.12  141.99  141.95  142.95  142.94  141.61  141.02  141.24  140.95
  141.22  140.86  141.67  141.32  140.74   135.5   135.5  140.16  141.31  141.37
       0       0       0       0       0       0       0       0       0       0
       0       0       0       0       0       0       0       0       0       0
       0       0       0       0       0       0       0       0       0       0
       0       0       0       0       0       0       0       0       0       0
       0       0       0       0       0       0       0       0       0       0
       0       0       0       0       0       0       0       0       0       0
       0   74.85  104.79  189.61  209.57  224.54   244.5  264.46  314.36  349.29
  374.24  404.17  424.13  493.99  518.94  543.89  558.86  568.84  618.73  698.57
  718.53  723.52  738.49  768.43   783.4  848.27  858.25  873.21  893.17  943.07
  958.04  973.01  982.99  992.97 1037.88 1057.84 1067.82 1092.77 1187.57 1267.41
 1357.23 1377.18 1402.13 1412.11 1447.04 1471.99 1546.84 1646.63 1716.49 1766.39
 1776.37 1826.27 2245.01 2324.46  2334.4 2384.15 2413.96 2458.49  2478.3 2532.84
  141.63  140.52  141.51  141.53  142.38  141.86  142.44  141.99  142.15  141.45
  141.58   141.1  141.61  141.06  141.08  141.54  141.09   141.3     141  141.41
   141.1  141.43  141.01  140.92  141.34  140.75  141.14  141.07  140.61  141.03
   140.8  141.34  142.12  141.51  140.86  140.95  140.23  141.01   141.9  142.48
  142.55  143.12  141.99  141.95  142.95  142.94  141.61  141.02  141.24  140.95
  141.22  140.86  141.67  141.32  140.74   135.5   135.5  140.16  141.31  141.37
       0       0       0       0       0       0       0       0       0       0
       0       0       0       0       0       0       0       0       0       0
       0       0       0       0       0       0       0       0       0       0
       0       0       0       0       0       0       0       0       0       0
       0       0       0       0       0       0       0       0       0       0
       0       0       0       0       0       0       0       0       0       0
BR Coef=-1 , 0 , 0 ,, 0 ,,,0.8,-1,,0,
WSPro=,,,, 1 ,,,, 0 ,,,, 0 ,,,,-1 ,-1 ,-1 , 0 , 0 , 0 , 0 , 0
Culvert=1,4,,78,0.013,0.5,1,1,3,131.62,2025.35,131.61,2047.87,Culvert #1  , 0 ,2
Culvert Bottom n=0.013
Multiple Barrel Culv=1,4.5,,78,0.013,0.7,1,1,1,126.78,126.77, 2,Culvert #2  , 0 ,2
 2395.85 2395.85 2401.85 2401.85
Culvert Bottom n=0.013
BC Design=,, 0 ,, 0 ,,,,,,
BC Use User HTab Curves=0
BC User HTab FreeFlow(D)= 0

Type RM Length L Ch R = 1 ,87766.38,1005.75,705.24,552.91
BEGIN DESCRIPTION:
Downstream Section - CROSSING "B"
UPDATED (February 2017)
END DESCRIPTION:
Node Name=Z
XS GIS Cut Line= 6
3011255.3864626913893053.29870873011351.2074652813891074.6658549
3011319.2747863513890974.47871943011265.4851957713890696.5819654
3011265.1115088613890538.0566919 3010380.633947113887567.4799559
#Sta/Elev= 30
       0  140.53 1026.43  140.97 1037.88  138.29 1057.84  141.98  1077.8  138.46
 1090.33  142.29 1132.68  146.77 1432.07  144.32 1556.82  139.47 1809.18   140.3
 1828.81  141.43 1907.34  131.51 2043.09  129.92 2071.76  126.47 2096.03  129.54
 2220.18   130.1 2245.01  136.49 2269.84  137.43 2339.36   124.3 2404.08  126.85
 2483.26   139.9 2517.93  141.42 3812.01  141.19 3916.94  135.51 4196.76   135.8
 4246.09  141.02 5438.16  142.88 5495.76  138.09 5622.27  140.82 5627.28  140.96
#Mann= 8 ,-1 , 0
       0     .07       0 1026.43     .08       0 1090.33     .07       0
 1809.18     .04       0 2517.93     .07       0 4246.09     .15       0
 5438.16     .07       0 5622.27     .12       0
#XS Ineff= 4 ,-1
       0 2045.87  140.23  2404.1 2517.93  133.12 2517.93 4321.68   138.4
 4321.68 5627.28  141.87
Permanent Ineff=
       F       F       F       F
#Block Obstruct= 3 ,-1
       0   29.94  141.93    3822 4246.09  140.93 5450.91 5627.28   142.5
Bank Sta=1828.81,2517.93
XS Rating Curve= 0 ,0
Exp/Cntr=0.5,0.3

Type RM Length L Ch R = 1 ,87061.14,395.44,466.86,456.39
BEGIN DESCRIPTION:
14-06-1909P
END DESCRIPTION:
XS GIS Cut Line= 6
 3012896.231606213892866.7095149 3012061.180126713890951.6598673
3011961.2600509413890826.14994783011721.7070523613890233.7019857
3010516.75703445 13887655.669084 3010462.468429113887539.5164292
#Sta/Elev= 30
       0  141.16  842.48  140.26  889.66  139.98  904.65  137.28     934   141.2
 2089.19  139.45 2128.65  137.49 2174.46  130.75 2225.31   138.3 2269.59  137.31
 2314.52  127.71 2349.47   125.4 2524.21   128.8 2619.07  140.99 2997.35  142.85
 3497.74  142.83 3552.66  140.23 4006.97  142.22 4070.74   139.2 4111.81  135.27
 4431.34  135.34 4471.14  139.51 4835.73  143.77 5015.46  140.52 5185.21  143.57
 5544.67  139.98 5671.85  142.89  5729.4  137.85 5853.33  140.73  5862.6   141.7
#Mann= 10 ,-1 , 0
       0     .07       0  842.48     .08       0 2089.19     .05       0
 2225.31     .04       0 2619.07     .07       0 2997.35     .15       0
 4070.74     .07       0 4471.14     .15       0 5671.85     .07       0
 5853.33     .12       0
#XS Ineff= 2 ,-1
       0 1509.42  139.89 4586.11  5862.6  139.74
Permanent Ineff=
       F       F
#Block Obstruct= 2 ,-1
 4041.92 4501.23  141.34 5689.46  5862.6   142.5
Bank Sta=2089.19,2619.07
XS Rating Curve= 0 ,0
Exp/Cntr=0.3,0.1

Type RM Length L Ch R = 1 ,86594.29,85.62,96,104.96
XS GIS Cut Line= 5
3013236.67488343 13892750.7663163012509.4020597313891156.1595971
3012449.3487021613890878.80450883012094.3139791513889977.7626757
3010486.3985598413887538.7117795
#Sta/Elev= 30
       0  141.28    9.99  139.36  429.42  142.74  649.12  139.31   664.1   141.2
 2026.45   140.2 2111.29  136.11 2186.17  138.39  2226.4  136.22 2261.06  130.08
 2330.95  127.77  2360.9  123.66  2425.8  127.76 2455.75   134.9 2487.45  137.36
 2525.64  142.15  2675.4  141.99 3254.57  142.63 3454.33  140.34 3948.72  143.36
 4128.49  140.75 4797.65  140.16 4987.41  142.95 5087.28  139.92 5606.63  140.28
 5721.48   143.3 5746.45  143.02 5796.39  137.53  5871.3  137.71 5926.23  141.92
#Mann= 4 ,-1 , 0
       0     .08       0 2026.45     .05       0 2186.17     .04       0
  2675.4     .08       0
#XS Ineff= 2 ,-1
       0 2047.57  139.89 2541.36 5926.23  139.74
Permanent Ineff=
       F       F
Bank Sta=2226.4,2487.45
XS Rating Curve= 0 ,0
Exp/Cntr=0.5,0.3

Type RM Length L Ch R = 1 ,86498.29,169.59,152.64,159.69
XS GIS Cut Line= 6
3013315.4293190813892690.54497983012590.9993374913891126.6458766
3012527.1261056713890836.70387123012364.36593249 13890393.995439
3012190.7547311513889944.7765212 3010512.0349915 13887531.883053
#Sta/Elev= 30
       0  139.85   354.7  141.95  569.52   138.6  599.49   141.2  2025.4   141.2
 2040.29  138.88 2084.98  140.25 2134.63  131.86 2184.28  131.72 2219.04   138.5
 2251.55  137.97 2283.58  130.35 2308.41  128.65 2328.27  122.89 2367.99  127.29
 2412.12   137.6 2467.29  141.15 2660.92  141.74 3478.61  140.43 3698.56  143.87
 4113.48   143.1 4343.43     140 4808.34  142.97 5053.29  139.91 5143.27  142.67
 5608.18  140.43 5733.16  143.27 5783.15  137.35 5858.13  137.69 5913.12  140.94
#Mann= 4 ,-1 , 0
       0     .08       0 2040.29     .05       0 2134.63     .04       0
 2660.92     .08       0
#XS Ineff= 2 ,-1
       0    2068  139.89    2416 5913.12  139.74
Permanent Ineff=
       F       F
Bank Sta=2251.55,2412.12
XS Rating Curve= 0 ,0
Exp/Cntr=0.5,0.3

Type RM Length L Ch R = 4 ,86416.86,,,
Node Name=GREENHOUSE ROAD
Bridge Culvert--1,0,-1,-1, 0
Deck Dist Width WeirC Skew NumUp NumDn MinLoCord MaxHiCord MaxSubmerge Is_Ogee
35,102,2.6,0, 5, 5, , , 0.98, 0, 0,0,,
       0    1990    2264    2528    6000
  141.17  139.89  140.99  138.88   141.1
                                        
       0    1990    2264    2528    6000
  141.17  139.89  140.99  138.88   141.1
                                        
BR Coef=-1 , 0 , 0 ,, 0 ,,,0.8,-1,,0,
WSPro=,,,, 1 ,,,, 0 ,,,, 0 ,,,,-1 ,-1 ,-1 , 0 , 0 , 0 , 0 , 0
Culvert=9,8.78,43,102.13,0.013,0.5,1,61,1,128.44,2150,128.34,2126,ConspanNorth, 0 ,35
Culvert Bottom n=0.04
Culvert Bottom Depth=2.2
Culvert=9,12.24,47,102,0.013,0.5,1,61,1,123.4,2333,123.3,2310,ConspanSouth, 0 ,35
Culvert Bottom n=0.013
BC Mult= 1 ,0,2065,0,2049
BC Mult= 2 ,2065,2270,2049,2225
BC Mult= 2 ,2200,2532,2160,2571
BC Mult= 1 ,2532,6000,2571,6000
BC Design=,, 0 ,, 0 ,,,,,,
BC Use User HTab Curves=0
BC User HTab FreeFlow(D)= 0

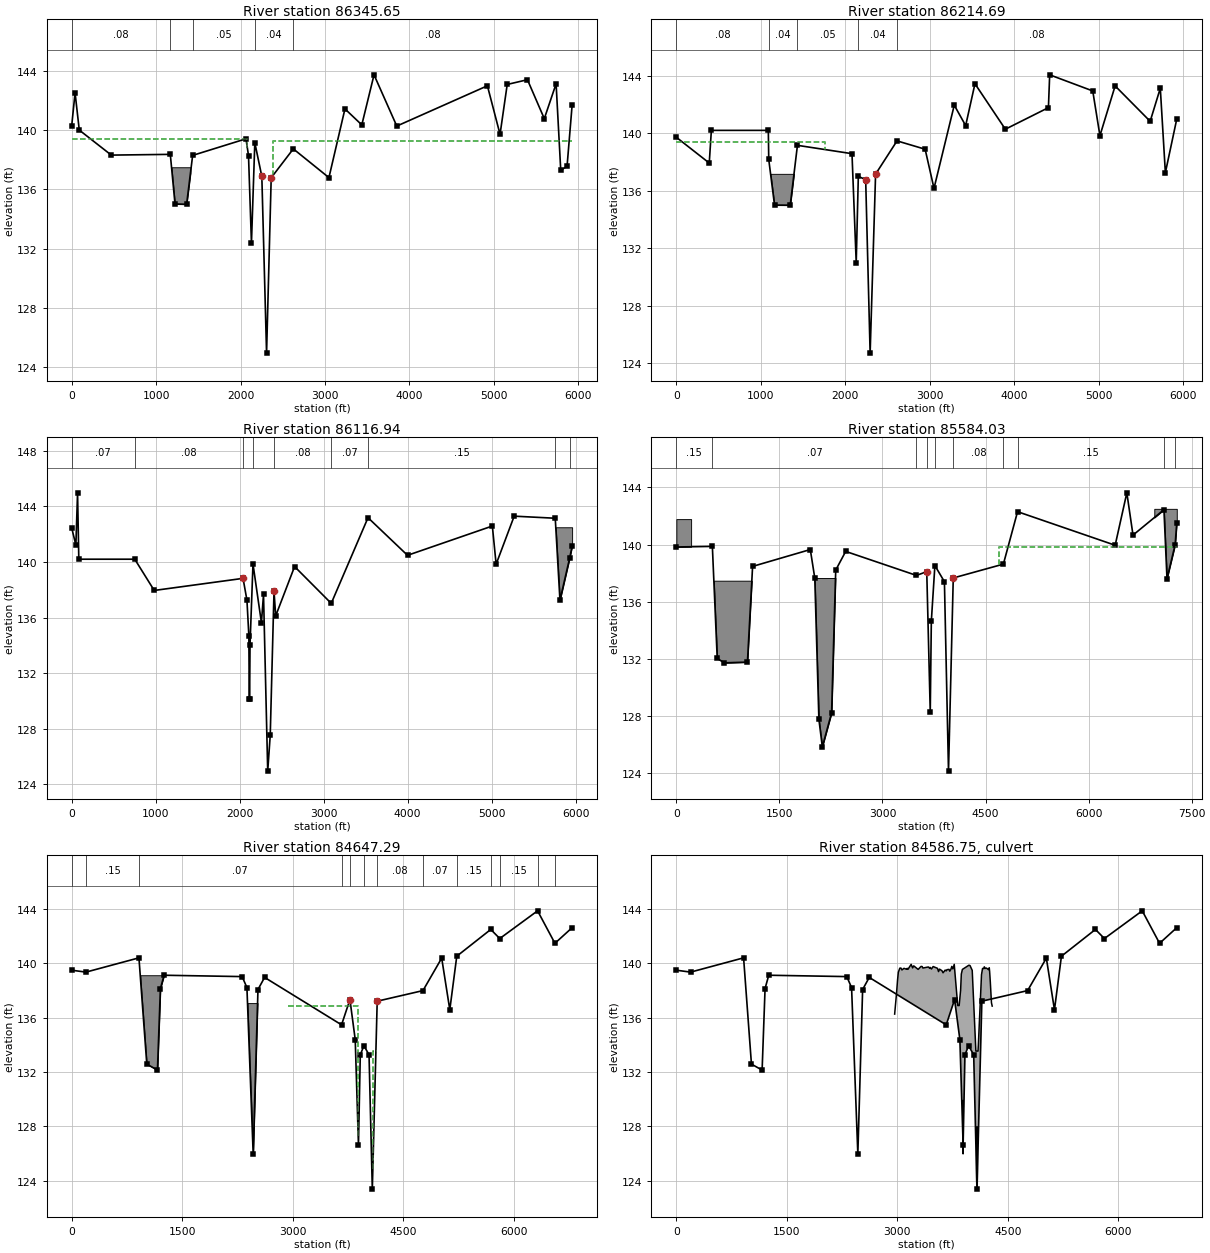
Type RM Length L Ch R = 1 ,86345.65,140.29,130.96,130.81
XS GIS Cut Line= 6
3013445.8893600113892616.34499693012746.2365598413891152.3692503
3012680.2642508113890836.39711333012496.2364036713890294.7302176
3012364.29211375  13889949.244363010533.7363916613887521.4664072
#Sta/Elev= 30
       0  140.29   39.94  142.53   89.87  140.01   469.3  138.32 1168.25  138.37
 1223.82  135.02 1361.48     135 1432.85   138.3 2064.77  139.42 2094.62  138.29
 2129.44  132.38 2169.23  139.16 2252.42  136.88 2308.52  124.95 2363.45  136.79
 2625.34  138.74  3047.3   136.8 3237.02  141.44 3436.73  140.36 3581.52  143.74
 3851.12  140.28 4924.54     143 5074.32  139.72  5159.2  143.09 5398.84  143.41
 5598.55  140.78 5738.35  143.14 5793.26   137.3 5868.15  137.56 5928.07  141.69
#Mann= 5 ,-1 , 0
       0     .08       0 1168.25     .04       0 1432.85     .05       0
 2169.23     .04       0 2625.34     .08       0
#XS Ineff= 2 ,-1
       0  2081.6  139.39    2383 5928.07  139.24
Permanent Ineff=
       F       F
#Block Obstruct= 1 ,-1
 1169.39 1407.15   137.5
Bank Sta=2252.42,2363.45
XS Rating Curve= 0 ,0
Exp/Cntr=0.5,0.3

Type RM Length L Ch R = 1 ,86214.69,265.13,97.75,71.27
XS GIS Cut Line= 6
3013548.9275397413892561.25225933012875.3163541613891116.8079698
3012807.6078281713890802.57172163012633.9969549213890297.3634144
3012384.8649072313889932.78015413010551.2783513413887514.6521163
#Sta/Elev= 30
       0  139.72   389.7  137.93  414.69   140.2 1089.17   140.2 1094.17  138.18
 1162.55  135.01 1348.69     135 1433.91  139.16    2080  138.58 2129.92  131.01
 2154.88     137 2241.94  136.78 2294.68  124.72 2359.39  137.16 2613.17  139.47
 2946.01  138.89    3051  136.17 3290.97  141.95 3425.95  140.53 3535.94  143.44
  3895.9  140.28 4405.85  141.78 4420.85  144.06 4930.81  142.94  5015.8  139.83
 5195.78  143.29 5610.74  140.83 5730.73  143.13 5790.73  137.26 5925.72  140.99
#Mann= 5 ,-1 , 0
       0     .08       0 1094.17     .04       0 1433.91     .05       0
 2154.88     .04       0 2613.17     .08       0
#XS Ineff= 2 ,-1
       0 1761.73  139.39 2629.96 5925.72  139.24
Permanent Ineff=
       F       F
#Block Obstruct= 1 ,-1
 1092.47 1402.71  137.18
Bank Sta=2241.94,2359.39
XS Rating Curve= 0 ,0
Exp/Cntr=0.3,0.1

Type RM Length L Ch R = 1 ,86116.94,1233.06,532.9,387.83
BEGIN DESCRIPTION:
14-06-1909P
END DESCRIPTION:
XS GIS Cut Line= 5
3013968.2399608613892377.56876093012880.0000113513890616.5699864
3012855.6299813513890510.56002783010638.1862535313887599.6249048
3010565.5620549513887504.2878251
#Sta/Elev= 30
       0  142.46   49.88  141.21   69.84  144.98    84.8   140.2  750.95   140.2
  982.68  137.95 2040.18  138.82 2086.56  137.25 2109.26   134.7 2114.39  130.14
 2118.35  130.16 2123.26  134.05  2158.5  139.86 2258.87  135.63 2283.87  137.66
 2333.86  124.94 2363.85  127.52 2408.84  137.89 2428.84  136.12  2653.8  139.67
 3090.24  137.02 3527.99  143.19 3998.55  140.48 5008.35  142.59 5053.35  139.84
  5268.3   143.3 5757.22  143.15  5813.2  137.25 5928.37  140.27 5958.04  141.13
#Mann= 9 ,-1 , 0
       0     .07       0  750.95     .08       0 2040.18     .05       0
  2158.5     .04       0 2408.84     .08       0 3090.24     .07       0
 3527.99     .15       0 5757.22     .07       0 5928.37     .12       0
#XS Ineff= 1 ,-1
       0  750.95  139.73
Permanent Ineff=
       F
#Block Obstruct= 1 ,-1
 5757.22 5958.04   142.5
Bank Sta=2040.18,2408.84
XS Rating Curve= 0 ,0
Exp/Cntr=0.3,0.1

Type RM Length L Ch R = 1 ,85584.03,627.62,936.74,990.56
XS GIS Cut Line= 6
3016453.4164209413891500.65614473013160.25994952 13889915.940154
3013053.0298490213889900.09996263012609.6252240213889854.0587161
3010695.3741312813887573.67121653010632.75811477 13887499.078846
#Sta/Elev= 30
       0  139.83   524.3  139.87  594.94  132.03  699.93  131.72 1034.89  131.77
 1109.88  138.47 1949.79  139.65 2014.78  137.66 2074.78  127.77 2124.77  125.84
 2259.76  128.22 2319.75  138.21 2464.74  139.52 3493.87  137.84 3644.62   138.1
 3695.46  128.29 3711.31  134.64 3763.01  138.53 3901.71   137.4 3961.14  124.14
 4030.49  137.66 4759.92  138.63 4966.14   142.3 6386.83  139.95 6556.67  143.62
 6646.59  140.66 7096.81  142.44 7141.14  137.61  7260.2     140 7283.49  141.52
#Mann= 10 ,-1 , 0
       0     .15       0   524.3     .07       0 3493.87     .12       0
 3644.62     .05       0 3763.01     .04       0 4030.49     .08       0
 4759.92     .07       0 4966.14     .15       0 7096.81     .07       0
  7260.2     .12       0
#XS Ineff= 2 ,-1
       0 2464.74  139.52 4703.35 7283.49  139.86
Permanent Ineff=
       F       F
#Block Obstruct= 4 ,-1
       0  214.98  141.78  534.94 1109.88  137.47 2014.78 2319.75  137.66
 6956.31 7283.49   142.5
Bank Sta=3644.62,4030.49
XS Rating Curve= 0 ,0
Exp/Cntr=0.5,0.3

Type RM Length L Ch R = 1 ,84647.29,104.07,121.35,114.64
BEGIN DESCRIPTION:
Upstream Section - CROSSING "A"
END DESCRIPTION:
XS GIS Cut Line= 6
3016864.1304945213890977.79137683014058.6758036213889673.4868988
 3013767.818117613889496.12472073013458.5149304413889407.6344121
3013184.8356877713889037.49440433011014.3275616213887661.6851481
#Sta/Elev= 30
       0   139.5  193.81  139.36  912.69  140.41 1019.18  132.59 1164.06  132.15
 1204.03  138.15 1253.99  139.13 2313.14  139.03 2378.09  138.22 2463.02  125.98
 2527.97  138.08  2617.9  138.97 3662.39  135.48 3775.96  137.34  3847.8  134.39
 3891.78  126.66  3916.5  133.28 3965.96  133.94 4035.19  133.28  4079.7  123.39
 4146.05  137.22  4767.1     138 5021.34  140.39 5131.33  136.59 5225.87  140.53
  5687.2   142.5 5809.29  141.83 6322.56  143.87 6557.86  141.48 6791.18  142.63
#Mann= 13 ,-1 , 0
       0     .07       0  193.81     .15       0  912.69     .07       0
 3662.39     .12       0 3775.96     .05       0 3965.96     .04       0
 4146.05     .08       0  4767.1     .07       0 5225.87     .15       0
  5687.2     .07       0 5809.29     .15       0 6322.56     .07       0
 6557.86     .15       0
#XS Ineff= 5 ,-1
       0 2527.97  138.08 2932.64 3888.78   136.9 4086.95 4146.05  133.55
 4146.05 5021.34   136.9 5021.34 6761.18  139.44
Permanent Ineff=
       F       F       F       F       F
#Block Obstruct= 2 ,-1
       0 1253.99  139.13 2378.09 2527.97  137.08
Bank Sta=3775.96,4146.05
XS Rating Curve= 0 ,0
Exp/Cntr=0.5,0.3

Type RM Length L Ch R = 2 ,84586.75,,,
BEGIN DESCRIPTION:
CROSSING "A"
END DESCRIPTION:
Node Name=CROSSING "A"
Bridge Culvert--1,0,-1,-1, 0
Deck Dist Width WeirC Skew NumUp NumDn MinLoCord MaxHiCord MaxSubmerge Is_Ogee
50.5,20,2.6,0, 60, 60, , , 0.98, 0, 2.5,2.5,,
 2962.62  2987.6 3002.59 3012.58 3032.56 3047.55 3061.44 3089.23 3123.09 3132.84
 3142.58 3186.54 3206.48 3221.42 3281.22 3321.08 3336.03    3346 3419.98 3439.25
 3443.78 3461.88 3484.95 3544.05 3558.12 3572.19 3605.02 3619.32 3648.17 3662.59
  3672.2 3700.94 3710.34 3724.44 3738.53 3752.63  3771.3 3818.53 3838.05 3857.56
 3867.32 3881.95  3970.9 3985.74 4015.41 4064.86 4093.92 4098.66 4141.31 4155.53
 4174.38 4179.08 4193.19  4207.3 4236.41 4246.41 4251.41 4261.41 4276.41 4286.41
  136.27  137.77  138.82  139.35  139.65  139.66  139.52  139.64  139.57  139.64
  139.56  139.93  139.67  139.82  139.56  139.78  139.77  139.66  139.74  139.64
  139.71  139.59  139.77  139.64   139.4  139.58  139.46  139.31  139.51  139.45
  139.54  139.56  139.43  139.55  139.78   139.6  139.93   136.9   136.9  138.01
  139.22  139.56  139.87  139.84  139.49  133.55  133.55  134.03  139.18  139.63
  139.62  139.75  139.63  139.66  139.54  139.68  139.42  138.59   137.1  136.86
       0       0       0       0       0       0       0       0       0       0
       0       0       0       0       0       0       0       0       0       0
       0       0       0       0       0       0       0       0       0       0
       0       0       0       0       0       0       0       0       0       0
       0       0       0       0       0       0       0       0       0       0
       0       0       0       0       0       0       0       0       0       0
 2962.62  2987.6 3002.59 3012.58 3032.56 3047.55 3061.44 3089.23 3123.09 3132.84
 3142.58 3186.54 3206.48 3221.42 3281.22 3321.08 3336.03    3346 3419.98 3439.25
 3443.78 3461.88 3484.95 3544.05 3558.12 3572.19 3605.02 3619.32 3648.17 3662.59
  3672.2 3700.94 3710.34 3724.44 3738.53 3752.63  3771.3 3818.53 3838.05 3857.56
 3867.32 3881.95  3970.9 3985.74 4015.41 4064.86 4093.92 4098.66 4141.31 4155.53
 4174.38 4179.08 4193.19  4207.3 4236.41 4246.41 4251.41 4261.41 4276.41 4286.41
  136.27  137.77  138.82  139.35  139.65  139.66  139.52  139.64  139.57  139.64
  139.56  139.93  139.67  139.82  139.56  139.78  139.77  139.66  139.74  139.64
  139.71  139.59  139.77  139.64   139.4  139.58  139.46  139.31  139.51  139.45
  139.54  139.56  139.43  139.55  139.78   139.6  139.93   136.9   136.9  138.01
  139.22  139.56  139.87  139.84  139.49  133.55  133.55  134.03  139.18  139.63
  139.62  139.75  139.63  139.66  139.54  139.68  139.42  138.59   137.1  136.86
       0       0       0       0       0       0       0       0       0       0
       0       0       0       0       0       0       0       0       0       0
       0       0       0       0       0       0       0       0       0       0
       0       0       0       0       0       0       0       0       0       0
       0       0       0       0       0       0       0       0       0       0
       0       0       0       0       0       0       0       0       0       0
BR Coef=-1 , 0 , 0 ,, 0 ,,,0.8,-1,,0,
WSPro=,,,, 1 ,,,, 0 ,,,, 0 ,,,,-1 ,-1 ,-1 , 0 , 0 , 0 , 0 , 0
Culvert=1,4,,73.5,0.024,0.7,1,2,2,125.96,3891.78,125.91,3867.32,Culvert #1  , 0 ,25
Culvert Bottom n=0.024
Multiple Barrel Culv=1,4.5,,73.5,0.024,0.7,1,2,2,123.49,123.53, 2,Culvert #2  , 0 ,25
  4076.7  4076.7  4083.7  4083.7
Culvert Bottom n=0.024
BC Design=,, 0 ,, 0 ,,,,,,
BC Use User HTab Curves=0
BC User HTab FreeFlow(D)= 0

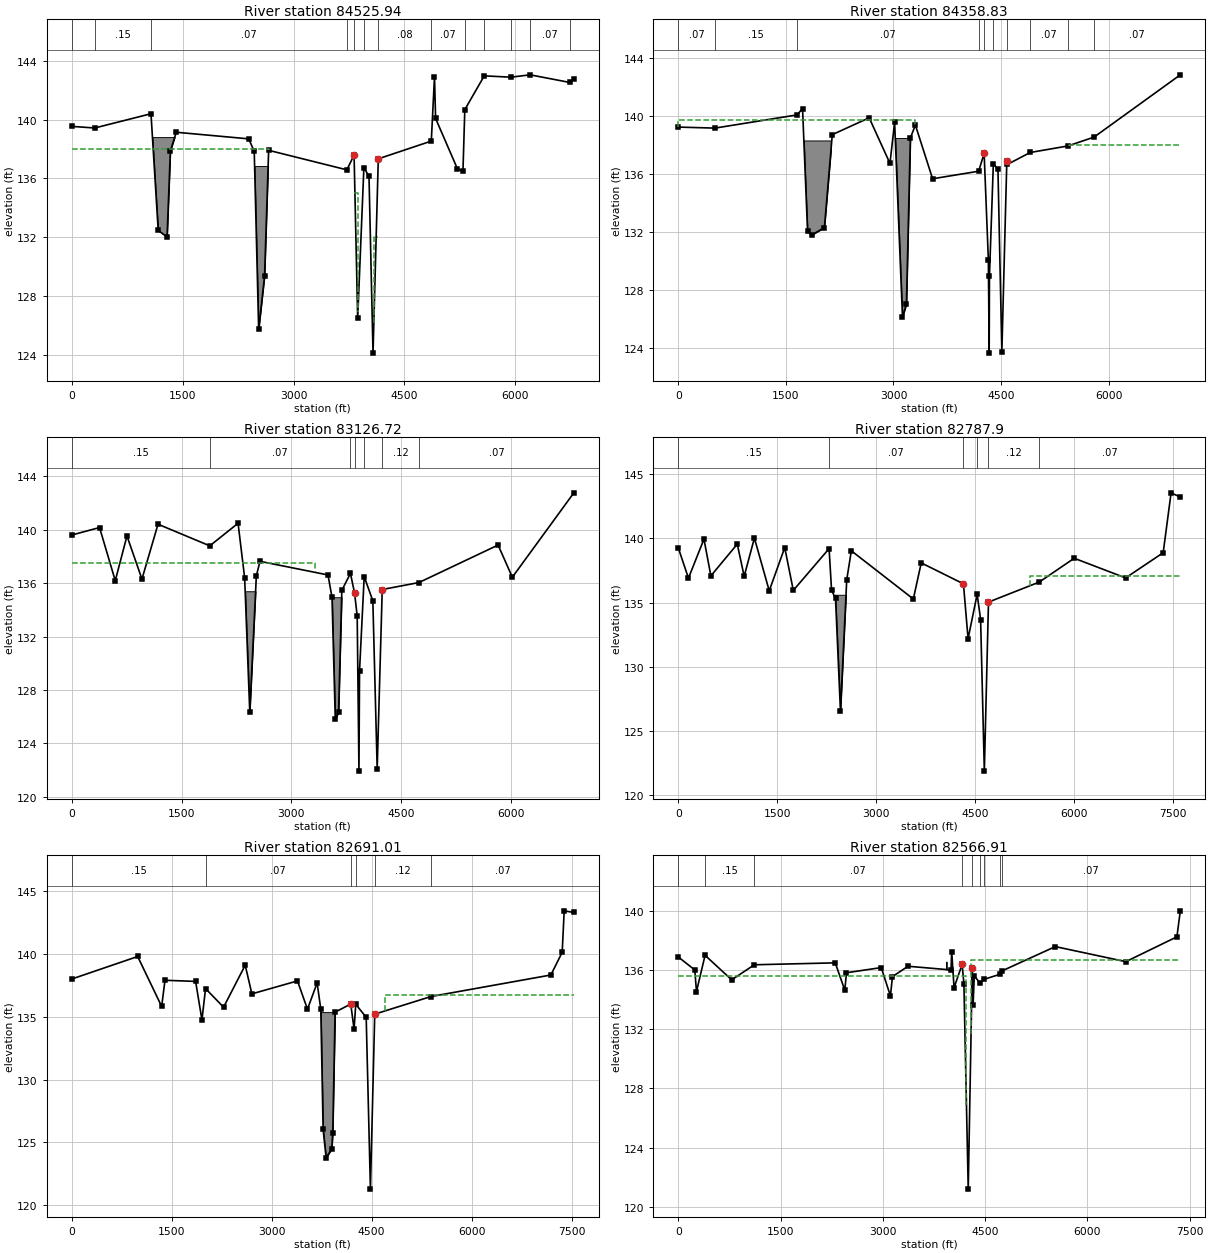
Type RM Length L Ch R = 1 ,84525.94,65.12,167.11,174.4
BEGIN DESCRIPTION:
Downstream Section - CROSSING "A"
END DESCRIPTION:
Node Name=Y
XS GIS Cut Line= 6
 3016975.4163612 13890929.5247413014169.96167028 13889625.220263
3013879.1039842813889447.8580849 3013569.800797113889359.3677763
3013296.1215544513888989.22776863011125.6134282813887613.4185124
#Sta/Elev= 30
       0  139.54  309.93  139.43 1071.62   140.4 1169.06  132.46 1288.96  132.01
 1333.93  137.88 1413.86  139.14 2393.08  138.69 2468.02  137.84 2527.97  125.71
  2607.9  129.36 2662.86  137.91 3721.14  136.58 3818.53  137.59 3867.32  126.46
 3951.12  136.73 4020.36  136.14 4074.76   124.1 4146.05  137.33 4863.18  138.54
 4906.35  142.92 4921.35  140.08 5216.32  136.65 5291.32  136.49 5316.23  140.68
 5579.38  142.98 5941.05  142.89 6200.19  143.05 6737.04  142.53 6791.18  142.78
#Mann= 13 ,-1 , 0
       0     .07       0  309.93     .15       0 1071.62     .07       0
 3721.14     .12       0 3818.53     .05       0 3951.12     .04       0
 4146.05     .08       0 4863.18     .07       0 5316.23     .15       0
 5579.38     .07       0 5941.05     .15       0 6200.19     .07       0
 6737.04     .15       0
#XS Ineff= 5 ,-1
       0 2662.86  138.03 3812.61 3865.32     135 4085.95 4146.05     132
 4146.05 4906.35     137 4906.35 6791.18     138
Permanent Ineff=
       F       F       F       F       F
#Block Obstruct= 2 ,-1
 1071.62 1413.86  138.81 2468.02 2667.86  136.84
Bank Sta=3818.53,4146.05
XS Rating Curve= 0 ,0
Exp/Cntr=0.5,0.3

Type RM Length L Ch R = 1 ,84358.83,1201.93,1232.11,1239
XS GIS Cut Line= 6
3017586.8728154513890899.63733363014045.6085725313889465.3823281
3013656.4827103613889262.04415213013480.3551098613888941.8125091
3013076.6269146913888442.27216963011543.1667270213887637.0306699
#Sta/Elev= 30
       0  139.22   511.3  139.15 1657.51  140.06 1733.04   140.5 1802.96  132.03
  1857.9  131.78  2037.7   132.3 2147.57   138.7 2661.99  139.86 2951.66  136.72
 3016.58  139.55 3126.46  126.12  3181.4  127.05 3236.33  138.47 3306.25  139.36
 3545.98  135.66 4188.08  136.18 4264.66  137.41 4323.54  130.08 4334.81  123.65
 4338.72  128.96 4393.07  136.71 4457.28   136.3  4511.6  123.75 4580.75  136.85
 4589.71  136.65  4906.4  137.47 5432.51  137.92 5796.98  138.53 6999.56  142.82
#Mann= 10 ,-1 , 0
       0     .07       0   511.3     .15       0 1657.51     .07       0
 4188.08     .12       0 4264.66     .05       0 4393.07     .04       0
 4589.71     .08       0  4906.4     .07       0 5432.51     .08       0
 5796.98     .07       0
#XS Ineff= 2 ,-1
       0 3306.25  139.68 5447.19 6999.56     138
Permanent Ineff=
       F       F
#Block Obstruct= 2 ,-1
 1728.05 2127.59   138.3 3016.58 3236.33  138.47
Bank Sta=4264.66,4580.75
XS Rating Curve= 0 ,0
Exp/Cntr=0.3,0.1

Type RM Length L Ch R = 1 ,83126.72,260.03,338.82,348.64
XS GIS Cut Line= 6
3017644.8162691113890687.74405663014718.39987786 13888536.860235
 3014541.499969213888370.58005583014450.4499544513888255.5599446
3014285.6494310213888092.30010053011711.7277416113887665.1119785
#Sta/Elev= 30
       0  139.61  379.67  140.17  594.48  136.19  754.34  139.54  959.16  136.31
 1178.97  140.42 1886.12   138.8 2273.01  140.49 2362.93   136.4 2432.87  126.35
 2522.79  136.56 2572.75  137.64 3501.93  136.62 3556.88  134.95 3601.84  125.81
 3646.68  126.36 3691.27  135.47 3808.81  136.74 3864.69  135.28 3901.12  133.56
 3925.26  121.93  3933.1  129.44 3996.84   136.5 4115.07  134.68 4174.29  122.12
  4243.4  135.53 4744.13  136.05 5826.88  138.86 6021.57  136.45 6862.36  142.77
#Mann= 7 ,-1 , 0
       0     .15       0 1886.12     .07       0 3808.81     .12       0
 3864.69     .05       0 3996.84     .04       0  4243.4     .12       0
 4744.13     .07       0
#XS Ineff= 2 ,-1
       0 3322.09  137.48 5297.35 6862.36  137.48
Permanent Ineff=
       F       F
#Block Obstruct= 2 ,-1
 2362.93 2522.79   135.4 3556.88 3691.27  134.95
Bank Sta=3864.69,4243.4
XS Rating Curve= 0 ,0
Exp/Cntr=0.3,0.1

Type RM Length L Ch R = 1 ,82787.9 ,80.47,96.9,97.27
Node Name=X
XS GIS Cut Line= 5
3018415.7097404513890501.52658133014873.4717461913888441.5261081
3014570.7453175313887878.34055473014356.6788165313887807.7045411
3011714.6903341113887645.0765855
#Sta/Elev= 30
       0  139.27  154.91   136.9  389.78  139.94  494.72  137.08  894.49  139.55
  999.44  137.05 1154.35  140.02 1379.22  135.92 1614.09  139.28 1744.02  135.95
 2286.32   139.2 2323.69  135.97 2383.66  135.32 2458.62  126.55 2553.56  136.77
 2623.52  139.03    3563  135.28 3682.93  138.09 4322.48  136.46 4392.69  132.19
 4530.38  135.65 4582.81  133.68  4639.2  121.89 4702.12  135.04 5472.59   136.6
 6001.29  138.45 6780.37  136.92  7349.7  138.88 7469.56  143.54  7609.4  143.21
#Mann= 6 ,-1 , 0
       0     .15       0 2286.32     .07       0 4322.48     .05       0
 4530.38     .04       0 4702.12     .12       0 5472.59     .07       0
#XS Ineff= 2 ,-1
       0 3682.93  137.05 5337.07  7609.4  137.05
Permanent Ineff=
       F       F
#Block Obstruct= 1 ,-1
 2363.67 2553.56  135.61
Bank Sta=4322.48,4702.12
XS Rating Curve= 0 ,0
Exp/Cntr=0.3,0.1

Type RM Length L Ch R = 1 ,82691.01,305.62,124.09,73.37
XS GIS Cut Line= 5
3018557.9847183713890048.54356343014870.5265421113888286.6510898
 3014663.922624613887842.35506243014359.1807800213887780.5103698
3011716.17163037 13887635.058889
#Sta/Elev= 30
       0  137.99  989.21  139.78 1348.93  135.81 1398.89  137.89 1858.52   137.8
 1953.45  134.74 2007.62  137.23 2278.19  135.75 2602.94  139.09 2702.86  136.81
 3387.33  137.84 3537.21  135.59  3682.1  137.68 3737.06   135.6 3772.03  126.04
    3817  123.78 3901.93  124.49 3916.92  125.78 3951.89  135.36 4186.78     136
 4236.78     134 4261.78  135.98 4418.44  134.95 4481.98  121.29 4546.77   135.2
 5392.21   136.6 7190.21  138.31 7360.03  140.12    7390  143.41 7534.84  143.28
#Mann= 6 ,-1 , 0
       0     .15       0 2007.62     .07       0 4186.78     .05       0
 4261.78     .04       0 4546.77     .12       0 5392.21     .07       0
#XS Ineff= 2 ,-1
       0  3682.1  136.71 4698.08 7534.84  136.71
Permanent Ineff=
       F       F
#Block Obstruct= 1 ,-1
 3737.06 3951.89  135.36
Bank Sta=4186.78,4546.77
XS Rating Curve= 0 ,0
Exp/Cntr=0.5,0.3

Type RM Length L Ch R = 1 ,82566.91,155.11,217.82,219.42
BEGIN DESCRIPTION:
Upstream Section - LONGENBAUGH ROAD
END DESCRIPTION:
XS GIS Cut Line= 6
3018966.5708434413888586.83684113018482.5691867813888480.9197301
3017405.9676654513888116.24263793015290.3049020313888011.6660754
3014270.0136355313887719.38811673011731.7283577813887607.8414238
#Sta/Elev= 30
       0   136.9  242.71  136.02  267.47  134.56  393.45  137.01  783.98  135.35
 1116.02  136.37 2302.69   136.5 2442.56  134.65 2467.53  135.83 2977.04  136.18
 3111.91  134.26 3141.88  135.57 3369.98  136.27 4000.55  136.02 4010.38  137.26
  4044.8  134.82 4163.07  136.39 4189.43  135.09 4252.86  121.19 4311.93  136.16
 4323.89  133.63 4341.46  135.63 4425.89  135.12 4488.07  135.39 4713.85  135.72
 4750.79  135.96 5529.86   137.6 6563.42  136.58 7313.09  138.26 7363.09  140.02
#Mann= 9 ,-1 , 0
       0     .07       0  393.45     .15       0 1116.02     .07       0
 4163.07     .04       0 4311.93     .07       0 4425.89     .12       0
 4488.07     .07       0 4713.85     .12       0 4750.79     .07       0
#XS Ineff= 2 ,-1
       0 4226.93  135.61 4294.35 7363.09  136.71
Permanent Ineff=
       F       F
#Block Obstruct= 1 ,-1
 3926.94  3938.5136.5773
Bank Sta=4163.07,4311.93
XS Rating Curve= 0 ,0
Exp/Cntr=0.5,0.3