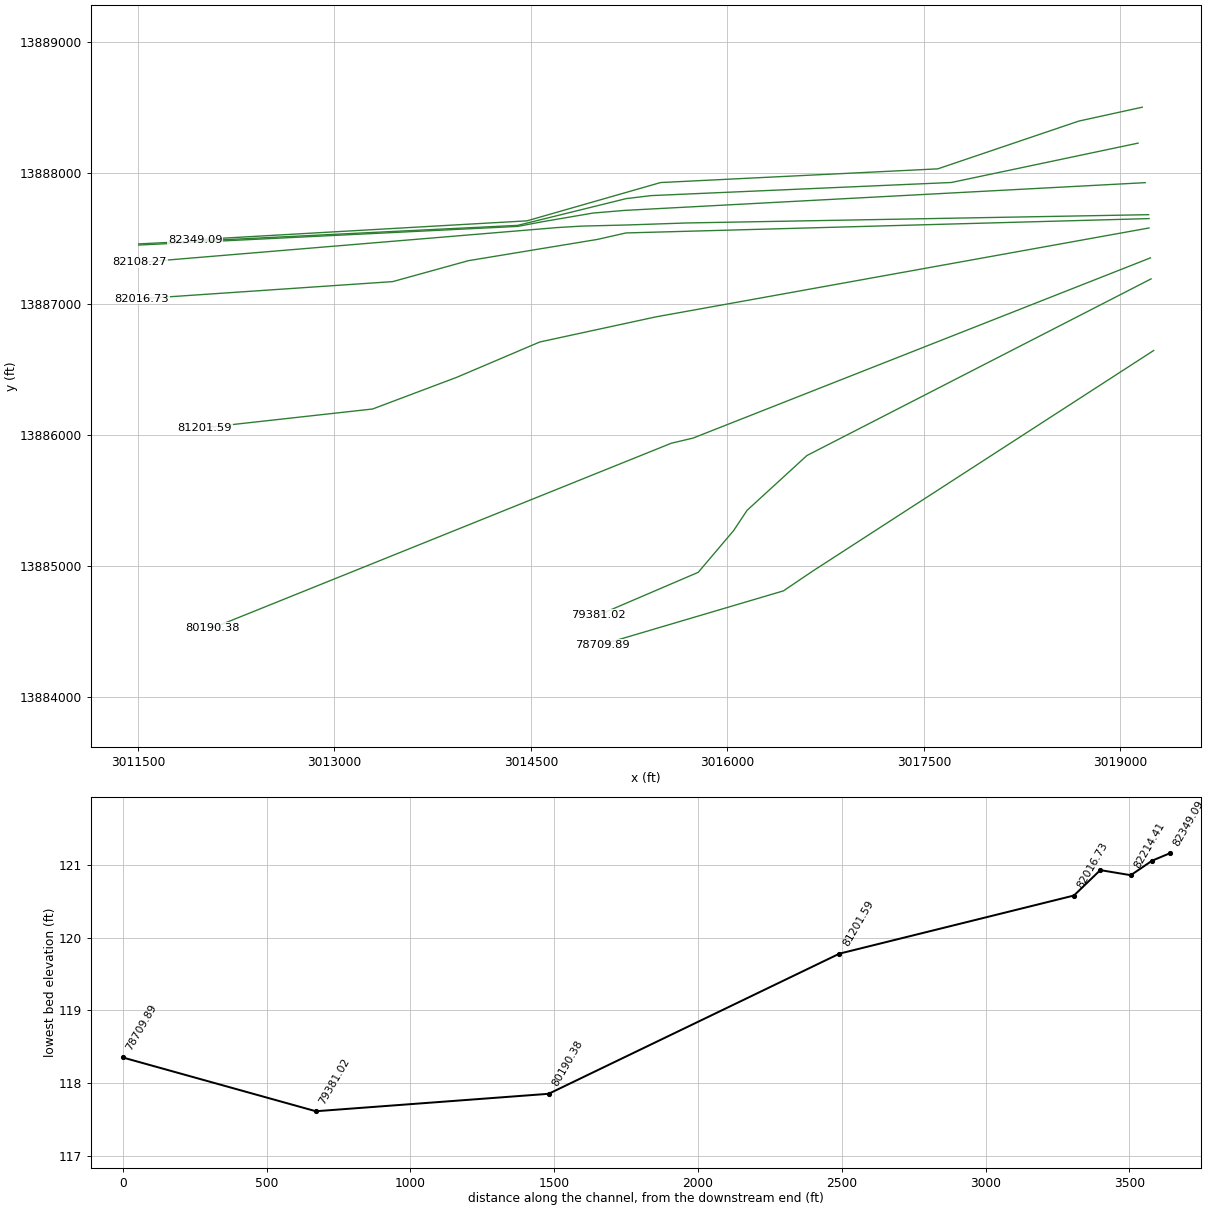
HEC-RAS study U100-00-00.prj: U100-00-00

--- U100-00-00.g01 (geometry) --- (continued)

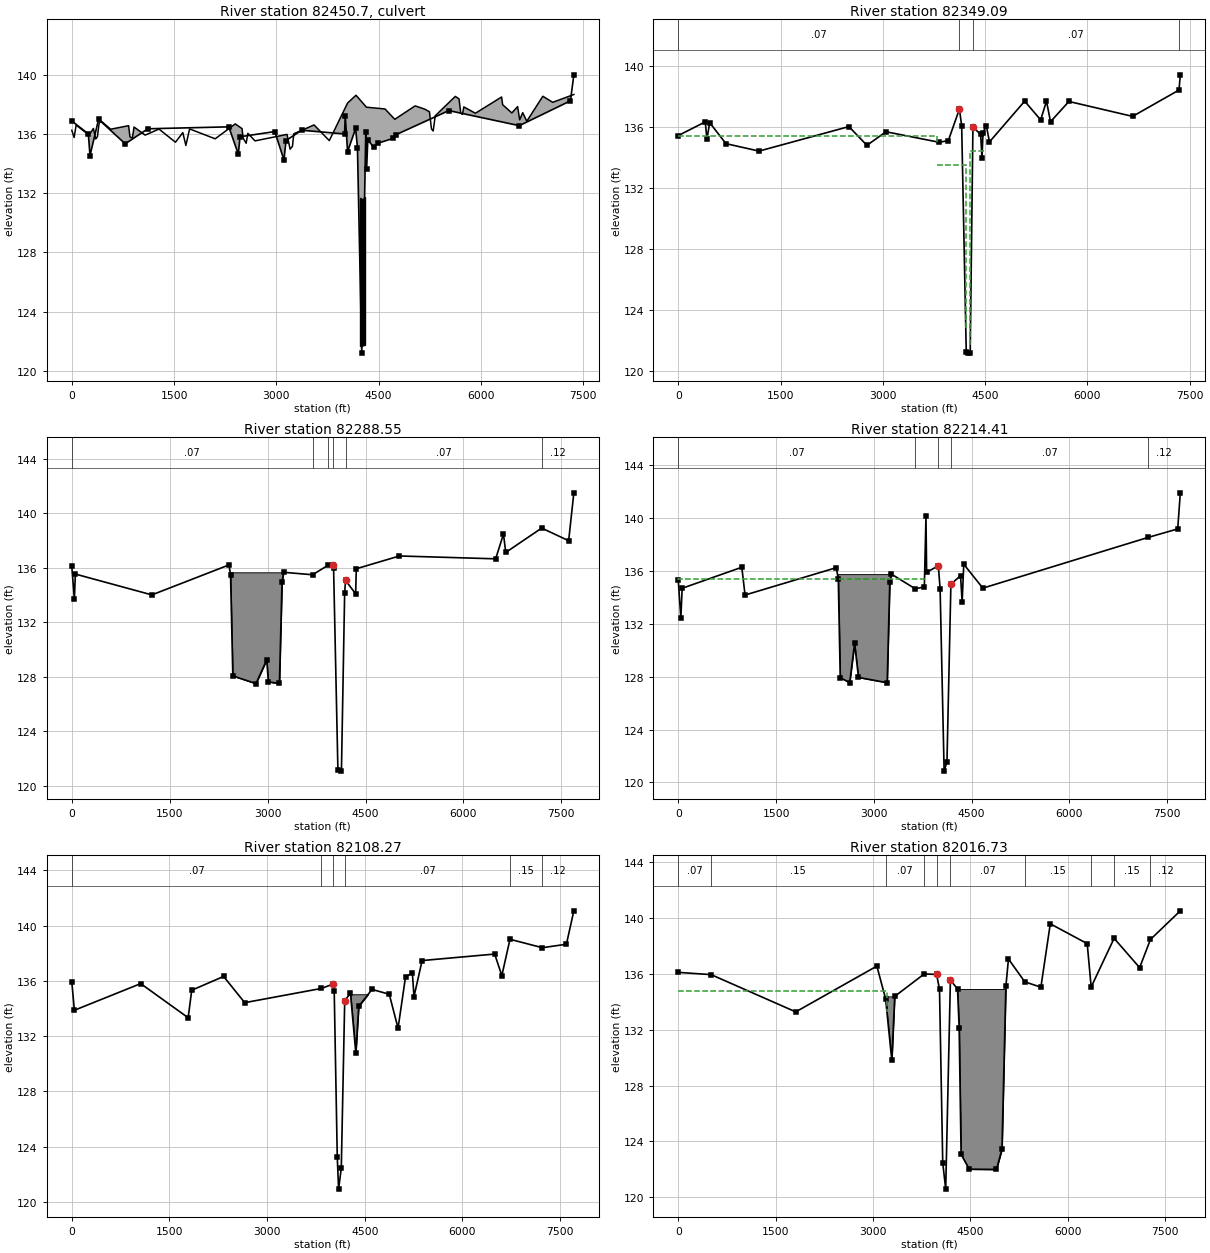
Type RM Length L Ch R = 2 ,82450.7 ,,,
BEGIN DESCRIPTION:
LONGENBAUGH ROAD
U00_1300
END DESCRIPTION:
Node Name=LONGENBAUGH
Bridge Culvert--1,0,-1,-1, 0
Deck Dist Width WeirC Skew NumUp NumDn MinLoCord MaxHiCord MaxSubmerge Is_Ogee
30,168,2.6,0, 60, 60, , , 0.98, 0, 0,0,,
       0   34.67   64.39  252.61     317  351.68  376.47   401.3  436.06  570.22
   833.7  853.58  888.38  913.24 1076.18 1278.91 1520.75 1628.53  1673.3 1728.24
 2102.89  2397.6  2497.5 2512.49 2557.45 2582.42 2687.32 3156.87 3201.83 3236.45
 3256.23 3552.97 3776.68  4044.8 4167.74 4321.77 4593.89 4737.18 5035.51 5175.33
 5245.31  5275.3 5300.29 5330.28 5624.66 5679.54 5704.48 5729.43 5749.39 5919.18
 6303.73 6318.71 6453.55 6538.45 6568.42 6613.36 6673.34 6908.24 7053.19 7363.07
  136.27  135.78  136.62  135.95  136.39  135.68  135.84  136.77  136.87  136.34
  136.58  135.82  135.74  136.49  135.94  136.35  135.46  136.11  135.24  136.36
  135.69   136.7  136.38  135.74  135.39  136.06  135.55  135.99  134.99  135.18
  136.03  136.63  135.57  138.11  138.64  137.83  137.71  137.01  137.92   137.7
  137.52  136.36  136.22  137.25  138.56  138.39  137.43  137.34  137.85  137.42
  138.52     138  137.44  137.87  136.98  137.46  136.88  138.57  138.16  138.69
       0       0       0       0       0       0       0       0       0       0
       0       0       0       0       0       0       0       0       0       0
       0       0       0       0       0       0       0       0       0       0
       0       0       0       0       0       0       0       0       0       0
       0       0       0       0       0       0       0       0       0       0
       0       0       0       0       0       0       0       0       0       0
       0   34.67   64.39  252.61     317  351.68  376.47   401.3  436.06  570.22
   833.7  853.58  888.38  913.24 1076.18 1278.91 1520.75 1628.53  1673.3 1728.24
 2102.89  2397.6  2497.5 2512.49 2557.45 2582.42 2687.32 3156.87 3201.83 3236.45
 3256.23 3552.97 3776.68  4044.8 4167.74 4321.77 4593.89 4737.18 5035.51 5175.33
 5245.31  5275.3 5300.29 5330.28 5624.66 5679.54 5704.48 5729.43 5749.39 5919.18
 6303.73 6318.71 6453.55 6538.45 6568.42 6613.36 6673.34 6908.24 7053.19 7363.07
  136.27  135.78  136.62  135.95  136.39  135.68  135.84  136.77  136.87  136.34
  136.58  135.82  135.74  136.49  135.94  136.35  135.46  136.11  135.24  136.36
  135.69   136.7  136.38  135.74  135.39  136.06  135.55  135.99  134.99  135.18
  136.03  136.63  135.57  138.11  138.64  137.83  137.71  137.01  137.92   137.7
  137.52  136.36  136.22  137.25  138.56  138.39  137.43  137.34  137.85  137.42
  138.52     138  137.44  137.87  136.98  137.46  136.88  138.57  138.16  138.69
       0       0       0       0       0       0       0       0       0       0
       0       0       0       0       0       0       0       0       0       0
       0       0       0       0       0       0       0       0       0       0
       0       0       0       0       0       0       0       0       0       0
       0       0       0       0       0       0       0       0       0       0
       0       0       0       0       0       0       0       0       0       0
BR Coef=-1 , 0 , 0 ,, 0 ,,,0.8,-1,,0,
WSPro=,,,, 1 ,,,, 0 ,,,, 0 ,,,,-1 ,-1 ,-1 , 0 , 0 , 0 , 0 , 0
Culvert=2,10,11,168,0.015,0.5,1,8,1,121.67,4232.43,121.22,4222.54,Culvert #1  , 0 ,30
Culvert Bottom n=0.015
Culvert=2,10,11,168,0.015,0.5,1,8,1,121.64,4252.86,121.32,4241.49,Culvert #2  , 0 ,30
Culvert Bottom n=0.015
Culvert=2,10,11,168,0.015,0.5,1,8,1,121.7,4270.58,121.26,4259.08,Culvert #3  , 0 ,30
Culvert Bottom n=0.015
Culvert=2,10,11,168,0.015,0.5,1,8,1,121.73,4288.85,121.29,4277.63,Culvert #4  , 0 ,30
Culvert Bottom n=0.015
BC Design=,, 0 ,, 0 ,,,,,,
BC Use User HTab Curves=0
BC User HTab FreeFlow(D)= 0

Type RM Length L Ch R = 1 ,82349.09,56.79,60.55,52.45
BEGIN DESCRIPTION:
Downstream Section - LONGENBAUGH ROAD
END DESCRIPTION:
XS GIS Cut Line= 6
3019166.2535149513888501.69167023018682.2518582813888395.7745592
3017605.65033695 13888031.0974673015489.9875735313887926.5209045
3014469.6963070313887634.24294583011936.3526204413887489.7635759
#Sta/Elev= 30
       0  135.45  396.33  136.35  421.16  135.21  460.89   136.3  699.47  134.92
 1184.89  134.43  2502.5  136.04 2767.24  134.81 3046.98   135.7 3826.51  135.01
 3961.08  135.12 4123.48  137.19 4156.64   136.1  4223.9  121.22 4252.86  121.16
 4281.77  121.19 4321.77  136.01 4434.99  135.53 4454.68  133.95 4469.44  135.65
 4519.22  136.09 4564.02  135.03 5080.43  137.71 5315.29  136.48 5400.14  137.71
 5460.01  136.36 5729.43  137.69 6663.34  136.71 7343.65  138.44 7363.09  139.44
#Mann= 4 ,-1 , 0
       0     .07       0 4123.48     .04       0 4321.77     .07       0
 7343.65     .12       0
#XS Ineff= 4 ,-1
       0 3791.63  135.41 3791.63 4217.04  133.53 4283.13 4494.33  134.41
 4494.33 7363.09  135.49
Permanent Ineff=
       F       F       F       F
Bank Sta=4123.48,4321.77
XS Rating Curve= 0 ,0
Exp/Cntr=0.5,0.3

Type RM Length L Ch R = 1 ,82288.55,78.52,74.13,51.92
Node Name=W
XS GIS Cut Line= 6
3019134.2037102713888227.4609194 3017709.027098713887927.0182789
3015417.1885065313887826.87051333015226.5232054413887803.7596671
 3014399.557339713887599.76007513011506.2826144413887458.3381139
#Sta/Elev= 30
       0  136.11    39.9   133.7   54.87  135.54 1227.05  134.01 2407.37  136.21
 2432.34   135.5 2467.29  128.06  2821.8  127.49 2986.57  129.24 3011.54  127.62
  3181.3   127.5 3221.25  134.95 3246.21  135.67 3689.02  135.49 3920.57  136.17
 3996.87   136.2 4010.88  135.99  4077.2  121.14 4131.23  121.06 4180.39  134.15
 4194.28  135.07 4348.88  134.09 4358.87  135.93 5019.68  136.87 6493.65  136.66
 6613.56  138.48 6648.54  137.13 7199.33  138.92 7612.09  137.99 7691.64  141.51
#Mann= 6 ,-1 , 0
       0     .07       0 3689.02     .12       0 3920.57     .07       0
 3996.87     .04       0 4194.28     .07       0 7199.33     .12       0
#XS Ineff= 2 ,-1
       0 3996.87   135.5 4388.84 7691.64   135.5
Permanent Ineff=
       F       F
#Block Obstruct= 1 ,-1
 2407.37 3246.21  135.67
Bank Sta=3996.87,4194.28
XS Rating Curve= 0 ,0
Exp/Cntr=0.3,0.1

Type RM Length L Ch R = 1 ,82214.41,109.24,106.14,100.71
XS GIS Cut Line= 6
3019188.8630497813887925.67379333015214.6544627713887713.9412772
3014973.4915592813887693.56139673014587.2895757713887627.4119227
3014399.6492030313887591.93791233011506.8180464513887449.4546014
#Sta/Elev= 30
       0  135.33      40  132.42      60  134.69  974.96  136.28 1024.96  134.18
  2424.9  136.25  2454.9  135.38  2484.9  127.93 2629.89  127.55 2704.89  130.52
 2764.88  127.95 3204.86  127.55 3244.86  135.15 3269.86  135.76 3636.28  134.65
 3774.83   134.8 3799.83  140.12 3809.83   135.9  3989.7  136.39 4016.82  134.64
 4078.28  120.86 4121.98  121.58 4182.33     135  4330.2  135.64 4354.82  133.64
 4379.45  136.51 4672.44   134.7 7208.88  138.54 7661.31  139.18 7701.05  141.91
#Mann= 5 ,-1 , 0
       0     .07       0 3636.28     .12       0  3989.7     .04       0
 4182.33     .07       0 7208.88     .12       0
#XS Ineff= 2 ,-1
       0 3779.83  135.39 4285.87 7701.05  135.39
Permanent Ineff=
       F       F
#Block Obstruct= 1 ,-1
  2424.9 3269.86  135.76
Bank Sta=3989.7,4182.33
XS Rating Curve= 0 ,0
Exp/Cntr=0.3,0.1

Type RM Length L Ch R = 1 ,82108.27,69.13,91.55,99.08
XS GIS Cut Line= 6
 3019214.563129613887681.29993833015694.5399859413887618.1799858
3015237.5500862713887602.78992473014886.8916668613887594.0773437
3014703.7926236113887583.14593513011514.7747234413887317.4857053
#Sta/Elev= 30
       0  135.96   39.95  133.88 1058.67  135.81 1787.76  133.34 1842.69  135.33
 2332.07  136.33 2656.67  134.43 3833.78  135.46 4016.65  135.78  4031.2  135.27
 4077.96  123.29 4098.36  120.93 4139.84  122.44 4192.51  134.58 4280.56  135.11
 4363.33  130.78 4407.94  134.17    4612  135.39 4876.85  135.04 5011.77  132.58
 5126.71   136.3 5231.65  136.58 5256.64  134.87 5381.57  137.48 6495.95  137.95
 6605.89  136.39 6731.13  139.02 7228.04  138.41 7597.74  138.66 7712.05  141.08
#Mann= 6 ,-1 , 0
       0     .07       0 3833.78     .12       0 4016.65     .04       0
 4192.51     .07       0 6731.13     .15       0 7228.04     .12       0
#XS Ineff= 2 ,-1
       0 3440.69  135.04 4876.85 7712.05  135.04
Permanent Ineff=
       F       F
#Block Obstruct= 1 ,-1
 4280.56 4876.85  135.04
Bank Sta=4016.65,4192.51
XS Rating Curve= 0 ,0
Exp/Cntr=0.3,0.1

Type RM Length L Ch R = 1 ,82016.73,760.56,815.15,785.05
XS GIS Cut Line= 6
3019218.5933052713887651.47650713015225.4562784413887541.8546791
3015008.6309246913887492.68581423014022.4275165213887330.1188821
3013444.9952724413887170.47615683011531.48203911 13887040.378976
#Sta/Elev= 30
       0  136.11  505.55  135.95 1809.85  133.28 3059.72  136.56 3194.07  134.21
  3289.7  129.81  3334.7  134.39 3789.45     136 3979.63  135.96 4024.27   134.9
 4074.06  122.47 4119.81  120.58 4192.26  135.56 4301.92  134.92 4326.91  132.15
 4356.89  123.07 4481.83  122.01 4901.62  121.99 4986.58  123.44 5046.55   135.1
 5086.53  137.07 5338.26  135.43 5585.91  135.05 5730.69  139.59 6299.26  138.17
 6360.39  135.06 6713.51  138.55 7106.84  136.45 7273.59  138.47 7733.46  140.52
#Mann= 10 ,-1 , 0
       0     .07       0  505.55     .15       0 3194.07     .07       0
 3789.45     .12       0 3979.63     .04       0 4192.26     .07       0
 5338.26     .15       0 6360.39     .07       0 6713.51     .15       0
 7273.59     .12       0
#XS Ineff= 2 ,-1
       0 3214.71  134.75 5046.55 7733.46   135.1
Permanent Ineff=
       F       F
#Block Obstruct= 2 ,-1
 3214.71  3334.7  134.39 4301.92 5046.55  134.92
Bank Sta=3979.63,4192.26
XS Rating Curve= 0 ,0
Exp/Cntr=0.3,0.1

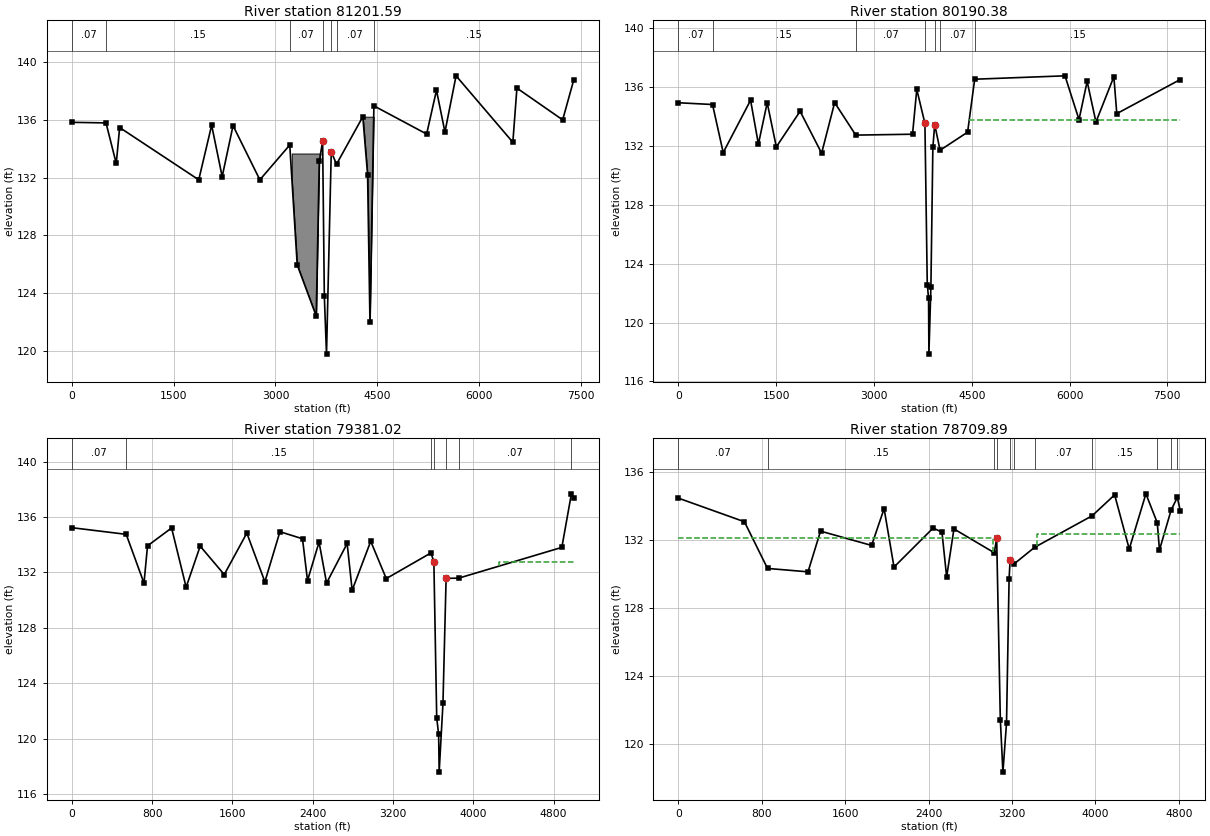
Type RM Length L Ch R = 1 ,81201.59,962.23,1011.21,970.93
XS GIS Cut Line= 6
3019217.5312995313887579.79882893015452.0499853613886900.9199374
3014567.6577252713886709.60503133013932.9027611913886439.5396265
3013291.4791752713886198.06012263012011.8833092713886056.0627032
#Sta/Elev= 30
       0  135.83  504.31  135.79  654.98  132.98  704.98  135.47 1869.93  131.85
 2059.92  135.63 2214.92  132.07 2374.91   135.6  2769.9  131.85  3210.2  134.26
 3319.87  125.96 3599.86  122.42 3644.86  133.12 3694.12  134.52 3719.36  123.79
 3751.26  119.78 3821.36  133.79  3898.8  132.93 4286.17  136.22 4356.16  132.21
 4391.15  122.03 4449.27  136.97 5225.94  135.02  5370.9  138.05 5495.38  135.16
 5659.27  139.05 6495.48  134.45 6555.36   138.2 7229.05     136 7393.72  138.79
#Mann= 7 ,-1 , 0
       0     .07       0  504.31     .15       0  3210.2     .07       0
 3694.12     .04       0 3821.36     .12       0  3898.8     .07       0
 4449.27     .15       0
#XS Ineff= 2 ,-1
       0  3210.2  134.26 4231.18 7393.72  134.32
Permanent Ineff=
       F       F
#Block Obstruct= 3 ,-1
       0 2804.89  131.98 3239.88 3664.75  133.67 4286.17 4451.14  136.22
Bank Sta=3694.12,3821.36
XS Rating Curve= 0 ,0
Exp/Cntr=0.3,0.1

Type RM Length L Ch R = 1 ,80190.38,769.32,809.36,850.23
XS GIS Cut Line= 4
 3019228.779964713887351.61326173015737.2000056113885975.9998712
3015571.8601131913885936.85985763012069.0803733613884526.0382042
#Sta/Elev= 30
       0  134.94  525.92  134.82  689.59  131.55 1109.35  135.11 1229.28  132.13
  1364.2  134.94 1504.11  131.94  1868.9  134.36  2198.7  131.51 2398.59  134.95
 2722.17  132.74 3592.88   132.8 3657.85  135.85 3782.77  133.53 3818.73  122.57
 3838.57  121.66 3843.77  117.85 3874.59  122.44  3904.5   131.9 3932.69  133.46
 4014.98  131.71 4437.19  132.94 4545.89  136.54 5930.73  136.77 6145.52  133.79
  6270.4  136.39 6405.27  133.63    6680  136.71 6724.96   134.2    7699  136.52
#Mann= 7 ,-1 , 0
       0     .07       0  525.92     .15       0 2722.17     .07       0
 3782.77     .04       0 3932.69     .12       0 4014.98     .07       0
 4545.89     .15       0
#XS Ineff= 2 ,-1
       0 3782.77  133.53 4462.17    7699  133.78
Permanent Ineff=
       F       F
Bank Sta=3782.77,3932.69
XS Rating Curve= 0 ,0
Exp/Cntr=0.3,0.1

Type RM Length L Ch R = 1 ,79381.02,693.32,671.13,647.25
XS GIS Cut Line= 6
3019233.7281175313887191.26482913016606.5647366913885842.8091927
3016149.7398629513885424.37006893016046.8998455313885269.6200504
3015777.3419856913884951.58853423015017.8667986113884626.0993558
#Sta/Elev= 30
       0  135.23  542.31  134.75  719.52  131.23  754.49  133.92  994.33  135.21
 1139.24  130.94 1279.14   133.9 1518.98  131.85 1743.83  134.84 1923.71  131.33
 2073.61  134.94 2298.46  134.43 2348.42  131.42 2463.35  134.19  2538.3  131.24
 2743.16  134.09 2793.13  130.72    2978  134.25 3132.87  131.56 3577.89  133.41
 3607.03  132.78 3635.49  121.51 3654.67  120.33 3659.82  117.61 3697.63  122.56
 3728.99  131.58 3853.38  131.59 4882.05  133.81 4977.12  137.67 5001.51  137.38
#Mann= 7 ,-1 , 0
       0     .07       0  542.31     .15       0 3577.89     .07       0
 3607.03     .04       0 3728.99     .12       0 3853.38     .07       0
 4977.12     .15       0
#XS Ineff= 2 ,-1
       0 3607.03  132.78 4259.85 5001.51  132.77
Permanent Ineff=
       F       F
Bank Sta=3607.03,3728.99
XS Rating Curve= 0 ,0
Exp/Cntr=0.3,0.1

Type RM Length L Ch R = 1 ,78709.89,726.7,725.19,705.72
XS GIS Cut Line= 4
3019253.3274877813886644.49459723016652.3901043513884961.8998653
3016427.5700159413884809.99006413015042.7601215213884400.4869461
#Sta/Elev= 30
       0  134.44  634.54  133.05  855.87  130.31 1244.09  130.11    1364   132.5
 1853.65  131.66 1973.56  133.82 2068.49  130.39 2443.22  132.68 2528.16  132.44
 2573.13  129.81 2643.08  132.63 3029.86  131.23 3052.79  132.08 3087.76  121.43
 3112.56  118.35 3147.09  121.23 3171.76   129.7 3181.62  130.82 3222.71  130.59
 3416.61  131.55 3967.69   133.4 4183.57  134.63 4323.48  131.45 4483.38  134.69
 4592.31  132.99 4613.29  131.39 4725.27  133.74 4784.57  134.48 4813.16  133.68
#Mann= 11 ,-1 , 0
       0     .07       0  855.87     .15       0 3029.86     .07       0
 3052.79     .04       0 3181.62     .07       0 3222.71     .12       0
 3416.61     .07       0 3967.69     .15       0 4592.31     .07       0
 4725.27     .15       0 4784.57     .07       0
#XS Ineff= 2 ,-1
       0 3017.81  132.11 3444.04 4813.16  132.32
Permanent Ineff=
       F       F
Bank Sta=3052.79,3181.62
XS Rating Curve= 0 ,0
Exp/Cntr=0.5,0.3