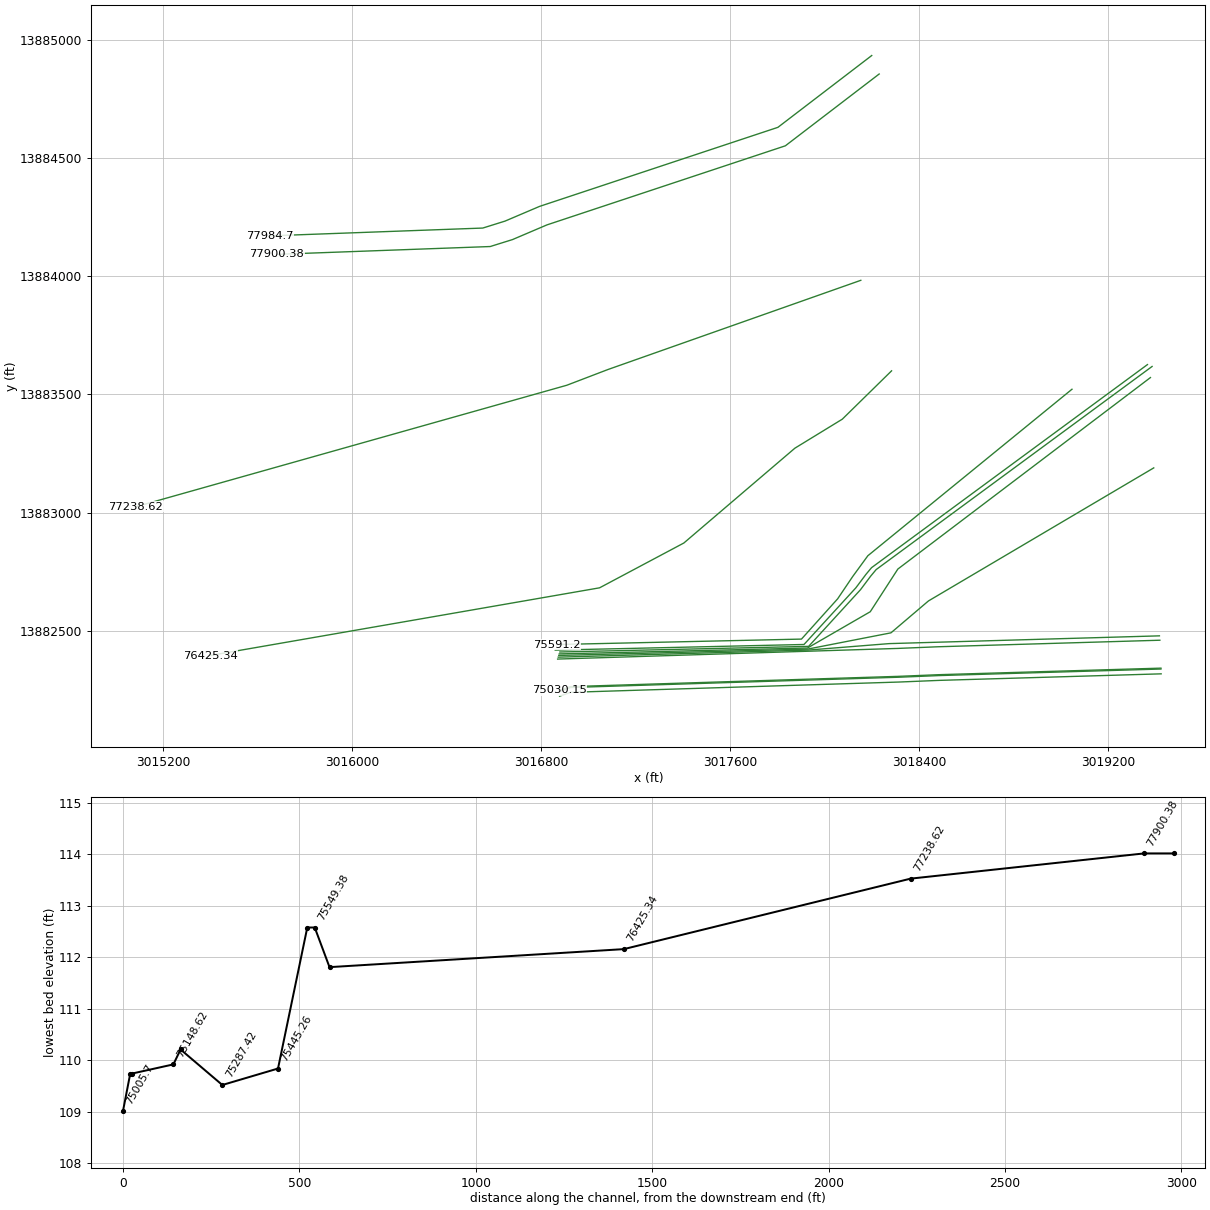
HEC-RAS study U100-00-00.prj: U100-00-00

--- U100-00-00.g01 (geometry) --- (continued)

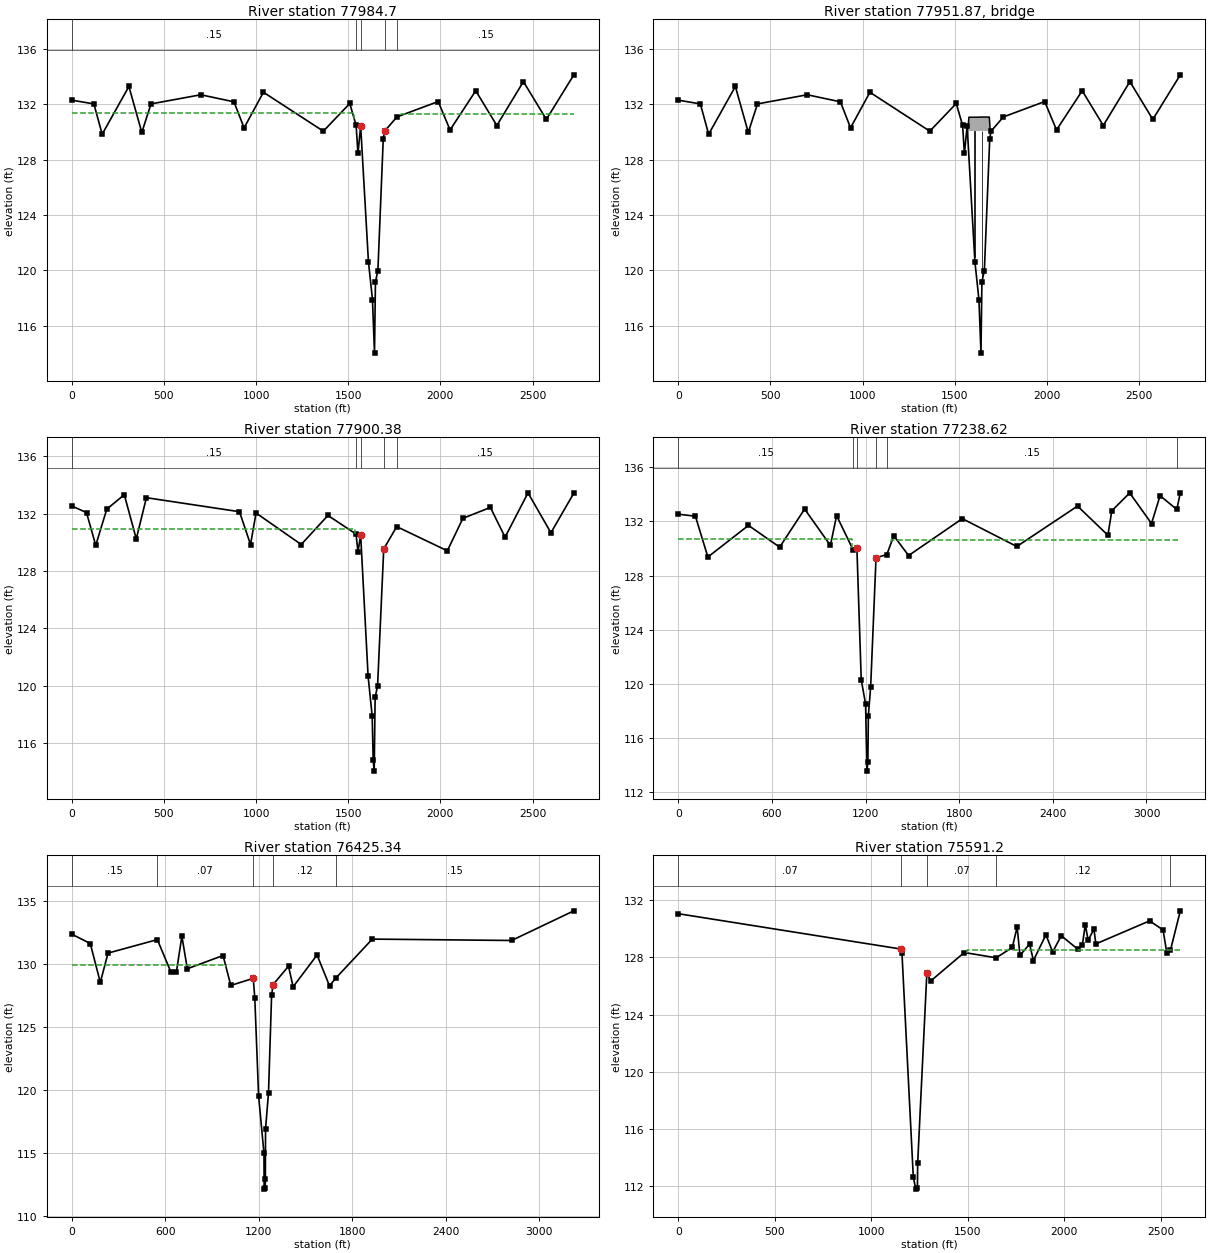
Type RM Length L Ch R = 1 ,77984.7 ,84.52,84.32,84.3
BEGIN DESCRIPTION:
Upstream Section - 18" PIPELINE
END DESCRIPTION:
XS GIS Cut Line= 6
3018198.7813685213884934.31822753017801.7332781113884630.4221818
3016793.02040052 13884295.8490323016646.9199709413884233.6024373
 3016552.710513713884204.19206313015649.2723599413884171.1137172
#Sta/Elev= 30
       0  132.29     120  132.02     165  129.83     310  133.28     380  129.96
     430  132.02     700  132.68     880  132.17     935  130.29    1040  132.86
    1365  130.05  1508.5  132.05 1542.89  130.47 1552.89  128.44 1567.58  130.43
 1609.72  120.63 1631.59  117.89 1642.66  114.02 1647.77  119.17 1661.03  119.98
 1690.24  129.52 1697.55  130.05 1764.45  131.08 1988.39  132.19 2052.67  130.14
 2191.95  132.97 2306.38  130.46 2450.67  133.63 2575.05   130.9 2724.31  134.12
#Mann= 5 ,-1 , 0
       0     .15       0 1542.89     .07       0 1567.58     .04       0
 1697.55     .12       0 1764.45     .15       0
#XS Ineff= 2 ,-1
       0 1533.16  131.34 1785.71 2724.31  131.26
Permanent Ineff=
       F       F
Bank Sta=1567.58,1697.55
XS Rating Curve= 0 ,0
Exp/Cntr=0.5,0.3

Type RM Length L Ch R = 3 ,77951.87,,,
BEGIN DESCRIPTION:
18" PIPELINE
END DESCRIPTION:
Node Name=18" PIPELINE
Bridge Culvert--1,0,-1,-1, 0
Deck Dist Width WeirC Skew NumUp NumDn MinLoCord MaxHiCord MaxSubmerge Is_Ogee
34,1.5,2.6,0, 26, 26, , , 0.98, 0, 0,0,,
  1572.4 1577.23 1582.05 1586.88  1591.7 1596.53 1601.36 1606.18 1611.01 1615.83
 1620.66 1625.48 1630.31 1635.11 1639.91 1644.72 1649.52 1654.32 1659.13 1663.93
 1668.73 1673.53 1678.34 1683.14 1687.94 1692.74
  130.29  131.06  131.06  131.06  131.06  131.06  131.06  131.06  131.06  131.06
  131.06  131.06  131.06  131.07  131.07  131.07  131.07  131.07  131.07  131.07
  131.07  131.07  131.07  131.07  131.07  130.09
       0  130.06  130.06  130.06  130.06  130.06  130.06  130.06  130.06  130.06
  130.06  130.06  130.06  130.07  130.07  130.07  130.07  130.07  130.07  130.07
  130.07  130.07  130.07  130.07  130.07       0
  1572.4 1577.23 1582.05 1586.88  1591.7 1596.53 1601.36 1606.18 1611.01 1615.83
 1620.66 1625.48 1630.31 1635.11 1639.91 1644.72 1649.52 1654.32 1659.13 1663.93
 1668.73 1673.53 1678.34 1683.14 1687.94 1692.74
  130.29  131.06  131.06  131.06  131.06  131.06  131.06  131.06  131.06  131.06
  131.06  131.06  131.06  131.07  131.07  131.07  131.07  131.07  131.07  131.07
  131.07  131.07  131.07  131.07  131.07  130.09
       0  130.06  130.06  130.06  130.06  130.06  130.06  130.06  130.06  130.06
  130.06  130.06  130.06  130.07  130.07  130.07  130.07  130.07  130.07  130.07
  130.07  130.07  130.07  130.07  130.07       0
Pier Skew, UpSta & Num, DnSta & Num=  ,1608.3, 2 ,1608.3, 2 , 0 , 0 , 0 ,,
     1.5     1.5
     110   130.5
     1.5     1.5
     110   130.5
Pier Skew, UpSta & Num, DnSta & Num=  ,1648.6, 2 ,1648.6, 2 , 0 , 0 , 0 ,,
     1.5     1.5
     110   130.5
     1.5     1.5
     110   130.5
BR Coef=-1 , 1 , 1 ,0.9, 0 ,,,0.8,-1,1.2,0,
WSPro=,,,, 1 ,,,, 0 ,,,, 0 ,,,,-1 ,-1 ,-1 , 0 , 0 , 0 , 0 , 0
BC Design=,, 0 ,, 0 ,,,,,,
BC Use User HTab Curves=0
BC User HTab FreeFlow(D)= 0

Type RM Length L Ch R = 1 ,77900.38,664.02,661.76,659.55
BEGIN DESCRIPTION:
Downstream Section - 18" PIPELINE
END DESCRIPTION:
Node Name=V
XS GIS Cut Line= 6
 3018230.274087713884856.11431573017833.2259972813884552.2182699
 3016824.513119713884217.6451202 3016678.412690113884155.3985255
3016584.2032328513884125.98815133015680.7650791113884092.9098054
#Sta/Elev= 30
       0  132.54      80  132.08     130  129.79     190  132.32     285  133.33
     350  130.24     405  133.12     910  132.14     970  129.85    1000  132.05
    1245  129.85    1390  131.88 1542.42  130.58 1552.89  129.35 1567.58  130.49
 1608.04  120.63 1629.91  117.89 1635.47   114.8 1640.98  114.02 1646.09  119.17
 1659.35  119.98 1692.74  129.54 1763.23   131.1 2037.84  129.41  2122.3  131.68
 2271.56  132.44 2351.16  130.36 2475.54  133.46 2599.93  130.67 2724.31  133.44
#Mann= 5 ,-1 , 0
       0     .15       0 1542.42     .07       0 1567.58     .04       0
 1692.74     .12       0 1763.23     .15       0
#XS Ineff= 2 ,-1
       0 1538.09  130.92 1761.04 2724.31  131.05
Permanent Ineff=
       F       F
Bank Sta=1567.58,1692.74
XS Rating Curve= 0 ,0
Exp/Cntr=0.5,0.3

Type RM Length L Ch R = 1 ,77238.62,805.74,813.28,824.14
XS GIS Cut Line= 4
3018152.5727995313883983.02222993017082.4499397713883605.5200321
3016908.1999601913883538.90008663015083.7652888613883024.5359579
#Sta/Elev= 30
       0  132.54  109.98  132.39  189.96  129.37   449.9  131.71  649.86   130.1
  809.82  132.92  974.79  130.23 1014.78  132.43 1121.36  129.88 1144.57  130.07
 1172.44   120.3  1200.4  118.49 1208.75  113.53 1214.93   114.2 1218.22  117.64
 1232.92  119.77 1267.31  129.32 1336.27  129.55 1381.17  130.94 1475.95  129.48
 1820.14  132.21 2169.32  130.15 2558.41  133.14 2752.95  130.98 2777.89  132.79
 2892.62  134.11 3032.29  131.85 3087.16  133.91 3194.34  132.89 3216.86  134.12
#Mann= 6 ,-1 , 0
       0     .15       0 1121.36     .07       0 1144.57     .04       0
 1267.31     .12       0 1336.27     .15       0 3194.34     .07       0
#XS Ineff= 2 ,-1
       0 1114.76   130.7  1366.2 3216.86  130.63
Permanent Ineff=
       F       F
Bank Sta=1144.57,1267.31
XS Rating Curve= 0 ,0
Exp/Cntr=0.3,0.1

Type RM Length L Ch R = 1 ,76425.34,833.38,834.13,853.71
XS GIS Cut Line= 6
3018282.7562661913883599.91013523018074.2934285313883395.3918434
3017873.60780628 13883272.5912363017403.7399796113882871.3200569
3017047.0500761913882681.66065943015398.7243046213882395.1769803
#Sta/Elev= 30
       0  132.36  118.79  131.62  183.14  128.54  232.64  130.86  549.25  131.93
  636.94  129.34  671.82   129.4   706.7   132.2  741.58  129.62   970.8  130.67
 1020.63   128.3 1164.82  128.86 1174.62  127.29 1199.13  119.54 1233.45  114.99
 1234.61  112.16  1241.2  112.21 1242.39     113  1243.7  116.94 1262.66  119.81
 1282.48  127.53 1292.28  128.37 1390.94  129.82 1420.62  128.19 1574.18  130.71
 1654.09  128.27 1695.26  128.89 1928.76  131.97 2822.72  131.86 3222.25  134.21
#Mann= 5 ,-1 , 0
       0     .15       0  549.25     .07       0 1164.82     .04       0
 1292.28     .12       0 1695.26     .15       0
#XS Ineff= 2 ,-1
       0  990.73  129.95 1599.15 3222.25  129.94
Permanent Ineff=
       F       F
Bank Sta=1164.82,1292.28
XS Rating Curve= 0 ,0
Exp/Cntr=0.3,0.1

Type RM Length L Ch R = 1 ,75591.2 ,42.46,41.82,39.36
Node Name=U
XS GIS Cut Line= 6
3019046.3088729413883522.05300743018182.43986578 13882817.470099
3018118.1899942813882729.38989463018054.5798852713882635.1400831
 3017901.436162713882464.65715633016867.1088350313882441.6611394
#Sta/Elev= 30
       0  131.04 1154.42  128.57 1159.17  128.27 1217.83  112.66 1230.77  111.81
 1239.16  111.91 1240.48   113.6 1288.07   126.9 1307.84  126.34 1481.98  128.33
 1646.93  127.96 1730.84  128.68 1755.72  130.11 1770.64  128.13 1820.39  128.92
 1840.29  127.77 1904.96  129.57 1939.79  128.37 1984.56   129.5 2069.14  128.57
 2094.01  128.88 2108.94  130.27 2123.86  129.18 2153.71  129.97 2163.66  128.93
 2442.25  130.54  2511.9   129.9  2531.8  128.27 2550.07  128.48 2601.25  131.24
#Mann= 5 ,-1 , 0
       0     .07       0 1154.42     .04       0 1288.07     .07       0
 1646.93     .12       0 2550.07     .15       0
#XS Ineff= 2 ,-1
       0  811.41     129 1496.93 2601.25   128.5
Permanent Ineff=
       F       F
Bank Sta=1154.42,1288.07
XS Rating Curve= 0 ,0
Exp/Cntr=0.5,0.3

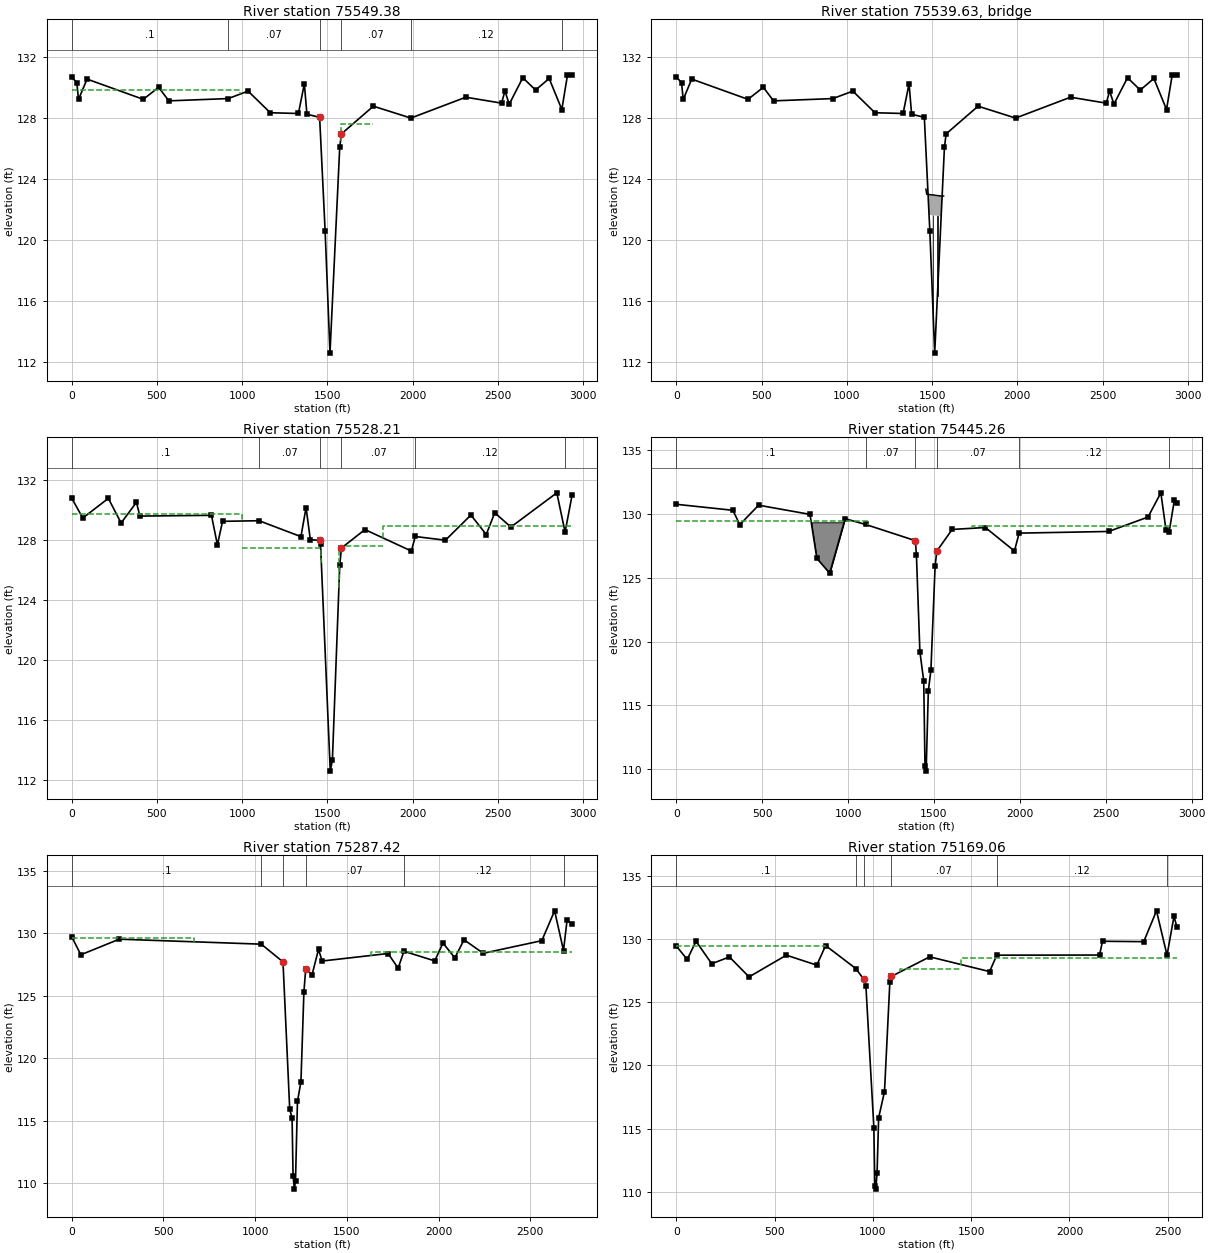
Type RM Length L Ch R = 1 ,75549.38,20.6,21.18,21.29
BEGIN DESCRIPTION:
Upstream Section - 16" PIPELINE
END DESCRIPTION:
XS GIS Cut Line= 6
 3019365.732446713883626.44748373018197.9837979413882766.8760401
3018174.2446721913882738.43712063018131.7844552713882681.8237168
3017912.1484116213882441.83174273016859.3565539413882418.0237194
#Sta/Elev= 30
       0  130.71      30  130.35      40  129.24      90  130.58     420  129.25
     510  130.04     570  129.15  918.18   129.3    1035  129.79    1165  128.37
    1330  128.32    1365  130.27    1380  128.27 1454.63  128.07 1486.77  120.63
 1515.38  112.58 1572.61  126.11 1582.46  126.98 1769.77   128.8 1990.09  128.02
  2312.3  129.39 2521.89     129 2541.85   129.8 2566.81  128.93 2646.65  130.67
  2721.5  129.86 2801.34  130.62 2875.61  128.58 2908.51  130.83  2936.2  130.86
#Mann= 6 ,-1 , 0
       0      .1       0  918.18     .07       0 1454.63     .04       0
 1582.46     .07       0 1990.09     .12       0 2875.61     .15       0
#XS Ineff= 4 ,-1
       0     990  129.87     990 1454.63  127.47 1577.53 1769.77  127.61
 1769.77  2936.2   128.8
Permanent Ineff=
       F       F       F       F
Bank Sta=1454.63,1582.46
XS Rating Curve= 0 ,0
Exp/Cntr=0.5,0.3

Type RM Length L Ch R = 3 ,75539.63,,,
BEGIN DESCRIPTION:
16" PIPELINE
END DESCRIPTION:
Node Name=16" PIPELINE
Bridge Culvert--1,0,-1,-1, 0
Deck Dist Width WeirC Skew NumUp NumDn MinLoCord MaxHiCord MaxSubmerge Is_Ogee
5,3,2.6,0, 22, 22, , , 0.98, 0, 0,0,,
 1463.89 1468.52 1477.78 1482.41 1487.05 1491.36 1495.67 1499.98 1504.29  1508.6
 1512.91 1517.22 1521.74 1526.25 1530.76 1535.27 1539.78 1544.29 1553.31 1557.82
 1562.75 1567.68
  123.35  123.02  123.01     123  122.99  122.99  122.98  122.97  122.97  122.97
  122.96  122.95  122.94  122.94  122.93  122.92  122.92  122.91   122.9   122.9
   122.9   122.9
  122.05  121.69  121.68  121.67  121.66  121.66  121.65  121.64  121.64  121.64
  121.63  121.62  121.61  121.61   121.6  121.59  121.59  121.58  121.55  121.57
  121.57  121.57
 1463.89 1468.52 1477.78 1482.41 1487.05 1491.36 1495.67 1499.98 1504.29  1508.6
 1512.91 1517.22 1521.74 1526.25 1530.76 1535.27 1539.78 1544.29 1553.31 1557.82
 1562.75 1567.68
  123.35  123.02  123.01     123  122.99  122.99  122.98  122.97  122.97  122.97
  122.96  122.95  122.94  122.94  122.93  122.92  122.92  122.91   122.9   122.9
   122.9   122.9
  122.05  121.69  121.68  121.67  121.66  121.66  121.65  121.64  121.64  121.64
  121.63  121.62  121.61  121.61   121.6  121.59  121.59  121.58  121.55  121.57
  121.57  121.57
Pier Skew, UpSta & Num, DnSta & Num=  ,1468.78, 2 ,1468.78, 2 , 0 , 0 , 0 ,,
     1.4     1.4
     110   122.7
     1.4     1.4
     110   122.7
Pier Skew, UpSta & Num, DnSta & Num=  ,1506.08, 2 ,1506.08, 2 , 0 , 0 , 0 ,,
     1.4     1.4
     110   122.7
     1.4     1.4
     110   122.7
Pier Skew, UpSta & Num, DnSta & Num=  ,1531.18, 2 ,1531.18, 2 , 0 , 0 , 0 ,,
     1.4     1.4
     110   122.7
     1.4     1.4
     110   122.7
BR Coef=-1 , 1 , 1 ,0.9, 0 ,,,0.8,-1,1.2,0,
WSPro=,,,, 1 ,,,, 0 ,,,, 0 ,,,,-1 ,-1 ,-1 , 0 , 0 , 0 , 0 , 0
BC Design=,, 0 ,, 0 ,,,,,,
BC Use User HTab Curves=0
BC User HTab FreeFlow(D)= 0

Type RM Length L Ch R = 1 ,75528.21,77.63,82.95,86.96
BEGIN DESCRIPTION:
Downstream Section - 16" PIPELINE
END DESCRIPTION:
XS GIS Cut Line= 6
3019385.3255833513883618.45373333018217.5769346113882758.8822897
3018193.8378088613882730.44337023018151.3775919413882673.8299664
3017931.7415482713882433.83799233016878.94969061 13882410.029969
#Sta/Elev= 30
       0  130.78      65  129.45     215  130.76     290  129.12     380   130.5
     400  129.58     820  129.63     855  127.66     885  129.23 1099.57  129.27
    1345  128.21    1375  130.15    1400  128.01 1454.63  127.96 1459.98  127.71
    1517  112.58 1529.48  113.31 1572.61  126.31 1582.46  127.45 1720.48  128.68
 1992.93  127.25 2015.53  128.22 2192.54  127.97 2342.25  129.65 2432.07  128.35
 2481.97   129.8 2576.79  128.85 2846.26  131.13 2894.61  128.51  2936.2     131
#Mann= 6 ,-1 , 0
       0      .1       0 1099.57     .07       0 1454.63     .04       0
 1582.46     .07       0 2015.53     .12       0 2894.61     .15       0
#XS Ineff= 4 ,-1
       0    1000  129.74    1000 1464.63  127.47 1567.53 1823.99  127.61
 1823.99  2936.2  128.91
Permanent Ineff=
       F       F       F       F
Bank Sta=1454.63,1582.46
XS Rating Curve= 0 ,0
Exp/Cntr=0.5,0.3

Type RM Length L Ch R = 1 ,75445.26,176.35,157.83,143.01
XS GIS Cut Line= 6
3019378.2829465313883571.43939163018309.3421710313882761.0463274
3018192.6271813713882580.50272523017926.7576343613882426.8383344
3016929.80654427 13882403.2780143016876.4063886113882402.0162055
#Sta/Elev= 30
       0  130.76  329.12  130.29  369.01  129.16  478.72  130.69  777.92  129.97
  817.81  126.52  892.61  125.36  982.37  129.63 1101.79  129.18  1391.4  127.91
 1397.62  126.78 1417.81  119.21 1440.07  116.92 1447.54  110.25 1454.22  109.84
 1466.95  116.11 1482.01  117.77 1506.39  125.92 1516.39  127.09 1605.92  128.79
 1799.08  128.94 1968.18   127.1 1995.74   128.5 2516.66  128.63 2746.02  129.76
 2820.81  131.66 2850.73  128.76 2869.42  128.62 2899.55  131.08 2914.11  130.88
#Mann= 6 ,-1 , 0
       0      .1       0 1101.79     .07       0  1391.4     .04       0
 1516.39     .07       0 1995.74     .12       0 2869.42     .15       0
#XS Ineff= 2 ,-1
       0 1117.01  129.48 1719.84 2914.11  129.09
Permanent Ineff=
       F       F
#Block Obstruct= 1 ,-1
  787.89  977.38  129.35
Bank Sta=1391.4,1516.39
XS Rating Curve= 0 ,0
Exp/Cntr=0.3,0.1

Type RM Length L Ch R = 1 ,75287.42,155.24,118.36,78.06
XS GIS Cut Line= 6
3019392.2927610313883189.21312193018438.8228831913882626.0944975
3018280.1634236113882491.1426677 3017927.491228713882422.2855219
3016930.1251131913882396.86004783016874.3187943513882395.4374785
#Sta/Elev= 30
       0  129.74   49.88  128.29  259.38  129.54  1033.7  129.14 1151.98  127.72
  1188.7  115.91 1201.44  115.23 1206.88  110.59 1213.95  109.52 1220.17  110.18
 1230.82  116.54 1249.77  118.11 1266.07  125.33 1275.96  127.16 1310.67   126.7
 1345.58  128.72 1365.54  127.79 1724.85  128.39 1779.72  127.22 1811.32  128.57
 1979.26   127.8 2024.16  129.23 2089.01  128.04 2138.89  129.49 2243.65  128.41
 2562.91  129.42 2632.75  131.81 2681.25  128.63 2700.57  131.05 2728.48  130.74
#Mann= 6 ,-1 , 0
       0      .1       0  1033.7     .07       0 1151.98     .04       0
 1275.96     .07       0 1811.32     .12       0 2681.25     .15       0
#XS Ineff= 3 ,-1
       0   668.4  129.66 1357.98 1630.05  127.61 1630.05 2728.48  128.51
Permanent Ineff=
       F       F       F
Bank Sta=1151.98,1275.96
XS Rating Curve= 0 ,0
Exp/Cntr=0.3,0.1

Type RM Length L Ch R = 1 ,75169.06,19.63,20.45,21.8
XS GIS Cut Line= 5
3019416.3107576113882478.37727333018272.8688187713882445.5508953
3017929.2346635313882418.14642263016925.6848333613882389.7491697
3016872.03205353   13882388.2308
#Sta/Elev= 30
       0  129.45   54.95  128.39   99.91  129.83  179.83  128.05  269.74  128.59
  369.65  127.01  559.47  128.73  714.32  127.94  759.28  129.49  912.75  127.67
  954.09  126.81  964.33  126.25 1004.67  115.08 1009.57  110.43 1014.44  110.21
    1021   111.5 1028.94  115.86 1058.77  117.93 1086.01  126.59 1093.96  127.05
  1288.8   128.6 1593.53  127.43 1629.92  128.73 2152.94  128.74 2167.93  129.83
 2377.71   129.8 2442.65  132.24 2496.25  128.72 2531.63  131.81 2546.27  130.97
#Mann= 6 ,-1 , 0
       0      .1       0  912.75     .07       0  954.09     .04       0
 1093.96     .07       0 1629.92     .12       0 2496.25     .15       0
#XS Ineff= 4 ,-1
       0  759.28  129.49  759.28  905.55  127.47 1137.78 1448.67  127.61
 1448.67 2546.27  128.47
Permanent Ineff=
       F       F       F       F
Bank Sta=954.09,1093.96
XS Rating Curve= 0 ,0
Exp/Cntr=0.5,0.3

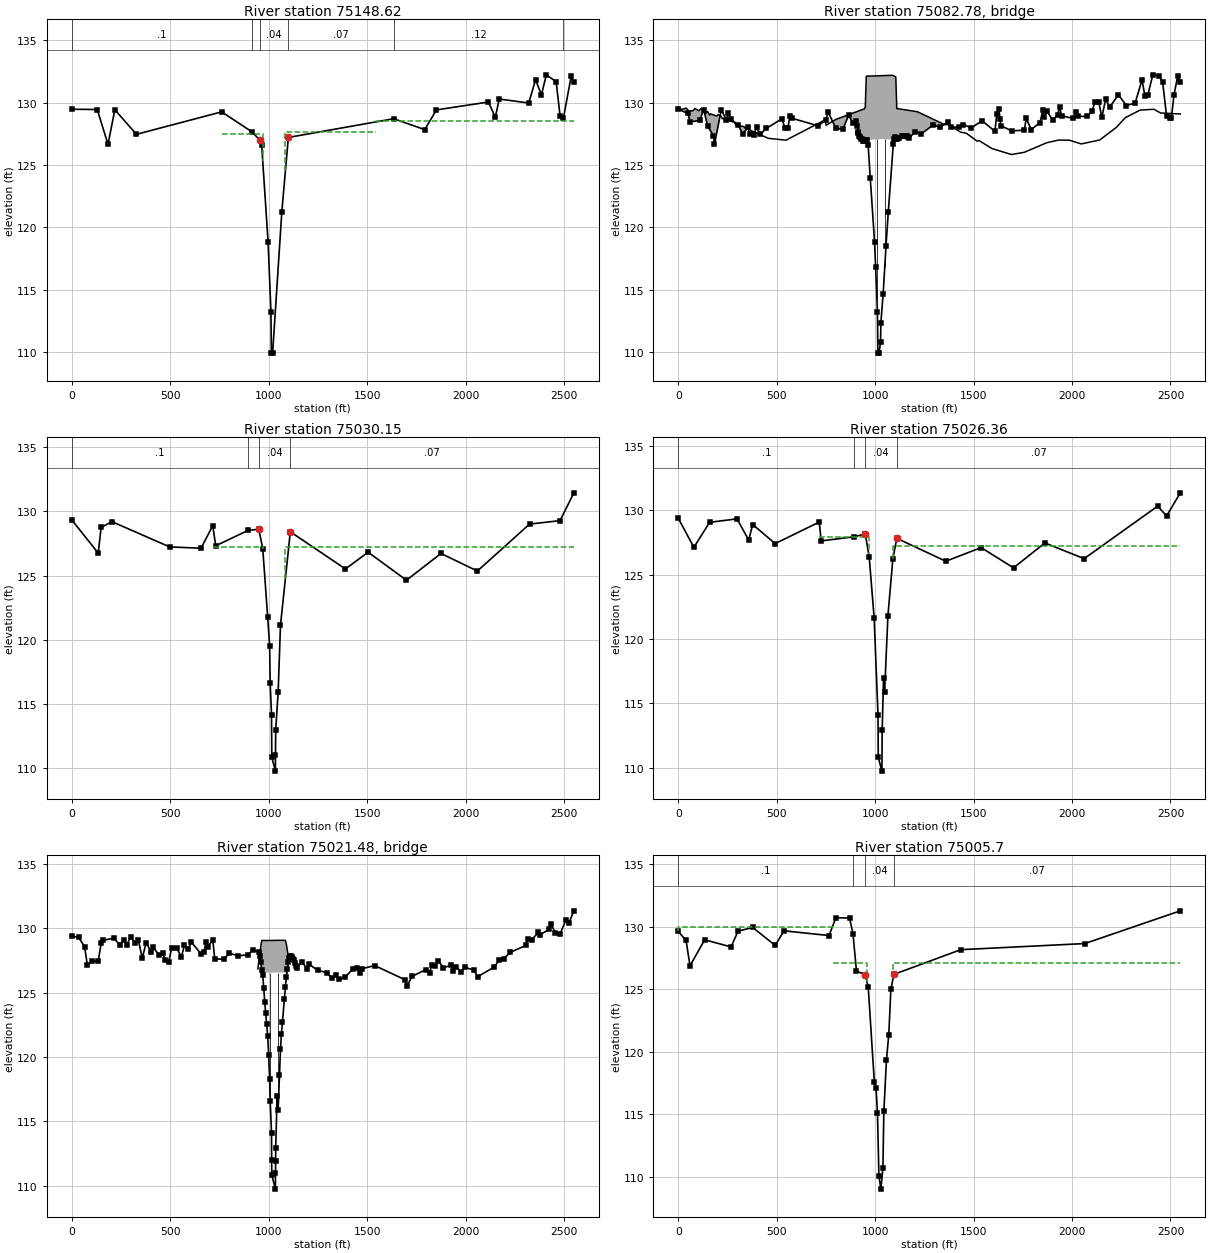
Type RM Length L Ch R = 1 ,75148.62,123.6,118.47,120.52
BEGIN DESCRIPTION:
Upstream Section - FREEMAN ROAD (FM 529)
END DESCRIPTION:
XS GIS Cut Line= 5
3019418.1916593613882459.85532873018478.5997065313882432.1601741
 3018308.744075113882425.15625113016919.4246752713882381.6566662
3016869.4490534413882380.0920368
#Sta/Elev= 30
       0  129.47  129.31  129.45  184.02  126.66  218.84  129.43  328.25  127.46
  760.95  129.26  914.49  127.67     955     127  964.51  126.59  997.17  118.82
 1011.61  113.21 1013.83  109.93 1020.07  109.92 1066.84  121.25    1100  127.21
 1634.68  128.71 1792.54  127.84 1852.33  129.42 2116.38  130.05 2151.25  128.83
 2171.18  130.29 2320.64  129.97 2355.52  131.83 2385.41  130.63 2410.32  132.23
 2460.14  131.68 2480.07  128.93 2496.83  128.74 2536.36  132.11    2550  131.66
#Mann= 6 ,-1 , 0
       0      .1       0  914.49     .07       0     955     .04       0
    1100     .07       0 1634.68     .12       0 2496.83     .15       0
#XS Ineff= 4 ,-1
       0  760.95  129.26  760.95     970  127.47    1085 1543.44  127.61
 1543.44    2550  128.55
Permanent Ineff=
       F       F       F       F
#Block Obstruct= 2 , 0
       0                 2480.07       0  128.93
Bank Sta=955,1100
XS Rating Curve= 0 ,0
Exp/Cntr=0.5,0.3

Type RM Length L Ch R = 3 ,75082.78,,,
BEGIN DESCRIPTION:
FREEMAN ROAD (FM 529)
U00_1100
END DESCRIPTION:
Node Name=FREEMAN ROAD
Bridge Culvert--1,0,-1,-1, 0
Deck Dist Width WeirC Skew NumUp NumDn MinLoCord MaxHiCord MaxSubmerge Is_Ogee
26.5,89.3,2.6,0, 60, 60, , , 0.98, 0, 0,0,,
       0   14.92   39.79   54.71    74.6   84.55  104.44  114.39  139.26  149.21
  159.15  164.13  193.97  203.92  218.84  223.81  248.68  258.62  283.49  293.44
  333.23  343.17  353.12  368.04  457.57  547.09  746.03  751.01  800.74     945
     950     955     965     970    1030    1085    1090    1105    1110 1214.62
 1354.12 1369.07 1433.83 1463.73 1518.53 1528.49 1593.26  1692.9 1757.67 1872.25
 1932.04 1986.84 2046.63 2141.29 2225.98 2270.82 2345.56 2415.31 2450.18    2550
  129.64  129.45  129.56  129.33  129.35  129.53  129.35  129.51  129.14  129.29
     129   129.1  128.93  129.04  128.89  128.71   128.7  128.53  128.45  128.21
  128.08   127.9  128.03  127.77  127.14  126.99  128.62  128.19  128.66   129.5
  129.65  132.12  132.13  132.13  132.16  132.19  132.19  132.06  129.53  129.27
  128.23  128.25  127.64  127.54  126.91  126.95  126.32  125.84  126.02  126.79
     127  126.99  126.69  127.01  128.03   128.8   129.4  129.47  129.17  129.09
       0       0       0       0       0       0       0       0       0       0
       0       0       0       0       0       0       0       0       0       0
       0       0       0       0       0       0       0       0       0       0
       0       0       0  127.01  127.08  127.03       0       0       0       0
       0       0       0       0       0       0       0       0       0       0
       0       0       0       0       0       0       0       0       0       0
       0   14.92   39.79   54.71    74.6   84.55  104.44  114.39  139.26  149.21
  159.15  164.13  193.97  203.92  218.84  223.81  248.68  258.62  283.49  293.44
  333.23  343.17  353.12  368.04  457.57  547.09  746.03  751.01  800.74     945
     950     955     965     970    1085    1090    1105    1110 1159.82 1214.62
 1354.12 1369.07 1433.83 1463.73 1518.53 1528.49 1593.26  1692.9 1757.67 1872.25
 1932.04 1986.84 2046.63 2141.29 2225.98 2270.82 2345.56 2415.31 2450.18    2550
  129.64  129.45  129.56  129.33  129.35  129.53  129.35  129.51  129.14  129.29
     129   129.1  128.93  129.04  128.89  128.71   128.7  128.53  128.45  128.21
  128.08   127.9  128.03  127.77  127.14  126.99  128.62  128.19  128.66   129.5
  129.66  132.24  132.23  132.23   132.2   132.2  132.05  129.53  129.31  129.27
  128.23  128.25  127.64  127.54  126.91  126.95  126.32  125.84  126.02  126.79
     127  126.99  126.69  127.01  128.03   128.8   129.4  129.47  129.17  129.09
       0       0       0       0       0       0       0       0       0       0
       0       0       0       0       0       0       0       0       0       0
       0       0       0       0       0       0       0       0       0       0
       0       0       0  127.03   127.1       0       0       0       0       0
       0       0       0       0       0       0       0       0       0       0
       0       0       0       0       0       0       0       0       0       0
Pier Skew, UpSta & Num, DnSta & Num=  ,1008.9, 2 ,1008.9, 2 , 0 , 0 , 0 ,,
     1.5     1.5
     105   129.5
     1.5     1.5
     105   129.5
Pier Skew, UpSta & Num, DnSta & Num=  ,1048.9, 2 ,1048.9, 2 , 0 , 0 , 0 ,,
     1.5     1.5
     105   129.5
     1.5     1.5
     105   129.5
Abutment Skew #Up #Dn= , 3 , 4
   949.8   997.9  1017.9
  127.42  119.97  112.13
   949.8   970.8   997.5  1018.7
  126.37  125.21   120.5  112.57
Abutment Skew #Up #Dn= , 5 , 5
  1038.7  1059.1  1086.4  1097.5  1108.6
  113.94  120.51  125.12  126.99  126.65
  1039.7  1060.3  1086.7  1098.8  1108.6
  113.06  120.78  125.24  126.12  126.43
BR Coef=-1 , 1 , 1 ,1.25, 0 ,,,0.8,-1,2,0,
WSPro=,,,, 1 ,,,, 0 ,,,, 0 ,,,,-1 ,-1 ,-1 , 0 , 0 , 0 , 0 , 0
BR U #Sta/Elev= 124
       0  129.47   49.74  129.13   59.68  128.46  109.42  128.57  129.31  129.45
  149.21  128.13  179.05  127.34  184.02  126.66  218.84  129.43   243.7  128.63
  253.65  129.16  268.57  128.66  303.39  128.23  328.25  127.46  353.12  128.03
  363.07  127.46  382.96   127.4  397.88  128.02  417.78  127.47  447.62  127.94
   527.2  128.71  542.12  127.93  557.04  127.98  566.98  128.91  576.93  128.75
  711.22  128.14  751.01  128.64  760.95  129.26  800.74  127.94  835.56  127.85
   865.4  128.99  885.29  128.38  905.19  128.53  910.16  128.12  914.49  127.67
  915.13   127.6  920.11  127.33  925.08  127.24  930.05  127.08  935.03  127.11
     940  126.95     945  126.89     950   126.9     955     127     960  126.99
  964.51  126.59  975.35  123.94  997.17  118.82 1002.58   116.8 1011.61  113.21
 1013.83  109.93 1020.07  109.92 1027.56  110.85 1029.18  112.37 1040.63  114.64
 1055.22  118.49 1066.84  121.25 1092.47  126.72    1095  127.11    1100  127.21
    1105  127.12    1110   127.1 1114.98  127.14 1119.96  127.17 1134.91  127.29
 1139.89  127.34 1144.87  127.33 1149.86  127.31 1154.84  127.31 1159.82  127.32
  1164.8  127.25 1169.78  127.13 1204.66  127.67 1234.55   127.5 1294.34   128.2
 1329.21  128.03 1369.07  128.45 1384.01  128.06 1423.87  128.02 1448.78  128.24
 1488.64  127.98 1543.44  128.55  1608.2   127.7 1618.17   129.1 1628.13  129.47
 1634.68  128.71  1638.1  128.16  1692.9  127.74 1757.67  127.79 1767.63  128.74
 1792.54  127.84 1837.38   128.4 1852.33  129.42 1857.31  128.83 1872.25  129.34
 1902.15  128.59 1927.06  129.02 1937.02  129.65 1946.98  128.95 2006.77  128.73
 2021.71  129.29 2031.68  128.91 2076.52  128.89 2101.43   129.3 2116.38  130.05
  2136.3  130.04 2151.25  128.83 2171.18  130.29 2191.11  129.64 2235.95  130.63
  2275.8  129.77 2320.64  129.97 2355.52  131.83 2370.47  130.51 2385.41  130.63
 2410.32  132.23 2440.22  132.14 2460.14  131.68 2480.07  128.93 2496.83  128.74
 2504.55  128.78 2518.18  130.63 2536.36  132.11    2550  131.66
BR U #Mann= 6
       0      .1  914.49     .07     960    .015    1100     .07 1634.68     .12
 2496.83     .15
BR D #Sta/Elev= 118
       0  129.34   29.84  129.05   39.79  129.33   64.66  128.86   79.58  127.71
    94.5  127.06  134.29  126.75  149.21  128.75  203.92   129.2   243.7  128.56
  258.62  129.13  273.54  128.78  298.41  129.17  323.28   128.5  333.23  128.99
  343.17  128.59  353.12   127.4  377.99  128.53  402.86  127.85  417.78  128.21
  462.54  127.86  472.49  127.32  497.35  127.23   507.3  127.89  532.17  128.12
  547.09  127.45  571.96  128.17  591.85  127.77  611.75  128.26  656.51  127.13
  671.43  127.32  681.38  128.64  691.32  128.38  716.19  128.89  731.11  127.32
  800.74  128.22  835.56  128.22  850.48  128.45  895.73  128.52  920.11  128.86
     950  128.61     955  128.25     960  127.79     965  127.08     970  127.09
     975  125.65     980  124.36     985  123.43     990  122.76     995  121.77
    1000  120.53    1005   119.5  1007.7  116.61 1014.52  114.13 1015.18  111.97
 1015.94  110.82  1034.4  109.74 1034.48  110.98 1035.32  111.92 1035.86  112.95
 1048.14   115.9    1050  116.55    1055  119.05    1060  121.12    1065  122.19
    1070  122.96    1075  123.77    1080  124.61    1085  125.51    1090  126.36
    1095  127.06    1100  127.77    1105  128.05    1110  128.41    1125   128.3
    1140  127.55    1160  128.02    1195  127.41    1205  127.68    1265  127.02
    1345  126.35    1360  125.89    1390  125.51    1415  125.71    1430  126.43
    1460  126.45    1505  126.82    1540  126.66    1550  126.34    1590  125.93
    1625  126.07    1690  125.38    1700  124.63    1780  125.88    1790  126.22
 1814.99  126.07 1824.99  126.48 1874.99  126.72 1899.99  126.44 1924.99   126.7
 1994.99  126.43 2039.99  125.91 2059.99  125.35 2079.99  125.98 2134.99  126.62
 2209.99  127.11 2224.99  127.64 2289.99  128.57 2304.99  128.53 2324.99  129.01
 2334.99  128.83    2410  129.59    2440  130.02    2455  129.36    2480  129.28
    2510  130.27    2530  129.99    2550  131.45
BR D #Mann= 4
       0      .1  895.73     .07     950    .015    1110     .07
BC Design=,, 0 ,, 0 ,,,,,,
BC Use User HTab Curves=0
BC User HTab FreeFlow(D)= 0

Type RM Length L Ch R = 1 ,75030.15,3.97,3.79,4.03
BEGIN DESCRIPTION:
Downstream Section - FREEMAN ROAD (FM 529)
END DESCRIPTION:
XS GIS Cut Line= 5
3019422.7349573713882341.72629993018483.1430045213882314.0308172
3018313.2873731113882307.02722233016923.9683013613882263.5276373
3016876.7193801113882247.1713708
#Sta/Elev= 30
       0  129.34  134.29  126.75  149.21  128.75  203.92   129.2  497.35  127.23
  656.51  127.13  716.19  128.89  731.11  127.32  895.73  128.52     950  128.61
     970  127.09     995  121.77    1005   119.5  1007.7  116.61 1014.52  114.13
 1015.94  110.82  1034.4  109.74 1034.48  110.98 1035.86  112.95 1048.14   115.9
    1060  121.12    1110  128.41    1390  125.51    1505  126.82    1700  124.63
 1874.99  126.72 2059.99  125.35 2324.99  129.01    2480  129.28    2550  131.45
#Mann= 4 ,-1 , 0
       0      .1       0  895.73     .07       0     950     .04       0
    1110     .07       0
#XS Ineff= 3 ,-1
       0  716.19  128.89  716.19  970.21  127.25    1085    2550  127.25
Permanent Ineff=
       F       F       F
Bank Sta=950,1110
XS Rating Curve= 0 ,0
Exp/Cntr=0.5,0.3

Type RM Length L Ch R = 1 ,75026.36,22.62,20.66,21.71
BEGIN DESCRIPTION:
Upstream Section - 30" PIPELINE
END DESCRIPTION:
XS GIS Cut Line= 5
3019422.8802982713882337.94973263018483.2883454413882310.2542499
3018313.43271403 13882303.250655 3016924.113314213882259.7510701
3016876.8643929413882243.3948036
#Sta/Elev= 30
       0  129.37   79.58  127.11  159.15  129.05  298.41  129.32   358.1  127.67
  377.99  128.88  492.38   127.4  716.19  129.07  726.14  127.61  894.49  127.93
     950  128.15     970  126.34     995  121.63 1014.51  114.13 1015.93  110.82
 1034.39  109.74 1035.85  112.95 1042.78  116.93 1048.13   115.9    1065  121.81
    1090  126.21    1110  127.81  1359.1  126.03 1538.46  127.09 1702.86  125.52
 1862.29  127.45 2061.57  126.23 2435.23  130.31 2480.07  129.54    2550  131.34
#Mann= 4 ,-1 , 0
       0      .1       0  894.49     .07       0     950     .04       0
    1110     .07       0
#XS Ineff= 3 ,-1
       0  716.19  129.07  716.19  967.56  127.88    1090    2550  127.25
Permanent Ineff=
       F       F       F
Bank Sta=950,1110
XS Rating Curve= 0 ,0
Exp/Cntr=0.5,0.3

Type RM Length L Ch R = 3 ,75021.48,,,
BEGIN DESCRIPTION:
30" PIPELINE
U00_1100
END DESCRIPTION:
Node Name=30" PIPELINE
Bridge Culvert--1,0,-1,-1, 0
Deck Dist Width WeirC Skew NumUp NumDn MinLoCord MaxHiCord MaxSubmerge Is_Ogee
1.75,2.5,2.6,0, 31, 31, , , 0.98, 0, 0,0,,
     945     950     955     960     965     970     975     980     985     990
     995    1000    1005    1010    1015    1020    1025    1035    1040    1045
    1050    1055    1060    1065    1070    1075    1080    1085    1090    1095
    1100
  126.82  127.41     128  128.59  129.04  129.04  129.04  129.04  129.04  129.04
  129.04  129.04  129.04  129.04  129.04  129.04  129.04  129.05  129.05  129.05
  129.05  129.05  129.05  129.05  129.05  129.05  129.05  129.05  128.74  128.25
  127.77
  124.32  124.91   125.5  126.09  126.54  126.54  126.54  126.54  126.54  126.54
  126.54  126.54  126.54  126.54  126.54  126.54  126.54  126.55  126.55  126.55
  126.55  126.55  126.55  126.55  126.55  126.55  126.55  126.55  126.24  125.75
  125.27
     945     950     955     960     965     970     975     980     985     990
     995    1000    1005    1010    1015    1020    1025    1035    1040    1045
    1050    1055    1060    1065    1070    1075    1080    1085    1090    1095
    1100
  126.82  127.41     128  128.59  129.04  129.04  129.04  129.04  129.04  129.04
  129.04  129.04  129.04  129.04  129.04  129.04  129.04  129.05  129.05  129.05
  129.05  129.05  129.05  129.05  129.05  129.05  129.05  129.05  128.74  128.25
  127.77
  124.32  124.91   125.5  126.09  126.54  126.54  126.54  126.54  126.54  126.54
  126.54  126.54  126.54  126.54  126.54  126.54  126.54  126.55  126.55  126.55
  126.55  126.55  126.55  126.55  126.55  126.55  126.55  126.55  126.24  125.75
  125.27
Pier Skew, UpSta & Num, DnSta & Num=  ,1008.35, 2 ,1008.35, 2 , 0 , 0 , 0 ,,
    1.15    1.15
     105     129
    1.15    1.15
     105     129
Pier Skew, UpSta & Num, DnSta & Num=  ,1047.75, 2 ,1047.75, 2 , 0 , 0 , 0 ,,
    1.15    1.15
     105     129
    1.15    1.15
     105     129
Abutment Skew #Up #Dn= , 5 , 5
  1038.7  1059.1  1086.4  1097.5  1108.6
  113.94  120.51  125.12  126.99  126.65
  1039.7  1060.3  1086.7  1098.8  1108.6
  113.06  120.78  125.24  126.12  126.43
Abutment Skew #Up #Dn= , 5 , 5
  1038.7  1059.1  1086.4  1097.5  1108.6
  113.94  120.51  125.12  126.99  126.65
  1039.7  1060.3  1086.7  1098.8  1108.6
  113.06  120.78  125.24  126.12  126.43
BR Coef=-1 , 1 , 1 ,0.9, 0 ,,,0.8,-1,1.25,1,
WSPro=,,,, 1 ,,,, 0 ,,,, 0 ,,,,-1 ,-1 ,-1 , 0 , 0 , 0 , 0 , 0
BR U #Sta/Elev= 126
       0  129.37   34.81  129.28   64.66  128.57   79.58  127.11  104.44  127.42
  134.29  127.45  149.21  128.81  159.15  129.05  213.86  129.22   243.7  128.69
   263.6  129.09  278.52  128.65  298.41  129.32  323.28  128.82   338.2  129.06
   358.1  127.67  377.99  128.88  402.86  128.13   412.8   128.5  442.65  127.95
  462.54   128.1  472.49  127.52  492.38   127.4   507.3  128.43  532.17  128.45
  557.04  127.77  571.96  128.65  591.85  128.37  606.77  128.93  656.51  127.99
  671.43  128.12  681.38  128.92  691.32  128.57  716.19  129.07  726.14  127.61
   770.9  127.58  800.74  128.04   845.5  127.85  894.49  127.93  920.11   128.3
     950  128.15     955  127.82     960  127.34     965  126.75     970  126.34
     975  125.33     980  124.29     985  123.38     990  122.53     995  121.63
    1000  120.14    1005  118.25 1007.69  116.61 1014.51  114.13 1015.17  111.97
 1015.93  110.82 1034.39  109.74 1034.47  110.98 1035.31  111.92 1035.85  112.95
 1042.78  116.93 1048.13   115.9    1055  118.62    1060  120.62    1065  121.81
    1070  122.68    1080  124.52    1085  125.41    1090  126.21    1095  126.82
    1100  127.33    1105  127.68    1110  127.81 1114.98   127.8 1119.96  127.76
 1124.95  127.62 1129.93  127.53 1134.91  127.32 1139.89  127.02 1144.87  126.92
 1169.78   127.4  1194.7  126.79 1204.66   127.2  1249.5  126.72 1294.34  126.55
 1319.25  126.13 1344.16  126.33  1359.1  126.03 1388.99   126.2 1428.85  126.84
 1448.78  126.94 1463.73   126.5 1473.69  126.85 1538.46  127.09  1692.9  125.99
 1702.86  125.52 1727.77  126.25 1797.52  126.77 1817.45  126.51 1827.42   127.1
 1847.34  127.05 1862.29  127.45  1887.2  126.93 1927.06  127.11 1937.02  126.69
 1951.97     127 1976.88  126.61  1996.8  126.95 2041.64  126.75 2061.57  126.23
 2146.27  126.98 2171.18  127.54 2196.09  127.63 2225.98  128.11  2305.7  128.65
 2315.66  129.15 2335.59   129.1 2370.47  129.66 2380.43   129.5 2425.27  129.91
 2435.23  130.31 2455.16  129.62 2480.07  129.54    2510  130.64    2525  130.39
    2550  131.34
BR U #Mann= 4
       0      .1  894.49     .07     950    .015    1110     .07
BR D #Sta/Elev= 124
       0  129.64   19.89  129.05   39.79  128.92   59.68  126.89   79.58  127.66
  104.44  127.96  134.29  128.97  154.18  128.47  203.92  129.01  253.65  128.88
  268.57   128.4  303.39  129.66  333.23  129.68  363.07  129.33  377.99  129.96
  402.86  129.24   432.7  129.32  457.57  129.45  472.49  128.67  492.38  128.52
   507.3   129.3  537.14  129.69  547.09  129.17  576.93   129.3  596.83  129.67
   601.8  129.16  626.67  129.93  636.61  129.45  711.22  129.43  736.08  129.53
  765.93  129.31  800.74  130.74  850.48  130.73  860.42   130.3  870.37  130.71
  887.83  129.42  900.21  126.75  905.18  126.46  910.16  126.44  915.13  126.36
  920.11  126.29  925.08  126.04  930.05  125.88  935.03  125.86     940   125.9
     945   126.1     950  126.18     955  126.12     960  125.81     965  125.19
  966.18  124.98  975.43  123.22   995.9   117.6 1004.31  117.14 1011.93  115.14
 1019.21  110.06 1029.15  109.01 1039.42   110.7 1044.43  115.29 1051.72  117.56
 1057.46  119.34 1069.28  121.38  1078.8  124.72    1080     125    1085  125.77
    1090  126.06    1095   126.2    1100  126.45    1105  126.71    1110   126.8
    1115  126.57    1120  126.44    1125  126.51    1130  126.53    1135  126.54
    1140  126.44    1145  126.39    1150  126.53    1155  126.77    1160  126.99
    1195  126.44    1210  126.87    1220  126.57    1265  127.33    1305  127.03
    1315  126.75    1345  127.41    1395  127.24    1435  128.18    1445   127.5
    1475  128.05    1510  127.72    1525  128.12    1595  128.14    1625  127.62
    1660   127.7    1685  127.98    1710  127.67    1740   127.9 1774.99  128.57
 1804.99  128.35 1829.99  128.82 1854.99  128.56 1929.99  128.56 1949.99  128.33
 2039.99     129 2064.99  128.67 2094.99  129.17 2184.99   129.6 2204.99   129.9
 2219.99  129.75 2259.99  130.43 2274.99   130.1 2284.99  130.54 2304.99     130
 2339.99  130.65 2369.99  130.43    2405  130.63    2415  131.29    2435  131.22
    2450   130.7    2480  130.84    2505  131.21    2550  131.29
BR D #Mann= 4
       0      .1  887.83     .07     950    .015    1110     .07
BC Design=,, 0 ,, 0 ,,,,,,
BC Use User HTab Curves=0
BC User HTab FreeFlow(D)= 0

Type RM Length L Ch R = 1 ,75005.7 ,34.31,46.01,59.84
BEGIN DESCRIPTION:
Downstream Section - 30" PIPELINE
END DESCRIPTION:
XS GIS Cut Line= 5
3019423.6624489413882317.60922213018484.0704961113882289.9137394
3018314.2148646913882282.90981643016924.8957929513882239.4102315
 3016877.6468717 13882223.053965
#Sta/Elev= 30
       0  129.64   39.79  128.92   59.68  126.89  134.29  128.97  268.57   128.4
  303.39  129.66  377.99  129.96  492.38  128.52  537.14  129.69  765.93  129.31
  800.74  130.74  870.37  130.71  887.83  129.42  905.18  126.46     950  126.18
     965  125.19   995.9   117.6 1004.31  117.14 1011.93  115.14 1019.21  110.06
 1029.15  109.01 1039.42   110.7 1044.43  115.29 1057.46  119.34 1069.28  121.38
    1080     125    1095   126.2    1435  128.18 2064.99  128.67    2550  131.29
#Mann= 4 ,-1 , 0
       0      .1       0  887.83     .07       0     950     .04       0
    1095     .07       0
#XS Ineff= 3 ,-1
       0  785.82  129.99  785.82  958.44  127.15 1091.43    2550  127.15
Permanent Ineff=
       F       F       F
Bank Sta=950,1095
XS Rating Curve= 0 ,0
Exp/Cntr=0.5,0.3