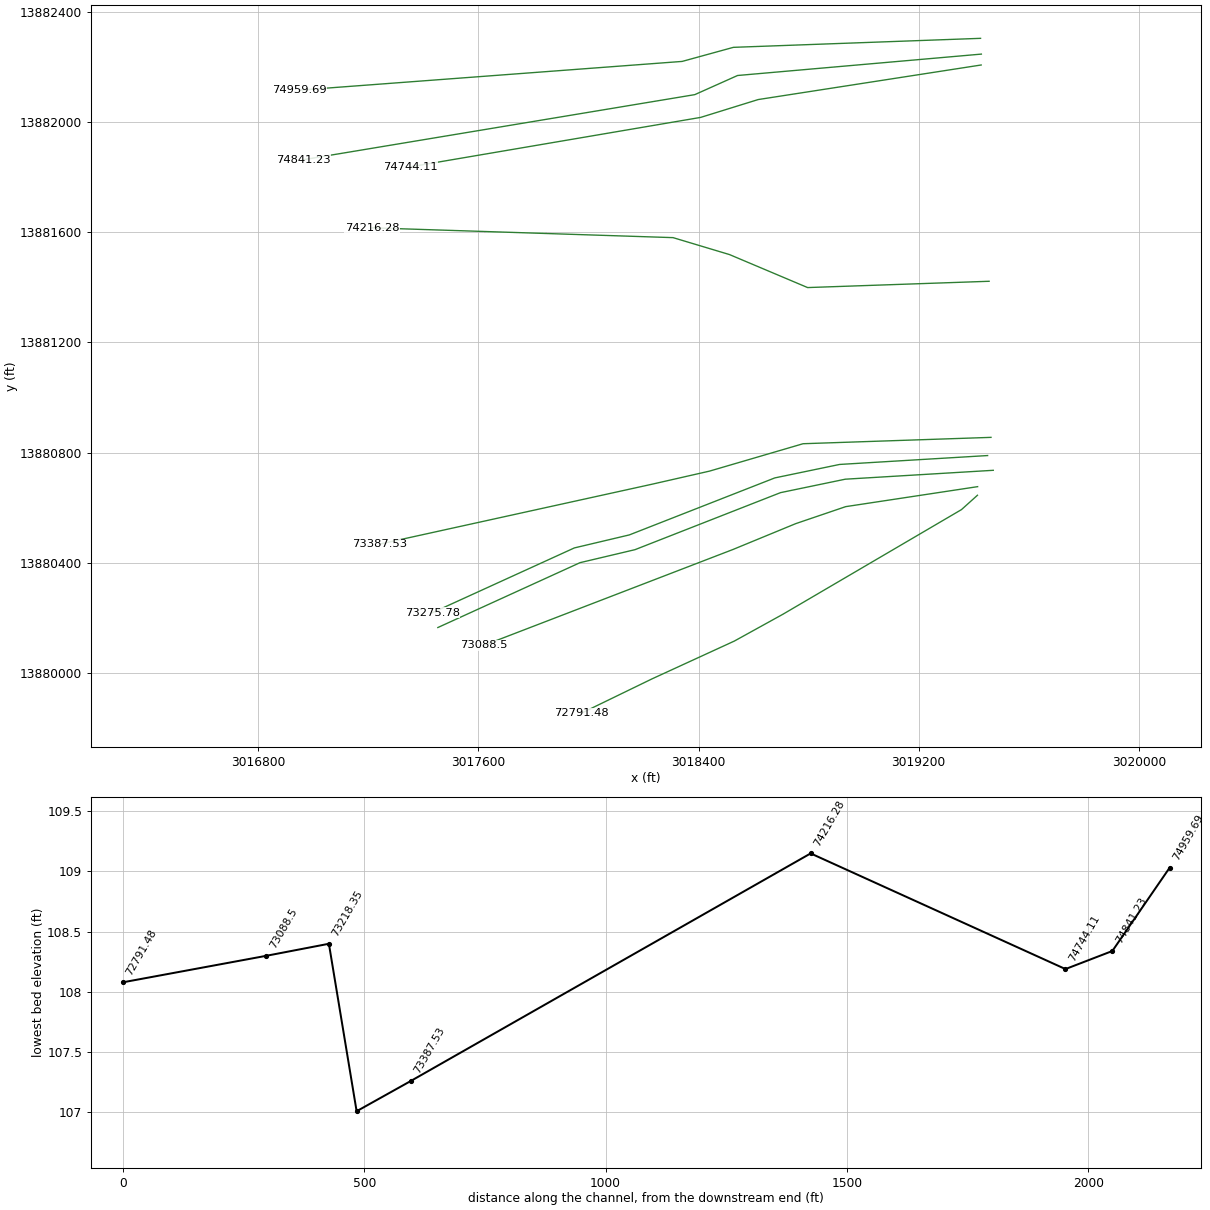
HEC-RAS study U100-00-00.prj: U100-00-00

--- U100-00-00.g01 (geometry) --- (continued)

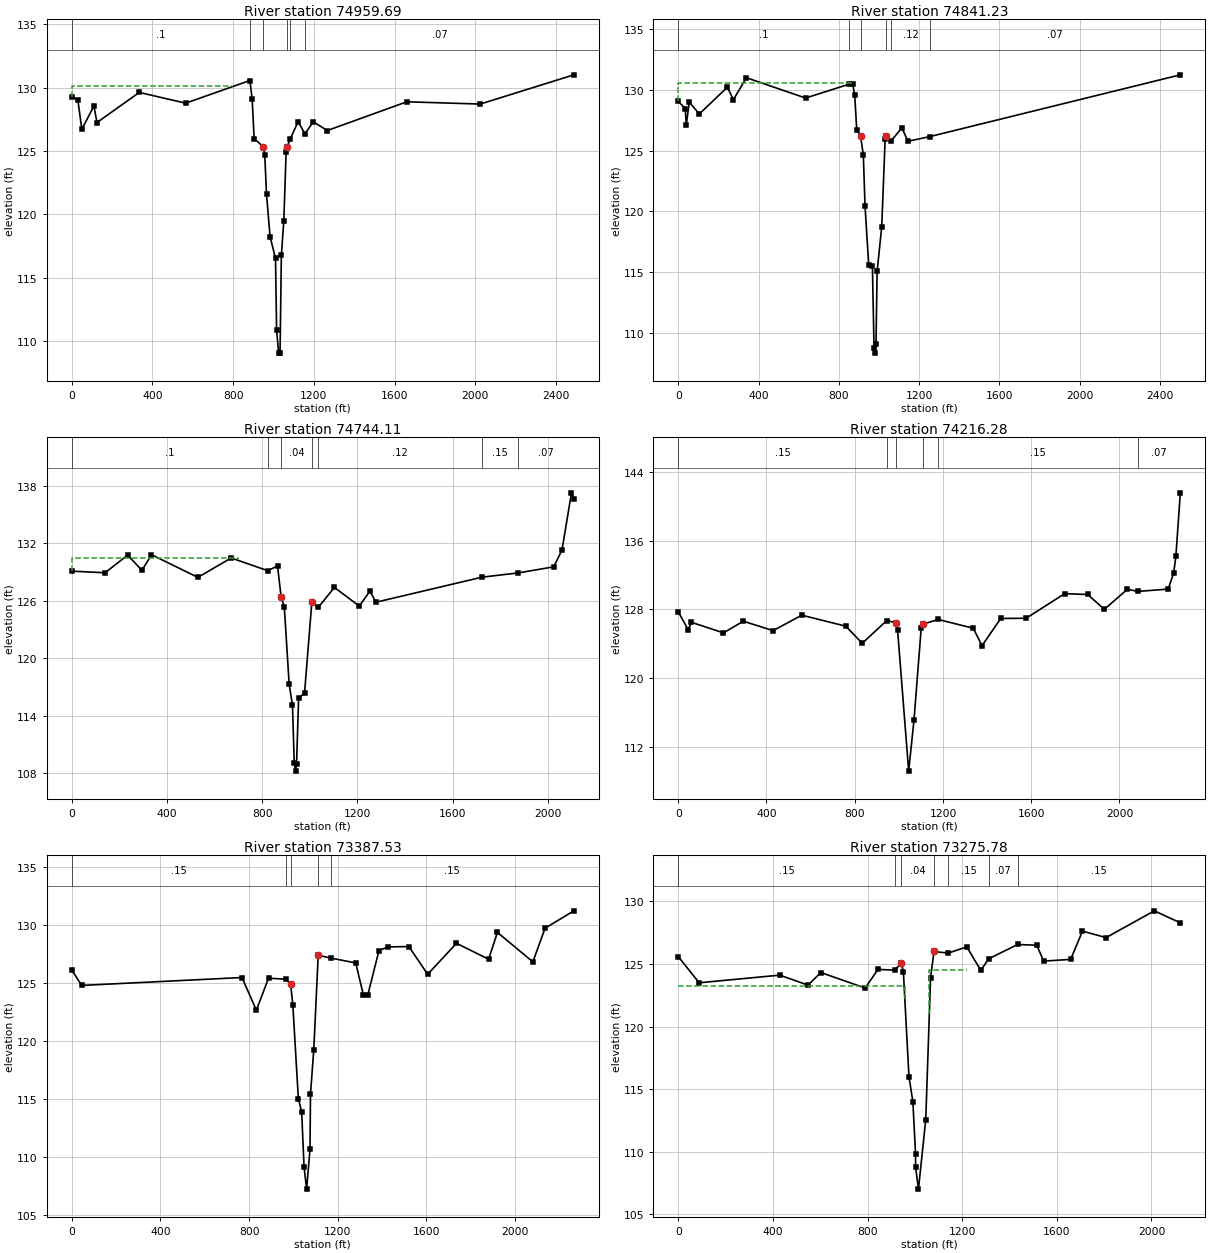
Type RM Length L Ch R = 1 ,74959.69,109.07,118.46,124.73
XS GIS Cut Line= 4
3019424.9701891113882305.29756693018526.7059095213882272.5591154
3018340.5051664413882221.40501823016948.3458772713882116.8674976
#Sta/Elev= 30
       0  129.29   29.96  129.05   49.94  126.72  109.86  128.56  124.84  127.25
  334.58  129.63  564.28  128.78  882.58  130.57  893.87  129.12  903.81  125.98
  948.37  125.35  956.25   124.7  965.03   121.6  982.61  118.24 1009.71  116.51
 1014.96  110.88  1025.2  109.03 1032.14  109.04 1038.66  116.76 1050.85   119.5
 1062.31  124.95  1067.2  125.32 1083.24  125.98 1121.88  127.33  1155.3  126.35
 1196.66  127.31 1266.47  126.62 1660.36  128.89 2024.34  128.71 2488.03  131.02
#Mann= 6 ,-1 , 0
       0      .1       0  882.58     .07       0  948.37     .04       0
  1067.2     .07       0 1083.24     .12       0  1155.3     .07       0
#XS Ineff= 1 ,-1
       0  793.99  130.13
Permanent Ineff=
       F
Bank Sta=948.37,1067.2
XS Rating Curve= 0 ,0
Exp/Cntr=0.3,0.1

Type RM Length L Ch R = 1 ,74841.23,101.98,97.12,88.8
XS GIS Cut Line= 4
3019427.8894746213882248.00503063018541.90207335 13882170.250921
 3018386.393854213882100.68150643016963.97084603 13881864.263344
#Sta/Elev= 30
       0  129.07   34.98  128.45   39.97   127.1   54.96     129  104.93  128.02
  244.83  130.22  274.81   129.2  339.77     131  634.57  129.33  851.41  130.47
  869.41   130.5   879.4  129.54  889.39  126.73  908.86  126.18   922.3  124.63
  930.73  120.46  948.98  115.61  967.58   115.5  975.62  108.75   980.3  108.34
  985.33  109.06  990.99  115.06 1013.96  118.74 1030.92  125.95 1035.42  126.19
 1060.12   125.8 1114.64  126.88 1144.57  125.77 1254.25  126.16  2501.7  131.24
#Mann= 6 ,-1 , 0
       0      .1       0  851.41     .07       0  908.86     .04       0
 1035.42     .07       0 1060.12     .12       0 1254.25     .07       0
#XS Ineff= 1 ,-1
       0  864.41  130.55
Permanent Ineff=
       F
Bank Sta=908.86,1035.42
XS Rating Curve= 0 ,0
Exp/Cntr=0.3,0.1

Type RM Length L Ch R = 1 ,74744.11,549.76,527.83,483.52
Node Name=T
XS GIS Cut Line= 4
3019427.1699878613882208.46016223018616.9800071913882082.8603478
3018407.8003074413882017.98810223017351.9713823613881838.2112308
#Sta/Elev= 30
       0   129.1  139.98  128.93  234.96  130.78  294.95  129.18  334.95  130.82
  529.91  128.45  669.89  130.48  823.39  129.15  864.67  129.64   879.6  126.44
  893.13  125.34  913.61  117.27  927.49  115.07  934.94  109.02  940.39  108.19
  944.66  108.97  953.33  115.81  978.26  116.37 1009.01  125.91 1035.86  125.31
 1103.64   127.4 1208.25  125.45 1253.08  127.02 1277.99  125.85 1724.07  128.47
 1877.14  128.92 2025.22  129.55 2060.09  131.31 2099.94  137.29  2109.9  136.67
#Mann= 7 ,-1 , 0
       0      .1       0  823.39     .07       0   879.6     .04       0
 1009.01     .07       0 1035.86     .12       0 1724.07     .15       0
 1877.14     .07       0
#XS Ineff= 1 ,-1
       0  699.89  130.52
Permanent Ineff=
       F
Bank Sta=879.6,1009.01
XS Rating Curve= 0 ,0
Exp/Cntr=0.3,0.1

Type RM Length L Ch R = 1 ,74216.28,795.63,828.75,856.15
XS GIS Cut Line= 5
3019456.0219642813881422.43483143018796.5114722713881399.5588928
3018512.4001638613881519.55012273018307.3900751913881581.0499997
 3017214.512339713881616.6352303
#Sta/Elev= 30
       0   127.7   44.99  125.63   59.99  126.48  204.97  125.25  294.96  126.61
  429.94  125.51  559.92  127.31   759.4  126.03  834.01  124.04  945.08  126.68
  988.23  126.43  994.38  125.54 1044.56  109.15 1068.71  115.12  1101.3   125.8
 1107.69  126.26 1178.42  126.81 1337.14  125.79 1377.08  123.76 1461.96  126.93
  1576.8  126.95 1751.55  129.82 1856.41  129.72  1931.3  127.99 2036.15  130.33
 2082.87  130.08 2220.89  130.35 2245.86  132.24 2255.84   134.2 2275.82  141.56
#Mann= 6 ,-1 , 0
       0     .15       0  945.08     .07       0  988.23     .04       0
 1107.69     .07       0 1178.42     .15       0 2082.87     .07       0
Bank Sta=988.23,1107.69
XS Rating Curve= 0 ,0
Exp/Cntr=0.3,0.1

Type RM Length L Ch R = 1 ,73387.53,106.05,111.75,119.66
Node Name=S
XS GIS Cut Line= 5
3019462.9035121913880855.20794743018779.98985177 13880832.100054
3018440.27990128 13880732.6199383018231.7199509413880685.1000199
3017241.2288216913880467.1611513
#Sta/Elev= 30
       0  126.15   44.89  124.82  768.06   125.5  832.87  122.68  887.71  125.44
  965.63  125.36  987.42  124.95   997.4  123.15 1022.32  115.06 1037.28  113.92
 1048.03  109.18 1059.71  107.26 1074.91  110.71 1077.08  115.44    1092  119.29
  1111.9  127.42 1168.01  127.18 1281.16  126.76 1316.13  123.97 1336.12  124.03
 1386.08  127.82 1426.04  128.14 1520.97  128.17  1605.9  125.78 1735.79  128.45
 1880.68  127.08 1920.65  129.39 2080.52  126.85 2135.47  129.75 2265.37  131.25
#Mann= 5 ,-1 , 0
       0     .15       0  965.63     .07       0  987.42     .04       0
  1111.9     .07       0 1168.01     .15       0
#XS Ineff= 2 ,-1
       0  851.67  123.28 1268.59 2265.37  124.49
Permanent Ineff=
       F       F
Bank Sta=987.42,1111.9
XS Rating Curve= 0 ,0
Exp/Cntr=0.5,0.3

Type RM Length L Ch R = 1 ,73275.78,57.43,57.43,57.47
BEGIN DESCRIPTION:
Upstream Section - AUTUMN HILLS DR
END DESCRIPTION:
XS GIS Cut Line= 6
3019450.5452691913880789.10867023018912.6713449513880756.7865563
3018677.2997684513880707.88901633018148.5422957813880500.6955331
3017948.8077871113880453.45547013017432.0365109413880217.6967553
#Sta/Elev= 30
       0   125.6   88.35   123.5  429.29  124.11  548.83  123.31  602.49  124.32
  790.05  123.08  844.26  124.57  914.34  124.51  942.82  125.06   951.5  124.39
  975.15     116  991.76  113.99 1003.01  109.83 1003.24  108.78 1015.22  107.01
 1046.07  112.55 1066.51   123.9 1081.05     126 1140.51  125.87 1219.52  126.37
 1278.86  124.49 1312.19  125.42 1434.68  126.56 1515.47   126.5 1544.37  125.23
 1658.64  125.37 1708.46  127.63 1808.11  127.11  2012.4  129.25 2122.01  128.29
#Mann= 7 ,-1 , 0
       0     .15       0  914.34     .07       0  942.82     .04       0
 1081.05     .07       0 1140.51     .15       0 1312.19     .07       0
 1434.68     .15       0
#XS Ineff= 3 ,-1
       0   957.6  123.28 1061.26 1219.52  124.49 1219.52 2122.01  125.64
Permanent Ineff=
       F       F       F
Bank Sta=942.82,1081.05
XS Rating Curve= 0 ,0
Exp/Cntr=0.5,0.3

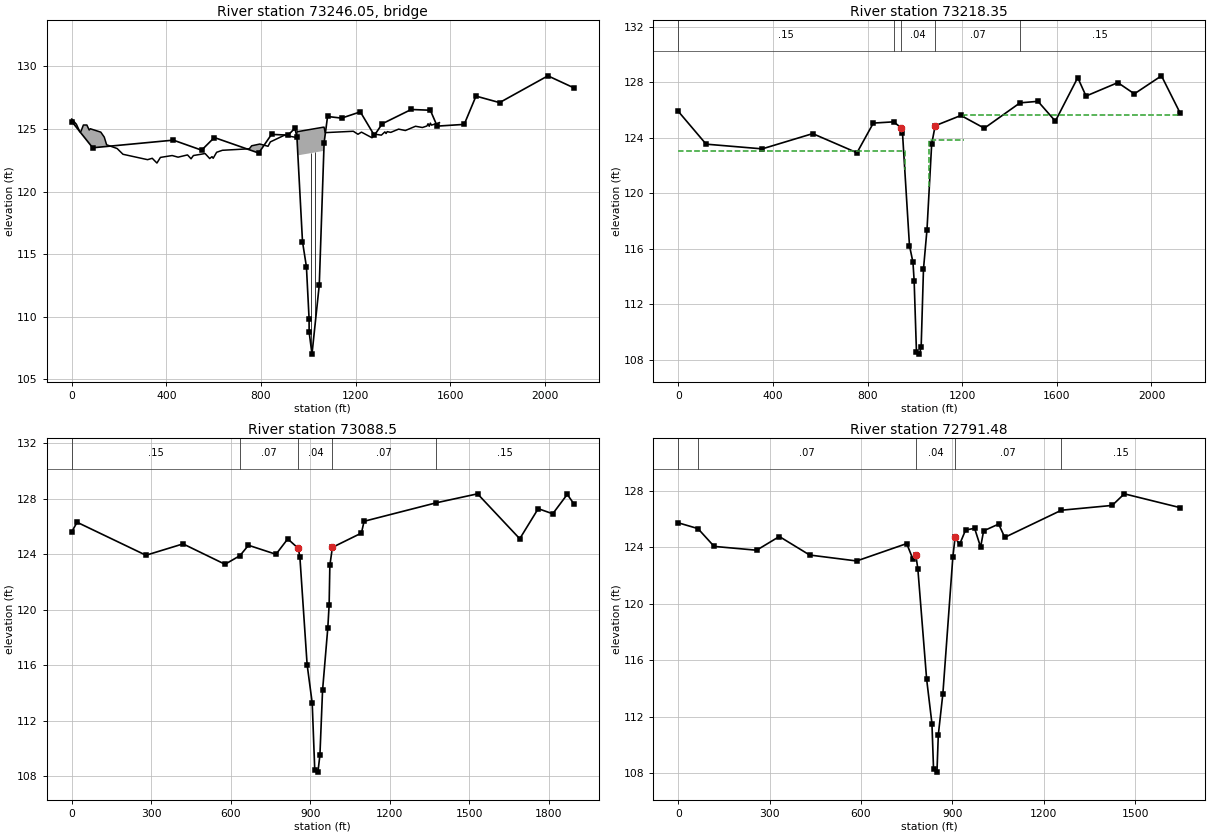
Type RM Length L Ch R = 3 ,73246.05,,,
BEGIN DESCRIPTION:
AUTUMN HILLS DR
END DESCRIPTION:
Node Name=AUTUMN HILLS DR
Bridge Culvert--1,0,-1,-1, 0
Deck Dist Width WeirC Skew NumUp NumDn MinLoCord MaxHiCord MaxSubmerge Is_Ogee
9.5,36,2.6,0, 60, 60, , , 0.98, 0, 0,0,,
       0   19.63   34.36   39.27   49.08   63.81   73.62   78.53  122.71  137.43
  147.28  191.78   216.5  320.34  340.11  359.89  374.72   424.3  449.25  489.17
  504.14  514.12  563.46  582.97  592.73  597.61  612.24  636.63  750.49  760.39
  794.98  829.47  839.33  898.47  947.75  952.67   957.6 1061.26 1066.21 1071.16
 1189.84 1209.62 1224.46 1268.97  1283.8 1308.53 1323.37 1328.31 1333.26 1348.09
 1381.39 1409.93 1452.86 1481.76 1501.02 1505.84 1510.66 1515.47 1520.29    1554
   125.8  125.38  124.77  124.83  125.32  125.32  124.92  125.02  124.75  124.35
  123.74  123.44  122.98  122.55  122.66  122.28  122.73  122.88  122.75  122.93
  122.62  122.88  123.04  122.64  122.79  122.66  123.14   123.3  123.42  123.66
   123.8  123.62  123.97   124.5  124.33  124.81   124.8  125.14  125.15  124.71
  124.82  124.58  124.75   124.3  124.58  124.51  124.77  124.64  124.79  124.73
  124.99  124.88  125.22  125.12  125.24  125.42  125.22  125.47  125.31  125.51
       0       0       0       0       0       0       0       0       0       0
       0       0       0       0       0       0       0       0       0       0
       0       0       0       0       0       0       0       0       0       0
       0       0       0       0       0       0   122.9  123.24       0       0
       0       0       0       0       0       0       0       0       0       0
       0       0       0       0       0       0       0       0       0       0
       0   19.63   34.36   39.27   49.08   63.81   73.62   78.53  122.71  137.43
  147.28  191.78   216.5  320.34  340.11  359.89  374.72   424.3  449.25  489.17
  504.14  514.12  563.46  582.97  592.73  597.61  612.24  636.63  750.49  760.39
  794.98  829.47  839.33  898.47  947.75  952.67   957.6 1061.26 1066.21 1071.16
 1189.84 1209.62 1224.46 1268.97  1283.8 1308.53 1323.37 1328.31 1333.26 1348.09
 1381.39 1409.93 1452.86 1481.76 1501.02 1505.84 1510.66 1515.47 1520.29    1554
   125.8  125.38  124.77  124.83  125.32  125.32  124.92  125.02  124.75  124.35
  123.74  123.44  122.98  122.55  122.66  122.28  122.73  122.88  122.75  122.93
  122.62  122.88  123.04  122.64  122.79  122.66  123.14   123.3  123.42  123.66
   123.8  123.62  123.97   124.5  124.33  124.81   124.8  125.14  125.15  124.71
  124.82  124.58  124.75   124.3  124.58  124.51  124.77  124.64  124.79  124.73
  124.99  124.88  125.22  125.12  125.24  125.42  125.22  125.47  125.31  125.51
       0       0       0       0       0       0       0       0       0       0
       0       0       0       0       0       0       0       0       0       0
       0       0       0       0       0       0       0       0       0       0
       0       0       0       0       0       0   122.8  123.14       0       0
       0       0       0       0       0       0       0       0       0       0
       0       0       0       0       0       0       0       0       0       0
Pier Skew, UpSta & Num, DnSta & Num=  ,1012.22, 2 ,1012.22, 2 , 0 , 0 , 0 ,,
     1.4     1.4
     105   129.5
     1.4     1.4
     105   129.5
Pier Skew, UpSta & Num, DnSta & Num=  ,1028.82, 2 ,1028.82, 2 , 0 , 0 , 0 ,,
     1.4     1.4
     105   129.5
     1.4     1.4
     105   129.5
Abutment Skew #Up #Dn= , 2 , 2
  957.32 1001.72
   122.9   110.3
  957.32 1001.72
   122.8   110.2
Abutment Skew #Up #Dn= , 2 , 2
 1030.72 1064.01
  110.38  123.25
 1030.72 1064.01
  110.28  123.15
BR Coef=-1 , 1 , 1 ,0.9, 0 ,,,0.8,-1,1.2,0,
WSPro=,,,, 1 ,,,, 0 ,,,, 0 ,,,,-1 ,-1 ,-1 , 0 , 0 , 0 , 0 , 0
BC Design=,, 0 ,, 0 ,,,,,,
BC Use User HTab Curves=0
BC User HTab FreeFlow(D)= 0

Type RM Length L Ch R = 1 ,73218.35,128.62,129.85,129.67
BEGIN DESCRIPTION:
Downstream Section - AUTUMN HILLS DR
END DESCRIPTION:
XS GIS Cut Line= 6
3019471.1833512813880735.51691383018933.30942702   13880703.1948
3018697.93785052  13880654.297263018169.1803778613880447.1037768
3017969.4458691913880399.86371383017452.6745930313880164.1049989
#Sta/Elev= 30
       0  125.92   117.8  123.55  354.95  123.21  568.34  124.31  755.44  122.93
  824.54  125.07  910.58  125.16  942.82  124.72  947.75  124.38  977.32  116.23
   992.1  115.02  997.03   113.7 1006.88  108.54 1019.08   108.4 1026.65  108.89
 1036.54  114.54 1051.37  117.39 1071.16  123.56 1085.99  124.88 1194.79  125.62
 1293.69   124.7 1444.47  126.53 1520.29  126.64 1593.86  125.21 1688.53  128.35
 1723.41  127.02 1857.94  127.99 1927.69  127.18 2042.29  128.48 2122.01  125.77
#Mann= 5 ,-1 , 0
       0     .15       0  910.58     .07       0  942.82     .04       0
 1085.99     .07       0 1444.47     .15       0
#XS Ineff= 3 ,-1
       0   957.6  123.08 1061.26 1209.62  123.84 1209.62 2122.01  125.64
Permanent Ineff=
       F       F       F
Bank Sta=942.82,1085.99
XS Rating Curve= 0 ,0
Exp/Cntr=0.5,0.3

Type RM Length L Ch R = 1 ,73088.5 ,288.39,297.03,302.83
XS GIS Cut Line= 5
 3019414.246129213880676.0819934 3018934.847481713880603.4459838
3018753.2572936913880541.70496553018524.7259266113880447.5660462
 3017618.619799213880098.9273078
#Sta/Elev= 30
       0  125.63   19.99  126.32  279.92  123.94  419.89  124.76  578.31  123.29
   634.6  123.91  666.83  124.66  770.59  124.01  815.08  125.12  854.63  124.44
  860.76  123.83   888.1  116.06  907.33  113.29  916.94  108.47  928.84   108.3
  936.44  109.53  946.37  114.19  966.23  118.71  971.19  120.35  973.95  123.21
  983.58  124.51 1093.11  125.54 1103.07  126.39 1374.72  127.72 1531.24  128.37
 1690.56  125.13 1760.26   127.3 1815.03  126.93  1869.8  128.33 1894.69  127.65
#Mann= 5 ,-1 , 0
       0     .15       0   634.6     .07       0  854.63     .04       0
  983.58     .07       0 1374.72     .15       0
#XS Ineff= 1 ,-1
       0  419.89  124.76
Permanent Ineff=
       F
Bank Sta=854.63,983.58
XS Rating Curve= 0 ,0
Exp/Cntr=0.3,0.1

Type RM Length L Ch R = 1 ,72791.48,169.07,184.43,198.72
XS GIS Cut Line= 6
3019413.6588600313880644.8376333 3019355.606482713880592.6730394
3018706.9201160213880212.53994143018530.0398923613880114.8600187
3018232.0598452813879978.04992493017972.8008493613879852.1646779
#Sta/Elev= 30
       0  125.72   64.67  125.31  117.86  124.05  257.21  123.78  331.86  124.75
   431.4  123.44  585.68  123.02  749.91  124.25  769.91  123.17  779.91  123.42
  786.49  122.47  815.34  114.66  832.77  111.52  838.01  108.31  849.23  108.08
  853.66  110.71  868.72  113.64  901.33  123.28  908.76  124.69  923.54  124.19
  943.26  125.21  972.83  125.33  992.54     124  1002.4  125.15 1051.84  125.63
 1071.71  124.69 1257.71  126.61 1424.45  126.95  1464.2  127.77 1648.06  126.79
#Mann= 5 ,-1 , 0
       0     .15       0   64.67     .07       0  779.91     .04       0
  908.76     .07       0 1257.71     .15       0
#XS Ineff= 1 ,-1
       0  331.86  124.75
Permanent Ineff=
       F
Bank Sta=779.91,908.76
XS Rating Curve= 0 ,0
Exp/Cntr=0.3,0.1