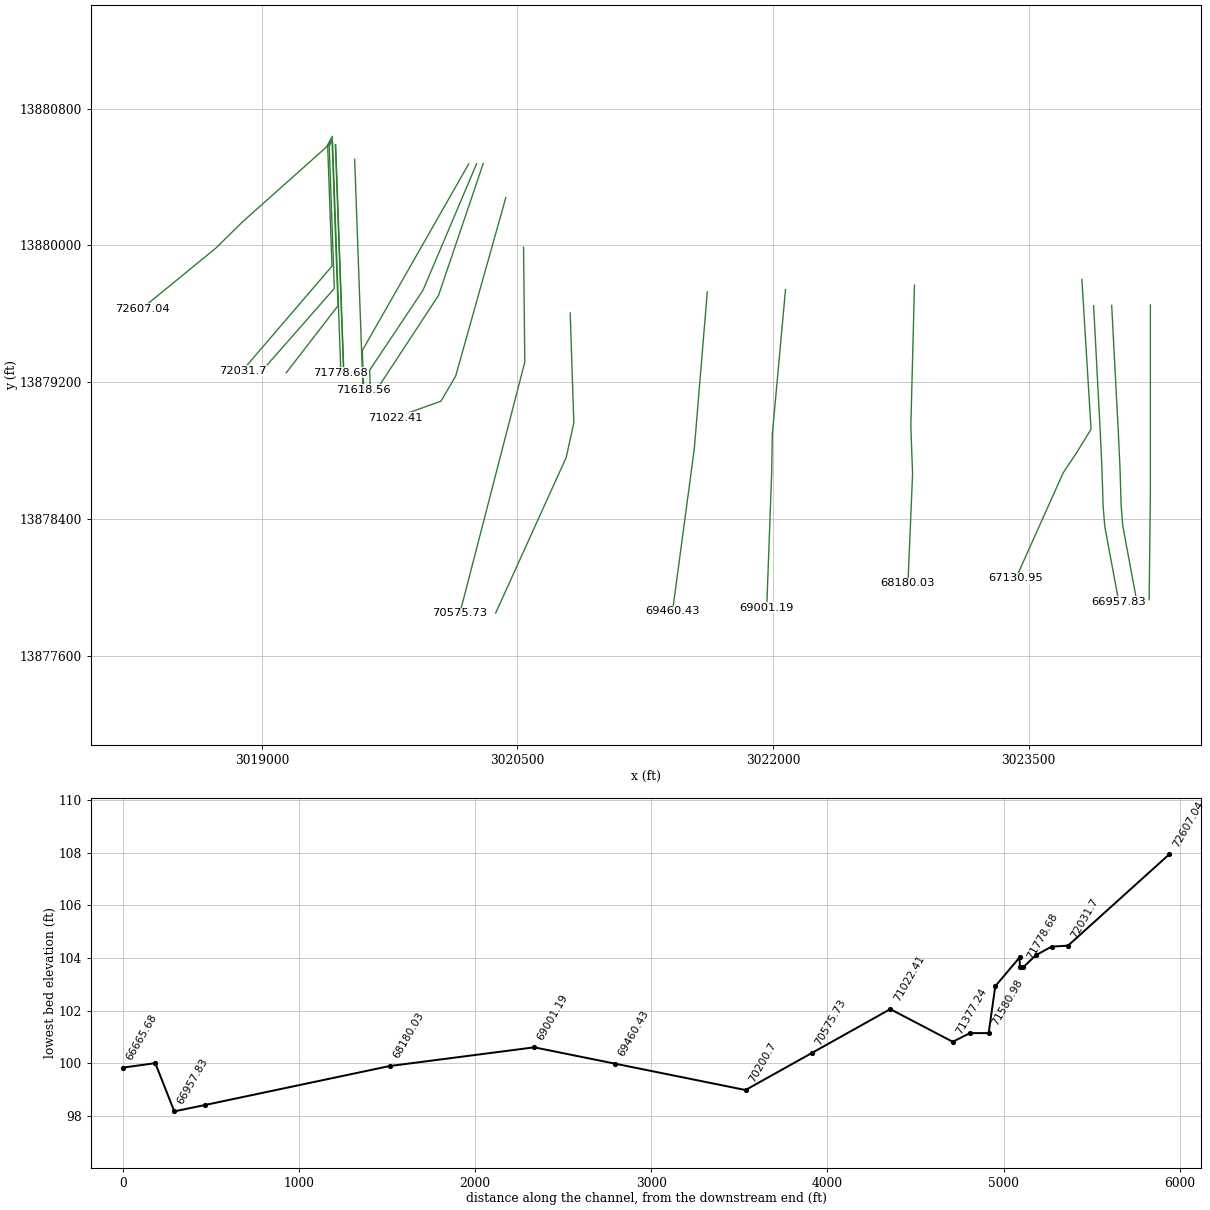
HEC-RAS study U100-00-00.prj: U100-00-00

--- U100-00-00.g01 (geometry) --- (continued)

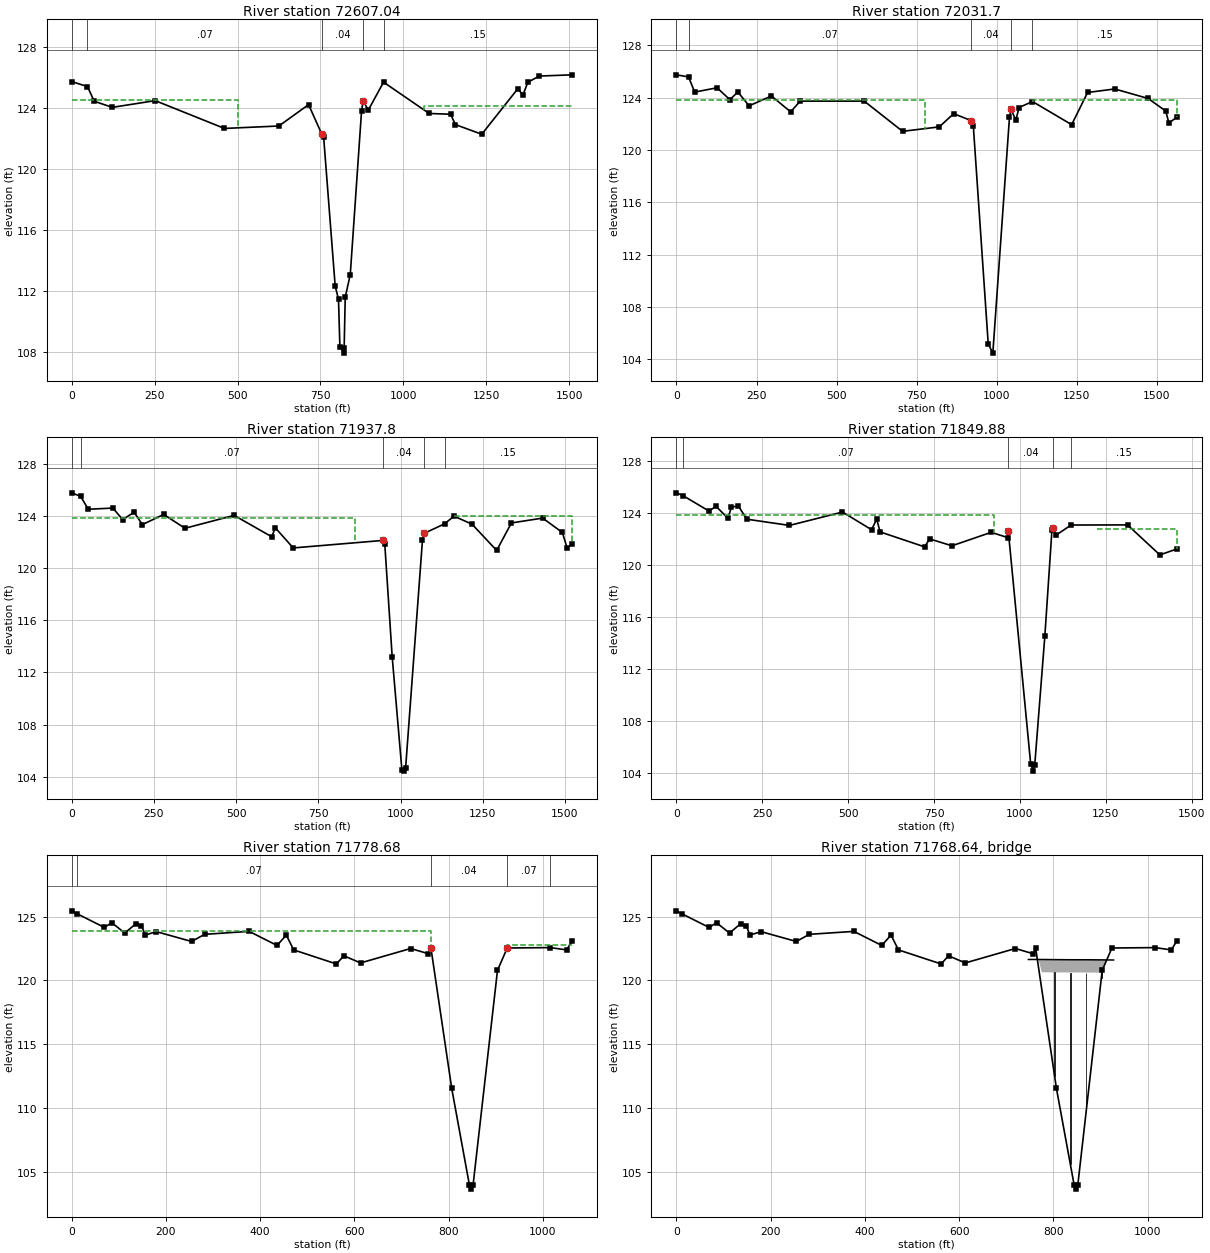
Type RM Length L Ch R = 1 ,72607.04,570.32,575.35,579.02
XS GIS Cut Line= 5
3019413.4980991913880636.28450083019377.2094578613880573.2724877
3018889.9601042713880140.85996673018729.3600317813879983.6900054
3018295.0899029413879630.1001614
#Sta/Elev= 30
       0  125.72   47.62  125.39   67.87  124.43  122.44  124.03  251.74  124.47
   460.6  122.65  624.71  122.81  714.22  124.21  754.13  122.27  759.61  122.08
  794.41  112.32   804.4  111.47  808.57  108.36  820.24  107.94  821.44   108.3
   824.7   111.6  839.85  113.08  873.98  123.82  878.97  124.47  893.95  123.84
  940.22  125.68 1077.73  123.63 1142.16  123.58 1157.03   122.9 1236.32  122.27
 1345.35  125.26 1360.22  124.82 1375.09  125.67 1409.78  126.08  1508.9  126.16
#Mann= 5 ,-1 , 0
       0     .15       0   47.62     .07       0  754.13     .04       0
  878.97     .07       0  940.22     .15       0
#XS Ineff= 2 ,-1
       0  500.39  124.48 1062.87  1508.9  124.12
Permanent Ineff=
       F       F
Bank Sta=754.13,878.97
XS Rating Curve= 0 ,0
Exp/Cntr=0.3,0.1

Type RM Length L Ch R = 1 ,72031.7 ,94.52,93.9,93.21
XS GIS Cut Line= 4
3019413.3202780313880626.83241993019386.0503194513880576.7249086
3019411.3393108513879878.3053737 3018885.061820113879267.3705719
#Sta/Elev= 30
       0  125.75   37.91  125.59   57.05  124.43  126.94  124.76  166.87  123.85
  191.83  124.44  226.77  123.38  296.66  124.13  356.57  122.92  386.52  123.74
   586.2  123.74  706.01  121.43  820.63  121.77  865.43  122.78  920.18  122.25
  926.84  121.82  973.34  105.17  987.69  104.47 1039.64   122.5 1044.62   123.1
 1059.55  122.28 1069.51  123.25  1111.4  123.71 1233.77  121.94 1283.54   124.4
 1368.16  124.67 1472.69  123.94 1527.44  122.98  1537.4  122.06 1562.28  122.52
#Mann= 5 ,-1 , 0
       0     .15       0   37.91     .07       0  920.18     .04       0
 1044.62     .07       0  1111.4     .15       0
#XS Ineff= 2 ,-1
       0  777.27   123.8  1114.3 1562.28   123.8
Permanent Ineff=
       F       F
#Block Obstruct= 2 , 0
       0                 1472.69       0  123.94
Bank Sta=920.18,1044.62
XS Rating Curve= 0 ,0
Exp/Cntr=0.3,0.1

Type RM Length L Ch R = 1 ,71937.8 ,85.25,87.92,92.4
XS GIS Cut Line= 4
3019413.1211314513880616.23270363019394.8915091213880580.1770014
3019425.0236666913879747.99067373018995.7256407713879261.3066077
#Sta/Elev= 30
       0  125.79   27.17  125.52   50.37  124.53  125.17  124.62  155.09  123.74
  189.99   124.3  214.93  123.35  279.75  124.13  344.57  123.07  494.17  124.06
  608.85  122.41  618.83  123.12  673.68  121.56  948.01  122.14  952.14  121.86
  974.65  113.22 1004.25  104.52 1009.25  104.43 1015.58  104.69 1066.73  122.14
 1072.82  122.69 1133.99  123.41 1162.67     124 1217.58  123.38 1292.46  121.37
 1337.39  123.48 1432.24  123.85 1492.15  122.75 1507.12  121.53  1522.1  121.88
#Mann= 5 ,-1 , 0
       0     .15       0   27.17     .07       0  948.01     .04       0
 1072.82     .07       0 1133.99     .15       0
#XS Ineff= 2 ,-1
       0  860.18  123.86 1162.67  1522.1     124
Permanent Ineff=
       F       F
#Block Obstruct= 2 , 0
       0                 1382.32       0  123.99
Bank Sta=948.01,1072.82
XS Rating Curve= 0 ,0
Exp/Cntr=0.3,0.1

Type RM Length L Ch R = 1 ,71849.88,5.36,71.2,131.32
Node Name=R
XS GIS Cut Line= 4
3019413.1381917713880607.64184153019412.5732322813880587.0815152
3019446.6177836113879646.84881563019142.7725907713879255.2429715
#Sta/Elev= 30
       0  125.54   18.87  125.33   95.24  124.13  115.15  124.51     150  123.58
  159.95  124.42  179.87  124.55  204.76  123.51  329.21  123.03  483.53  124.06
  568.15   122.7  583.09  123.51  593.04  122.53  722.47  121.38   737.4  121.99
  802.12  121.46  916.61   122.5  964.59  122.09  966.25  122.59  1031.3  104.69
 1038.57  104.11 1043.29  104.61 1072.59   114.5 1093.34  122.69 1095.24  122.87
 1105.16  122.28    1149  123.06 1313.33  123.07 1407.51  120.76 1457.08  121.22
#Mann= 5 ,-1 , 0
       0     .15       0   18.87     .07       0  966.25     .04       0
 1095.24     .07       0    1149     .15       0
#XS Ineff= 2 ,-1
       0  924.59  123.86 1224.12 1457.08  122.76
Permanent Ineff=
       F       F
#Block Obstruct= 2 , 0
       0                 1352.99       0  122.24
Bank Sta=966.25,1095.24
XS Rating Curve= 0 ,0
Exp/Cntr=0.5,0.3

Type RM Length L Ch R = 1 ,71778.68,17.96,20.35,53.55
BEGIN DESCRIPTION:
Upstream Section - 12" PIPELINE
END DESCRIPTION:
XS GIS Cut Line= 3
3019414.5870077813880601.93680043019416.3238809413880553.9683924
 3019463.3641412 13879254.819744
#Sta/Elev= 30
       0  125.45  10.906  125.23  69.345  124.15  85.105  124.52 112.686  123.71
 136.326  124.44 148.146   124.3 156.026  123.55 179.666  123.82 254.527  123.05
 282.108  123.61 376.669  123.84  435.77  122.74  455.47  123.55  471.23  122.39
 561.852  121.29 577.612  121.93 613.072  121.37 719.454   122.5 757.144  122.09
 762.566  122.51 806.584  111.54 843.952  104.02 847.608  103.66 851.942  103.99
 903.722  120.79 924.337  122.541015.998  122.571050.418  122.391062.239   123.1
#Mann= 5 ,-1 , 0
       0     .15       0  10.906     .07       0 762.566     .04       0
 924.337     .07       01015.998     .15       0
#XS Ineff= 2 ,-1
       0  762.57  123.86  924.341062.239  122.76
Permanent Ineff=
       F       F
Bank Sta=762.566,924.337
XS Rating Curve= 0 ,0
Skew Angle= 38
Exp/Cntr=0.5,0.3

Type RM Length L Ch R = 3 ,71768.64,,,
BEGIN DESCRIPTION:
12" PIPELINE
U00_800
END DESCRIPTION:
Node Name=12" PIPELINE
Bridge Culvert--1,0,-1,-1, 0
Deck Dist Width WeirC Skew NumUp NumDn MinLoCord MaxHiCord MaxSubmerge Is_Ogee
9,1,2.6,38, 7, 7, , , 0.98, 0, 0,0,,
 747.034 775.505 802.534 836.024 869.515 902.769 927.828
  121.64  121.64  121.63  121.62  121.62  121.61   121.6
  120.64  120.64  120.63  120.62  120.62  120.61  120.61
 747.034 775.505 802.534 836.024 869.515 902.769 927.828
  121.64  121.64  121.63  121.62  121.62  121.61   121.6
  120.64  120.64  120.63  120.62  120.62  120.61  120.61
Pier Skew, UpSta & Num, DnSta & Num=  ,802.534, 2 ,802.534, 2 , 0 , 0 , 0 ,,
     1.4     1.4
     100   121.3
     1.4     1.4
     100   121.3
Pier Skew, UpSta & Num, DnSta & Num=  ,836.024, 2 ,836.024, 2 , 0 , 0 , 0 ,,
     1.4     1.4
     100   121.3
     1.4     1.4
     100   121.3
Pier Skew, UpSta & Num, DnSta & Num=  ,869.515, 2 ,869.515, 2 , 0 , 0 , 0 ,,
     1.4     1.4
     100   121.3
     1.4     1.4
     100   121.3
Pier Skew, UpSta & Num, DnSta & Num=  ,901.981, 2 ,902.769, 2 , 0 , 0 , 0 ,,
     1.4     1.4
     100   121.3
     1.4     1.4
     100   121.3
BR Coef=-1 , 1 , 1 ,0.9, 0 ,,,0.8,-1,1.2,0,
WSPro=,,,, 1 ,,,, 0 ,,,, 0 ,,,,-1 ,-1 ,-1 , 0 , 0 , 0 , 0 , 0
BC Design=,, 0 ,, 0 ,,,,,,
BC Use User HTab Curves=0
BC User HTab FreeFlow(D)= 0

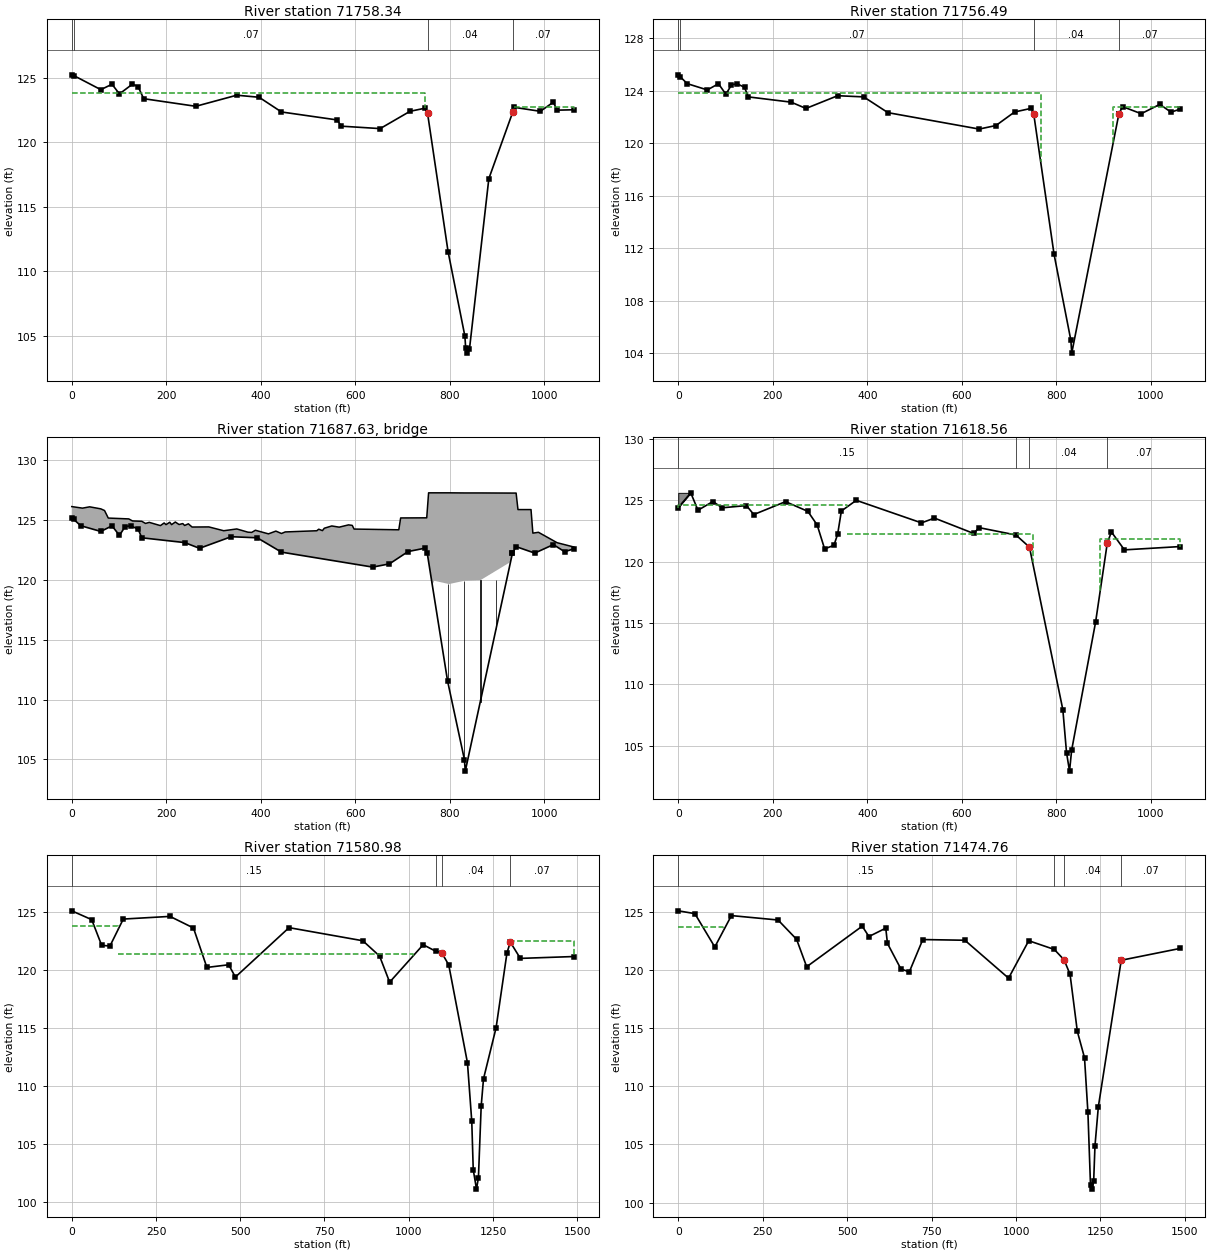
Type RM Length L Ch R = 1 ,71758.34,1.52,1.84,1.55
BEGIN DESCRIPTION:
Downstream Section - 12" PIPELINE
END DESCRIPTION:
XS GIS Cut Line= 3
3019431.15062295 13880589.2265243019432.88749611 13880541.258116
3019479.9277563513879242.1094676
#Sta/Elev= 30
       0  125.24   4.381  125.18  61.465  124.09  85.105  124.51 100.865  123.76
 128.446  124.52 140.266  124.33 152.086  123.39 262.408   122.8 349.089  123.66
 396.369   123.5  443.65  122.36 561.852  121.74 569.732  121.26 652.473  121.07
 715.514  122.41 747.034  122.65 752.716  122.26 796.104  111.54 831.651  104.99
 833.471  104.02 837.127  103.66 841.461  103.99 882.383  117.19  932.69  122.32
 936.157  122.72 991.318  122.411018.898  123.121026.778   122.51062.239  122.53
#Mann= 4 ,-1 , 0
       0     .15       0   4.381     .07       0 752.716     .04       0
  932.69     .07       0
#XS Ineff= 2 ,-1
       0  747.03  123.86  936.161062.239  122.76
Permanent Ineff=
       F       F
Bank Sta=752.716,932.69
XS Rating Curve= 0 ,0
Skew Angle= 38
Exp/Cntr=0.5,0.3

Type RM Length L Ch R = 1 ,71756.49,135.69,137.93,127.2
BEGIN DESCRIPTION:
Upstream Section - BARKER CYPRESS RD
END DESCRIPTION:
XS GIS Cut Line= 3
3019432.6434021113880588.08118513019434.3802752813880540.1127771
3019481.4205355213879240.9641287
#Sta/Elev= 30
       0  125.21    3.79  125.08  18.912  124.54  61.465  124.06  85.105  124.53
 100.865  123.73 112.686  124.45 124.506  124.53 140.266  124.26 148.146  123.53
 238.767  123.13 270.288  122.65 337.269  123.62 392.429  123.53  443.65  122.33
 636.713  121.08 672.173  121.35 711.574  122.38 747.034  122.66 752.117  122.23
 795.158  111.54 830.705  104.99 832.526  104.02 932.185  122.22 932.217  122.23
 940.097  122.79 979.497  122.251018.898  122.961042.538  122.371062.239   122.6
#Mann= 4 ,-1 , 0
       0     .15       0    3.79     .07       0 752.117     .04       0
 932.185     .07       0
#XS Ineff= 2 ,-1
       0 766.734  123.86 919.9711062.239  122.76
Permanent Ineff=
       F       F
Bank Sta=752.117,932.217
XS Rating Curve= 0 ,0
Skew Angle= 38
Exp/Cntr=0.5,0.3

Type RM Length L Ch R = 3 ,71687.63,,,
BEGIN DESCRIPTION:
BARKER CYPRESS RD
U00_800
END DESCRIPTION:
Node Name=BARKER CYPRESS
Bridge Culvert--1,0,-1,-1, 0
Deck Dist Width WeirC Skew NumUp NumDn MinLoCord MaxHiCord MaxSubmerge Is_Ogee
11.5,92,2.6,38, 60, 60, , , 0.98, 0, 0,0,,
       0  22.695  37.825  61.465  69.345  77.225 120.566 128.446 148.146 156.026
 163.906 187.547 195.427 199.367 207.247 211.187 219.067 226.947 234.827 238.767
 246.647 254.527 289.988 321.508 349.089 372.729 380.609 388.489  416.07  431.83
  443.65  451.53 518.511 522.451 530.331 534.271 550.031 565.792 585.492 593.372
 597.312 691.873 695.814 750.974 754.914 762.794 766.734 798.255 829.775 865.236
 928.277 932.217 936.157 940.097 944.037 971.617 975.557 987.3781026.7781062.239
  126.14  126.01  126.12  125.95  125.81  125.18  125.11  124.94  124.91  124.73
  124.82  124.55  124.77  124.63  124.83  124.63  124.85  124.64  124.72  124.56
   124.7  124.43  124.44  124.12  124.27     124  123.98  124.16  123.86  124.09
  123.89  124.02  124.12  124.25  124.13  124.33  124.52  124.42  124.61  124.57
  124.26   124.2  125.19   125.2  127.29  127.29  127.29  127.29  127.28  127.28
  127.27  127.27  127.27  127.27  125.89  125.89  123.92  123.99  123.12  122.76
       0       0       0       0       0       0       0       0       0       0
       0       0       0       0       0       0       0       0       0       0
       0       0       0       0       0       0       0       0       0       0
       0       0       0       0       0       0       0       0       0       0
       0       0       0       0       0       0  119.94  119.66  119.93     120
  119.99  111.81       0       0       0       0       0       0       0       0
       0  57.525  69.345  77.225 120.566 128.446 136.326 144.206 148.146 156.026
 163.906 187.547 191.487 195.427 199.367 207.247 211.187 219.067 226.947 234.827
 238.767 246.647 254.527 289.988 297.868 309.688 321.508 349.089 372.729 380.609
 388.489 400.309  408.19  416.07  431.83  443.65  451.53 490.931 510.631 518.511
 526.391 640.653 652.473 687.933 691.873 719.454 723.394 727.334 731.274 861.296
 892.816 896.756 904.636 908.576 944.037 983.4371018.8981046.4781058.2981062.239
  126.14  125.99  125.81  125.18  125.11  124.94  124.97  124.82  124.91  124.73
  124.82  124.55  124.58  124.77  124.63  124.83  124.63  124.85  124.64  124.72
  124.56   124.7  124.43  124.44  124.28  124.33  124.12  124.27     124  123.98
  124.16     124  124.03  123.86  124.09  123.89  124.02     124   124.2  124.12
  124.26  124.21  124.91  125.04   125.8   125.8  127.08  127.13  127.15  127.14
  127.14  127.16  127.22  125.39  124.87  122.83  122.61  122.58  122.58  122.76
       0       0       0       0       0       0       0       0       0       0
       0       0       0       0       0       0       0       0       0       0
       0       0       0       0       0       0       0       0       0       0
       0       0       0       0       0       0       0       0       0       0
       0       0       0       0       0       0       0       0  119.94  120.05
  120.04       0       0       0       0       0       0       0       0       0
Pier Skew, UpSta & Num, DnSta & Num=  ,796.127, 2 ,763.661, 2 , 0 , 0 , 0 ,,
     1.2     1.2
     100     122
     1.2     1.2
     100     122
Pier Skew, UpSta & Num, DnSta & Num=  ,830.012, 2 ,797.309, 2 , 0 , 0 , 0 ,,
     1.2     1.2
     100     122
     1.2     1.2
     100     122
Pier Skew, UpSta & Num, DnSta & Num=  ,864.29, 2 ,830.642, 2 , 0 , 0 , 0 ,,
     1.2     1.2
     100     122
     1.2     1.2
     100     122
Pier Skew, UpSta & Num, DnSta & Num=  ,897.702, 2 ,861.296, 2 , 0 , 0 , 0 ,,
     1.2     1.2
     100     122
     1.2     1.2
     100     122
BR Coef=-1 , 1 , 1 ,1.25, 0 ,,,0.8,-1,2,0,
WSPro=,,,, 1 ,,,, 0 ,,,, 0 ,,,,-1 ,-1 ,-1 , 0 , 0 , 0 , 0 , 0
BC Design=,, 0 ,, 0 ,,,,,,
BC Use User HTab Curves=0
BC User HTab FreeFlow(D)= 0

Type RM Length L Ch R = 1 ,71618.56,95.68,37.58,4.34
BEGIN DESCRIPTION:
Downstream Section - BARKER CYPRESS RD
END DESCRIPTION:
XS GIS Cut Line= 3
3019544.3859607713880502.33627793019546.1228339413880454.3678699
3019593.1630941913879155.2192214
#Sta/Elev= 30
       0  124.41  26.477  125.62  41.765   124.2  73.285  124.91  92.985   124.4
 144.206  124.58 159.966  123.85 226.947   124.9 274.228  124.11 293.928     123
 309.688  121.05 329.389  121.34 337.269  122.25 345.149  124.14 376.669  125.01
 514.571  123.17 542.151  123.56 624.893  122.31 636.713  122.78 714.505  122.18
 743.094  121.19 813.708  107.94 821.533  104.43  827.86  102.93 832.297  104.63
 882.919  115.06 907.796  121.54 916.457  122.43 944.037  120.971062.239  121.24
#Mann= 4 ,-1 , 0
       0     .15       0 714.505     .07       0 743.094     .04       0
 907.796     .07       0
#XS Ineff= 3 ,-1
       0 356.969  124.63 356.969  749.54  122.29 892.8161062.239  121.88
Permanent Ineff=
       F       F       F
#Block Obstruct= 2 , 0
       0  26.477  125.62               0
Bank Sta=743.094,907.796
XS Rating Curve= 0 ,0
Skew Angle= 38
Exp/Cntr=0.5,0.3

Type RM Length L Ch R = 1 ,71580.98,109.77,106.23,83.69
XS GIS Cut Line= 4
 3020213.722548613880475.89472973020100.9904906213880279.0398084
3019589.1181547813879385.19907643019597.55613002 13879152.158532
#Sta/Elev= 30
       0  125.14   59.18  124.38   88.77  122.16  113.42  122.11  152.88  124.43
  291.54  124.66   361.2  123.66  401.01  120.26   465.7  120.49   485.6  119.43
  644.83  123.69  863.78  122.56  913.54  121.24  943.39  118.99 1042.91  122.22
 1081.18  121.64 1097.65  121.54 1118.73  120.48 1174.33  112.04 1187.13  106.99
 1191.48  102.83 1201.15  101.15 1206.91  102.15 1215.07  108.31 1221.95  110.66
 1259.29  115.06 1291.61  121.52 1301.54  122.44  1331.3  121.04 1490.07   121.2
#Mann= 4 ,-1 , 0
       0     .15       0 1081.18     .07       0 1097.65     .04       0
 1301.54     .07       0
#XS Ineff= 3 ,-1
       0  138.08  123.85  138.08 1013.06  121.38 1301.54 1490.07   122.5
Permanent Ineff=
       F       F       F
Bank Sta=1097.65,1301.54
XS Rating Curve= 0 ,0
Exp/Cntr=0.3,0.1

Type RM Length L Ch R = 1 ,71474.76,96.13,97.51,97.03
XS GIS Cut Line= 5
3020260.2788859513880477.19984523020158.1780402813880237.3430414
3019945.5259065313879737.77875193019632.3273859513879270.4906444
3019636.6738339413879150.4534829
#Sta/Elev= 30
       0  125.08   49.19  124.84  108.21  121.97  157.39  124.67  295.55  124.29
  350.34  122.63  380.23  120.27  544.61  123.76  564.53  122.87  614.34  123.59
  619.32  122.28  659.17  120.08  684.08  119.83  723.93  122.61  848.43  122.55
  977.86  119.29  1037.6  122.51 1113.21  121.76 1142.14  120.87 1159.87  119.62
 1181.44  114.71 1202.67  112.45 1212.76  107.74 1220.44  101.48 1224.97  101.15
 1229.81  101.86 1233.69  104.89 1243.66  108.24  1311.4  120.83 1486.28  121.85
#Mann= 4 ,-1 , 0
       0     .15       0 1113.21     .07       0 1142.14     .04       0
  1311.4     .07       0
#XS Ineff= 2 ,-1
       0   132.8  123.73   132.8 1022.67  121.33
Permanent Ineff=
       F       F
Bank Sta=1142.14,1311.4
XS Rating Curve= 0 ,0
Exp/Cntr=0.3,0.1

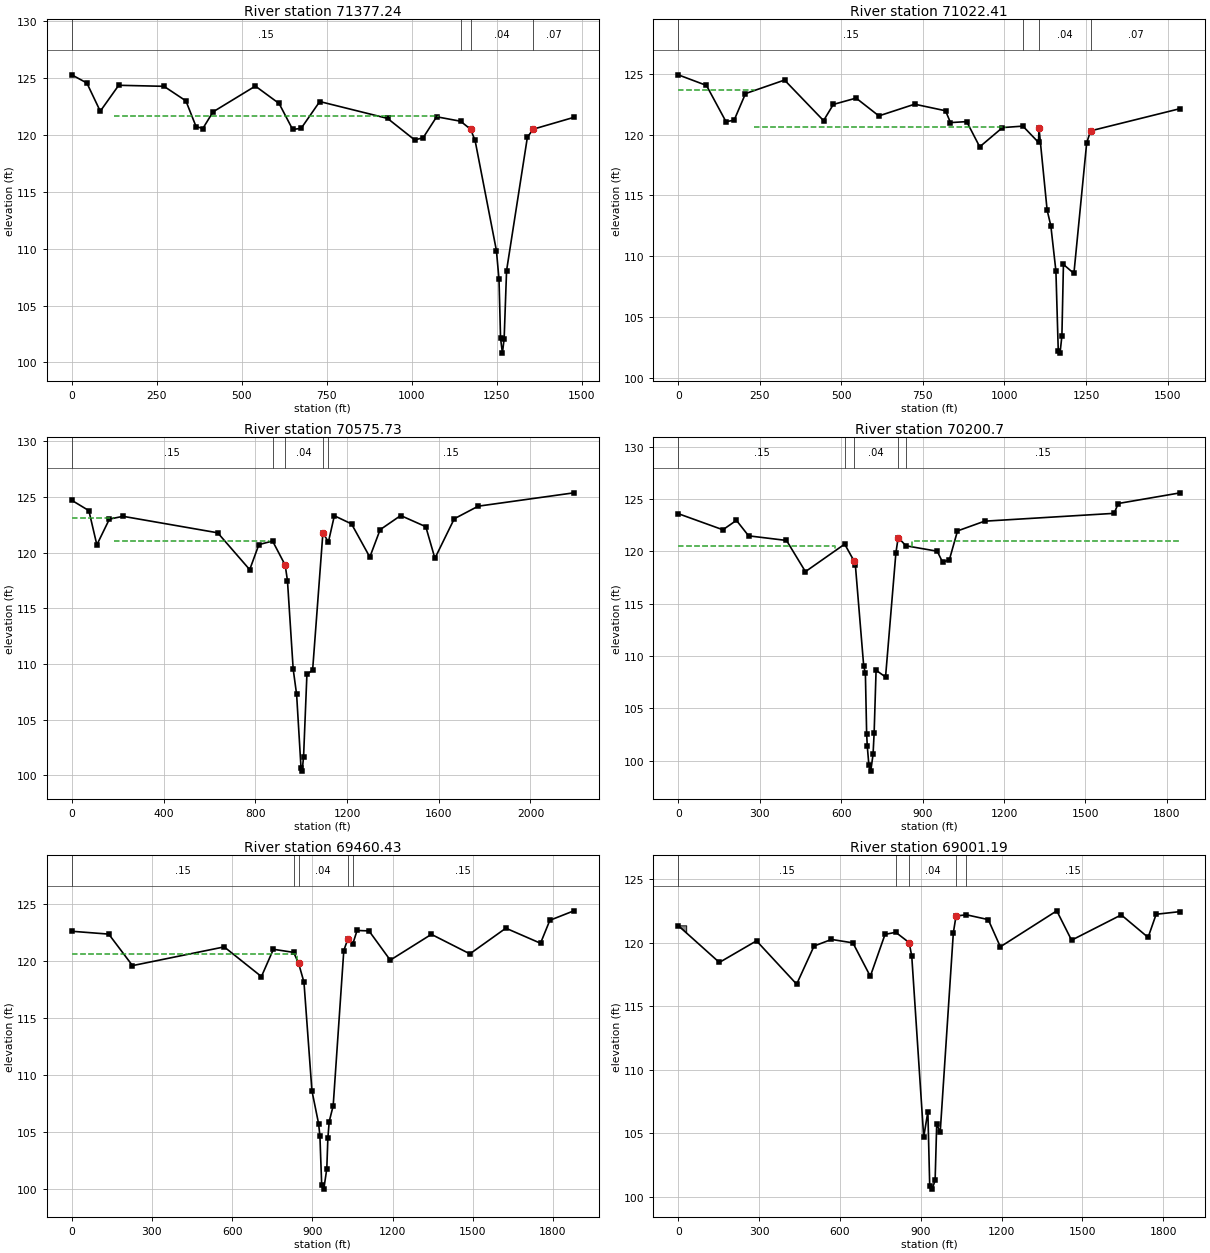
Type RM Length L Ch R = 1 ,71377.24,345.25,354.84,352.69
XS GIS Cut Line= 4
3020298.9776274413880478.28514493020202.0588580213880193.4622237
3020036.6625352813879707.3998756 3019672.115692213879153.8288043
#Sta/Elev= 30
       0  125.29   44.39  124.57   83.85  122.09   138.1  124.37  271.27  124.28
  335.75     123  365.66  120.74   385.6  120.57  415.51  122.03  540.13   124.3
  609.92  122.77   649.8  120.49  674.72  120.58  729.55  122.94  928.92  121.46
 1008.65  119.57 1033.57  119.75 1073.44   121.6  1143.9  121.21 1173.11  120.51
 1186.54  119.52 1249.31  109.84 1256.92  107.32 1261.52  102.12 1266.96  100.82
 1272.07  102.09 1279.21  108.08 1340.41   119.8 1357.51  120.51 1477.12  121.55
#Mann= 4 ,-1 , 0
       0     .15       0  1143.9     .07       0 1173.11     .04       0
 1357.51     .07       0
#XS Ineff= 2 ,-1
       0   123.3  123.72   123.3 1078.43  121.65
Permanent Ineff=
       F       F
Bank Sta=1173.11,1357.51
XS Rating Curve= 0 ,0
Exp/Cntr=0.3,0.1

Type RM Length L Ch R = 1 ,71022.41,383.27,446.68,435.03
XS GIS Cut Line= 5
3020431.4537404513880278.39545283020407.9603491113880195.1498844
3020137.0999984413879235.40016343020050.65988261  13879088.70984
3019781.9786614513878993.3865398
#Sta/Elev= 30
       0   124.9    86.5  124.03  146.33  121.06  171.26  121.17  206.17  123.36
  325.83  124.47   445.5  121.14  475.42  122.47  545.23  122.99  615.03  121.53
  724.73  122.49  819.47  121.95  834.43  120.98  884.29  121.06  924.18  118.99
  993.99  120.57 1056.52  120.69 1104.47  119.35 1105.77  120.56 1130.79   113.8
 1142.19  112.51 1157.74   108.8 1164.97  102.23 1170.34  102.06 1176.09  103.46
  1180.8  109.34  1212.9   108.6 1251.99  119.29 1263.83   120.3 1539.09  122.13
#Mann= 4 ,-1 , 0
       0     .15       0 1056.52     .07       0 1105.77     .04       0
 1263.83     .07       0
#XS Ineff= 2 ,-1
       0   231.1  123.62   231.1 1003.96  120.65
Permanent Ineff=
       F       F
Bank Sta=1105.77,1263.83
XS Rating Curve= 0 ,0
Exp/Cntr=0.3,0.1

Type RM Length L Ch R = 1 ,70575.73,369.02,375.02,374.54
BEGIN DESCRIPTION:
Confluence with Dinner Creek (U120-00-00)
END DESCRIPTION:
XS GIS Cut Line= 4
3020535.70648469 13879988.9757563020543.0407876113879317.8639093
3020345.0077191113878555.06983123020161.5687815213877848.4895514
#Sta/Elev= 30
       0  124.71   74.57  123.78  109.37  120.71  164.06  123.02  223.72  123.27
  636.35  121.79   775.9  118.48   815.8  120.73  875.65  121.05  930.52  118.89
   940.5  117.49  965.44  109.55   980.4  107.28  999.65  100.67 1004.61  100.39
 1010.78   101.7 1025.29  109.07 1050.23  109.47 1095.12   121.8 1118.96  120.96
    1145  123.32 1219.82  122.59 1299.62  119.61 1344.51  122.07 1434.29  123.34
 1543.66  122.34 1583.38   119.5 1667.81  123.05 1772.09  124.18 2189.24  125.38
#Mann= 5 ,-1 , 0
       0     .15       0  875.65     .07       0  930.52     .04       0
 1095.12     .07       0 1118.96     .15       0
#XS Ineff= 3 ,-1
       0  183.95  123.13  183.95  860.69  121.04 1234.78 2189.24  121.51
Permanent Ineff=
       F       F       F
Bank Sta=930.52,1095.12
XS Rating Curve= 0 ,0
Exp/Cntr=0.3,0.1

Type RM Length L Ch R = 1 ,70200.7 ,722.22,740.28,736.14
XS GIS Cut Line= 5
3020809.7357922813879604.66484493020830.7101597813878962.0499884
3020786.3001436113878760.45984043020615.12364869 13878384.475028
3020372.0099616913877850.4816734
#Sta/Elev= 30
       0  123.59  164.48  122.05  214.32  122.95  259.18  121.47  398.73  121.03
  468.51  118.05  613.05  120.68  647.87  119.05  652.49  118.65  682.98  109.07
  689.31  108.32  693.97  102.54  696.21   101.4  702.24   99.54  709.11   98.99
  717.57   100.6  721.55  102.65  728.69  108.63  763.55  107.98  801.64  119.83
  810.06  121.31  838.69  120.52   953.9     120  973.81  118.95   998.7  119.19
 1028.56  121.94 1128.11  122.87 1605.58  123.62  1620.5  124.56 1849.23  125.58
#Mann= 5 ,-1 , 0
       0     .15       0  613.05     .07       0  647.87     .04       0
  810.06     .07       0  838.69     .15       0
#XS Ineff= 2 ,-1
       0  578.16  120.51  859.34 1949.23  120.94
Permanent Ineff=
       F       F
Bank Sta=647.87,810.06
XS Rating Curve= 0 ,0
Exp/Cntr=0.3,0.1

Type RM Length L Ch R = 1 ,69460.43,453.32,459.24,467.77
Node Name=Q
XS GIS Cut Line= 5
3021614.0980286913879727.00088633021594.0751028713879485.8255156
 3021538.109991713878811.71990843021459.39066094 13878226.128888
 3021410.214578213877860.3090816
#Sta/Elev= 30
       0  122.58  138.29  122.33  227.19  119.57  570.27  121.21  709.53  118.61
   754.3     121  830.11  120.73   848.8  119.76  868.69  118.12  898.54   108.6
   923.4  105.73  928.36  104.64  935.05  100.34  942.91   99.99  954.11  101.78
  958.15  104.46  963.12  105.91  978.01  107.29 1017.73  120.89 1032.63  121.89
 1051.48  121.47 1067.39  122.65 1112.07  122.61 1191.52  120.05 1345.44  122.31
 1489.43   120.6 1624.02  122.85  1753.7  121.53 1788.62  123.54  1878.4  124.37
#Mann= 5 ,-1 , 0
       0     .15       0  830.11     .07       0   848.8     .04       0
 1032.63     .07       0 1051.48     .15       0
#XS Ineff= 2 ,-1
       0  843.83  120.59 1017.73  1878.4  120.89
Permanent Ineff=
       F       F
Bank Sta=848.8,1032.63
XS Rating Curve= 0 ,0
Exp/Cntr=0.3,0.1

Type RM Length L Ch R = 1 ,69001.19,815.58,821.16,823.78
XS GIS Cut Line= 6
 3022073.473094213879742.28792923022045.6647508613879438.2898495
3021995.8498898613878893.7200725 3021994.300024213878794.4200743
3021992.4401197713878675.04006373021963.1242335313877882.8769498
#Sta/Elev= 30
       0  121.34  152.63  118.44   290.5  120.14  439.49  116.73  504.12  119.73
  568.75  120.25  648.29  119.98  712.91  117.35   767.6  120.65  807.37  120.81
  857.08     120  866.73  118.94  911.11  104.71  926.55   106.7  933.43  100.86
  942.11  100.61  953.42  101.29  959.38  105.74  972.27  105.07 1021.07  120.77
 1031.02  122.09  1069.3  122.19 1150.63  121.81 1195.53  119.67 1405.04   122.5
 1459.91  120.19 1644.35  122.18 1743.97  120.41 1773.86  122.23 1863.52  122.44
#Mann= 5 ,-1 , 0
       0     .15       0  807.37     .07       0  857.08     .04       0
 1031.02     .07       0  1069.3     .15       0
#XS Ineff= 2 ,-1
       0  842.17   120.1  1019.8 1863.52  120.35
Permanent Ineff=
       F       F
#Block Obstruct= 2 , 0
       0   29.54  121.36               0
Bank Sta=857.08,1031.02
XS Rating Curve= 0 ,0
Exp/Cntr=0.3,0.1

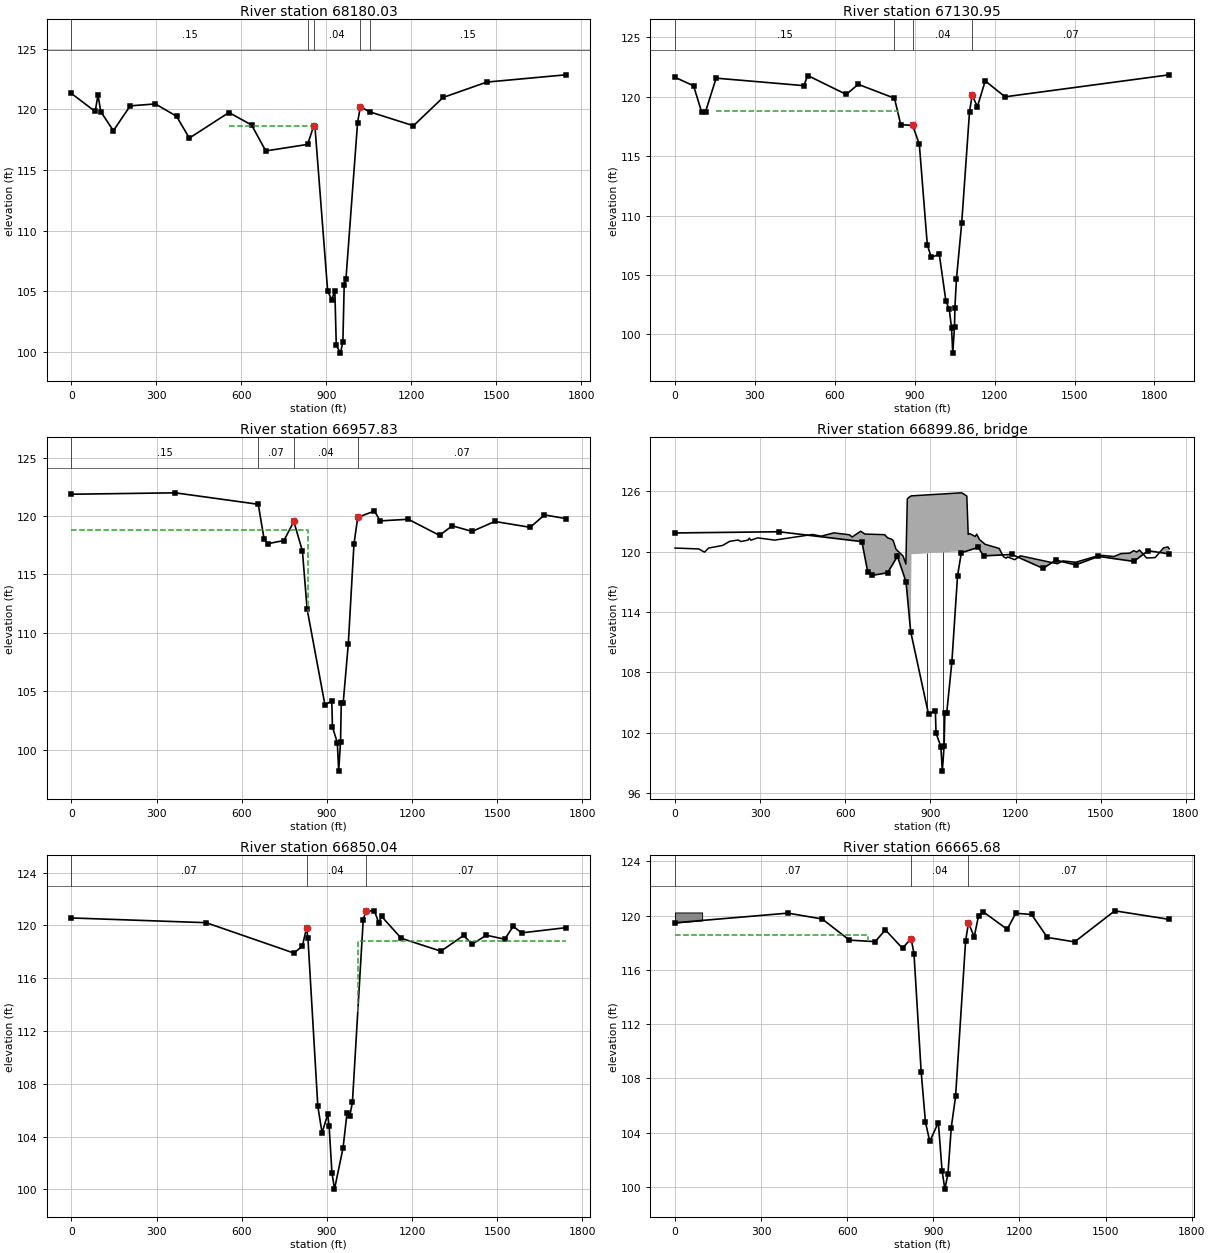
Type RM Length L Ch R = 1 ,68180.03,1050.76,1049.08,942.84
XS GIS Cut Line= 6
3022830.3708586113879767.4755429 3022822.081505113879446.2124058
 3022809.059877613878941.55002943022813.5300130213878820.8898376
3022819.3098571213878664.79008423022792.2072210313878023.3638736
#Sta/Elev= 30
       0  121.32   84.05  119.84   93.94   121.2  103.83  119.82  148.32  118.25
  207.65   120.3  296.65  120.46  371.35  119.44  416.34  117.64  556.29  119.75
  636.26  118.72  686.25  116.58  833.99  117.12  855.18  118.61  860.07  118.53
  904.82  105.02  919.22   104.3  930.13  105.06  935.22  100.55  949.92    99.9
  958.53  100.83  963.14  105.51  969.35  106.02  1010.4  118.91 1020.16  120.23
 1052.68  119.81 1207.66  118.66 1312.17  120.99 1466.45  122.26 1745.15  122.86
#Mann= 5 ,-1 , 0
       0     .15       0  833.99     .07       0  855.18     .04       0
 1020.16     .07       0 1052.68     .15       0
#XS Ineff= 3 ,-1
       0  207.65   120.3  207.65  556.29  119.75  556.29  850.35  118.64
Permanent Ineff=
       F       F       F
Bank Sta=855.18,1020.16
XS Rating Curve= 0 ,0
Exp/Cntr=0.3,0.1

Type RM Length L Ch R = 1 ,67130.95,87.58,173.11,202.41
XS GIS Cut Line= 5
3023813.2235516913879800.18282653023866.8700979513878924.4299849
3023779.9099700313878784.53984473023703.5098603713878670.4298367
 3023425.887712213878053.7457026
#Sta/Elev= 30
       0  121.63   69.79  120.92    99.7  118.74  114.66  118.73  154.54  121.56
  483.56  120.93  498.52  121.78  643.09  120.19  687.96  121.04   824.1  119.87
  847.48  117.65  892.37  117.58  917.33     116  947.27  107.54  962.25  106.47
   992.2  106.75 1017.15   102.8 1029.74  102.12 1038.28  100.54 1042.92   98.42
  1049.5  100.65 1050.86  102.21 1056.82  104.69 1076.44  109.36 1105.87  118.75
 1115.68  120.12 1135.29  119.16 1164.72  121.33 1239.11  119.99 1855.73  121.84
#Mann= 4 ,-1 , 0
       0     .15       0   824.1     .07       0  892.37     .04       0
 1115.68     .07       0
#XS Ineff= 2 ,-1
       0  154.54  121.56  154.54  837.54  118.77
Permanent Ineff=
       F       F
#Block Obstruct= 2 , 0
       0                 1840.81       0  122.25
Bank Sta=892.37,1115.68
XS Rating Curve= 0 ,0
Exp/Cntr=0.5,0.3

Type RM Length L Ch R = 1 ,66957.83,117.79,107.79,108.76
BEGIN DESCRIPTION:
Upstream Section - QUEENSTON BLVD
END DESCRIPTION:
Node Name=P
XS GIS Cut Line= 6
3023882.0114718713879647.20052093023921.3716293613878899.3699956
3023930.6491698613878700.71192843023937.6672004513878476.5017468
3023947.4394906213878357.06432173024029.95999487 13877915.145258
#Sta/Elev= 30
       0  121.86  366.02  121.98  658.45     121  679.14  117.99  694.08  117.64
  748.87   117.9  783.67  119.53  813.88  117.01  830.49  112.04   893.4  103.83
  917.48   104.2  919.68  101.96  936.87  100.62  941.76   98.18  948.25  100.69
   950.8     104  957.48  103.98  975.58  109.06  995.47  117.58 1008.86  119.89
 1067.87  120.42 1087.72  119.58 1187.05  119.72  1296.9  118.34 1341.86  119.16
 1411.79  118.68 1491.71  119.53 1616.58  119.03 1666.54  120.09 1741.46  119.78
#Mann= 4 ,-1 , 0
       0     .15       0  658.45     .07       0  783.67     .04       0
 1008.86     .07       0
#XS Ineff= 2 ,-1
       0  833.39  118.77 1008.85 1741.46  118.81
Permanent Ineff=
       F       F
#Block Obstruct= 2 , 0
       0                 1636.57       0  119.87
Bank Sta=783.67,1008.86
XS Rating Curve= 0 ,0
Exp/Cntr=0.5,0.3

Type RM Length L Ch R = 3 ,66899.86,,,
BEGIN DESCRIPTION:
QUEENSTON BLVD
END DESCRIPTION:
Node Name=QUEENSTON BLVD
Bridge Culvert--1,0,-1,-1, 0
Deck Dist Width WeirC Skew NumUp NumDn MinLoCord MaxHiCord MaxSubmerge Is_Ogee
9.5,90,2.6,0, 60, 60, , , 0.98, 0, 0,0,,
       0   84.09  103.87  118.71  168.17   192.9  222.58  232.47   257.2  262.15
   267.1  291.83  351.18   484.9  514.78  559.61  614.39  624.35  654.24  669.18
   738.9  748.87  763.78  768.75   778.7  803.56   813.5  818.47  828.42  833.39
 1008.85 1013.56 1028.18 1033.14  1038.1 1057.95 1062.91 1072.83 1092.68  1142.3
 1157.18 1167.11 1172.07 1197.03 1217.01 1346.85 1366.83 1411.79  1496.7 1546.65
 1571.63  1601.6 1616.58 1626.57 1636.56 1661.54 1691.51 1721.48 1736.47 1741.46
  120.36  120.27  119.95  120.36  120.62  121.03  121.16  121.01  121.15  121.34
  121.14  121.37  121.15  121.71  121.54  121.87  121.68  121.46  122.03  121.75
  121.69  121.38  121.23  121.11  120.24  119.57  118.77  125.25  125.49  125.55
  125.85   125.8  125.53  121.71   121.8  121.51  121.74   121.2  120.73  120.32
   119.5  119.35  119.48   119.2  119.59   118.8  119.08  118.95  119.65  119.52
  119.81  119.85   120.1  119.96  120.16  119.37  119.41  120.38  120.47  120.29
       0       0       0       0       0       0       0       0       0       0
       0       0       0       0       0       0       0       0       0       0
       0       0       0       0       0       0       0       0       0  119.74
  120.04       0       0       0       0       0       0       0       0       0
       0       0       0       0       0       0       0       0       0       0
       0       0       0       0       0       0       0       0       0       0
       0   84.09  103.87  118.71  168.17   192.9  222.58  232.47   257.2  262.15
   267.1  291.83  351.18   484.9  514.78  559.61  614.39  624.35  654.24  669.18
   738.9  748.87  763.78  768.75   778.7  803.56   813.5  818.47  828.42  833.39
 1008.85 1013.56 1028.18 1033.14  1038.1 1057.95 1062.91 1072.83 1092.68  1142.3
 1157.18 1167.11 1172.07 1197.03 1217.01 1346.85 1366.83 1411.79  1496.7 1546.65
 1571.63  1601.6 1616.58 1626.57 1636.56 1661.54 1691.51 1721.48 1736.47 1741.46
  120.36  120.27  119.95  120.36  120.62  121.03  121.16  121.01  121.15  121.34
  121.14  121.37  121.15  121.71  121.54  121.87  121.68  121.46  122.03  121.75
  121.69  121.38  121.23  121.11  120.24  119.57  118.77  125.25  125.49  125.55
  125.85   125.8  125.53  121.71   121.8  121.51  121.74   121.2  120.73  120.32
   119.5  119.35  119.48   119.2  119.59   118.8  119.08  118.95  119.65  119.52
  119.81  119.85   120.1  119.96  120.16  119.37  119.41  120.38  120.47  120.29
       0       0       0       0       0       0       0       0       0       0
       0       0       0       0       0       0       0       0       0       0
       0       0       0       0       0       0       0       0       0  119.64
  119.94       0       0       0       0       0       0       0       0       0
       0       0       0       0       0       0       0       0       0       0
       0       0       0       0       0       0       0       0       0       0
Pier Skew, UpSta & Num, DnSta & Num=  ,888.56, 2 ,888.56, 2 , 0 , 0 , 0 ,,
     1.4     1.4
      95     121
     1.4     1.4
      95     121
Pier Skew, UpSta & Num, DnSta & Num=  ,944.46, 2 ,944.46, 2 , 0 , 0 , 0 ,,
     1.4     1.4
      95     121
     1.4     1.4
      95     121
Abutment Skew #Up #Dn= , 2 , 2
  830.66  900.96
  119.74  103.49
  830.66  900.96
  119.64  103.39
Abutment Skew #Up #Dn= , 2 , 2
  965.16 1011.15
  103.97  120.04
  965.16 1011.15
  103.87  119.94
BR Coef=-1 , 1 , 1 ,0.9, 0 ,,,0.8,-1,1.2,0,
WSPro=,,,, 1 ,,,, 0 ,,,, 0 ,,,,-1 ,-1 ,-1 , 0 , 0 , 0 , 0 , 0
BC Design=,, 0 ,, 0 ,,,,,,
BC Use User HTab Curves=0
BC User HTab FreeFlow(D)= 0

Type RM Length L Ch R = 1 ,66850.04,184,184.36,178.27
BEGIN DESCRIPTION:
Downstream Section - QUEENSTON BLVD
END DESCRIPTION:
XS GIS Cut Line= 6
 3023987.973202213879648.85701373024027.3333596913878901.0264883
3024036.6109001913878702.36842113024043.6289307813878478.1582396
3024053.4012209513878358.7208144 3024135.921725213877916.8017508
#Sta/Elev= 30
       0  120.57  474.94  120.21  783.67  117.91   813.5  118.42  828.42   119.8
  833.39  119.03  868.19   106.3  883.11  104.28  902.99  105.67  907.97   104.8
  917.91  101.27  926.94  100.01  957.14  103.14  971.25   105.8  980.65  105.56
  990.05  106.58 1028.18  120.44  1038.1  121.11 1067.87   121.1 1082.76   120.2
 1092.68  120.69 1162.14  119.03 1301.89  118.05 1381.82  119.24 1411.79  118.58
 1461.74  119.26 1526.67  118.96 1556.64  119.93 1586.61  119.44 1741.46  119.83
#Mann= 3 ,-1 , 0
       0     .07       0  828.42     .04       0  1038.1     .07       0
#XS Ineff= 2 ,-1
       0  833.39  118.77 1008.85 1741.46  118.81
Permanent Ineff=
       F       F
#Block Obstruct= 2 , 0
       0                 1556.64       0  119.93
Bank Sta=828.42,1038.1
XS Rating Curve= 0 ,0
Exp/Cntr=0.5,0.3

Type RM Length L Ch R = 1 ,66665.68,564.89,547.93,507.48
XS GIS Cut Line= 4
3024215.1617241913879650.96790193024215.1617241913879168.0958361
3024215.16172419 13878548.5376923024207.87269677 13877928.979876
#Sta/Elev= 30
       0  119.47  393.27  120.18  512.85  119.75  607.78  118.19  697.72  118.08
  732.69  118.95  792.65  117.59  822.63  118.31  832.62   117.2  857.61   108.5
  872.59  104.78  887.58  103.36  917.56  104.75  930.44  101.21  940.15   99.84
  950.96  100.96  962.53  104.38  977.52  106.67  1012.5  118.13 1022.49  119.46
 1042.47  118.43 1057.46  119.98 1072.45   120.3  1157.4  118.99 1187.38  120.17
 1242.34  120.08  1297.3  118.39 1392.24  118.06 1532.15  120.35 1722.03  119.72
#Mann= 3 ,-1 , 0
       0     .07       0  822.63     .04       0 1022.49     .07       0
#XS Ineff= 2 ,-1
       0  672.74  118.59 1277.32 1722.03  118.95
Permanent Ineff=
       F       F
#Block Obstruct= 2 , 0
       0   94.58  120.23               0
Bank Sta=822.63,1022.49
XS Rating Curve= 0 ,0
Exp/Cntr=0.3,0.1