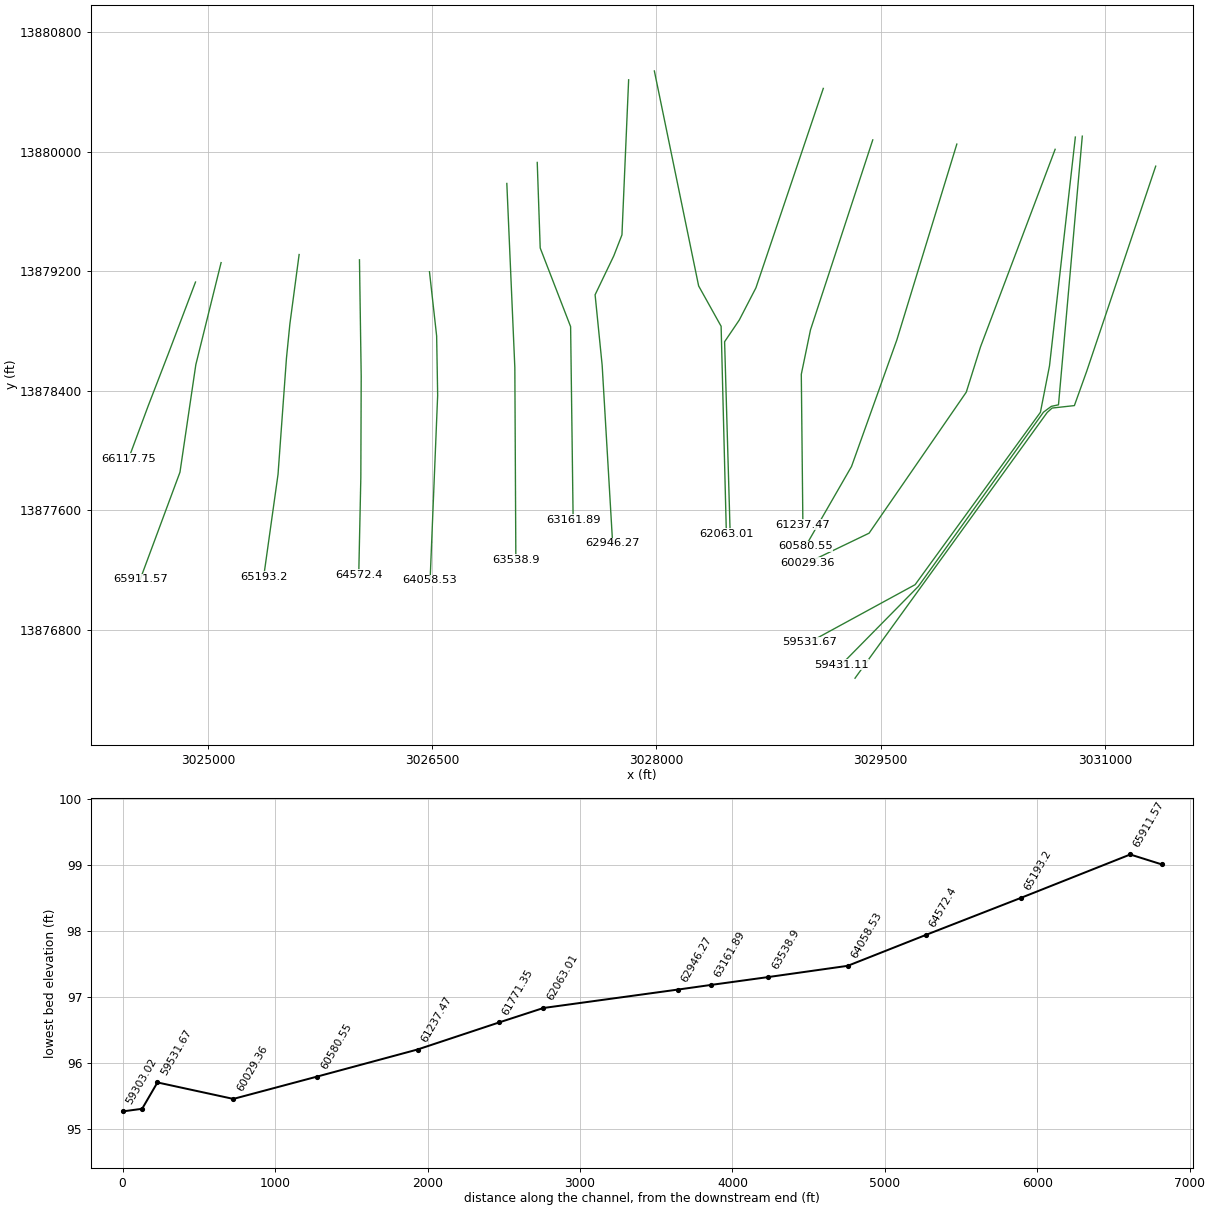
HEC-RAS study U100-00-00.prj: U100-00-00

--- U100-00-00.g01 (geometry) --- (continued)

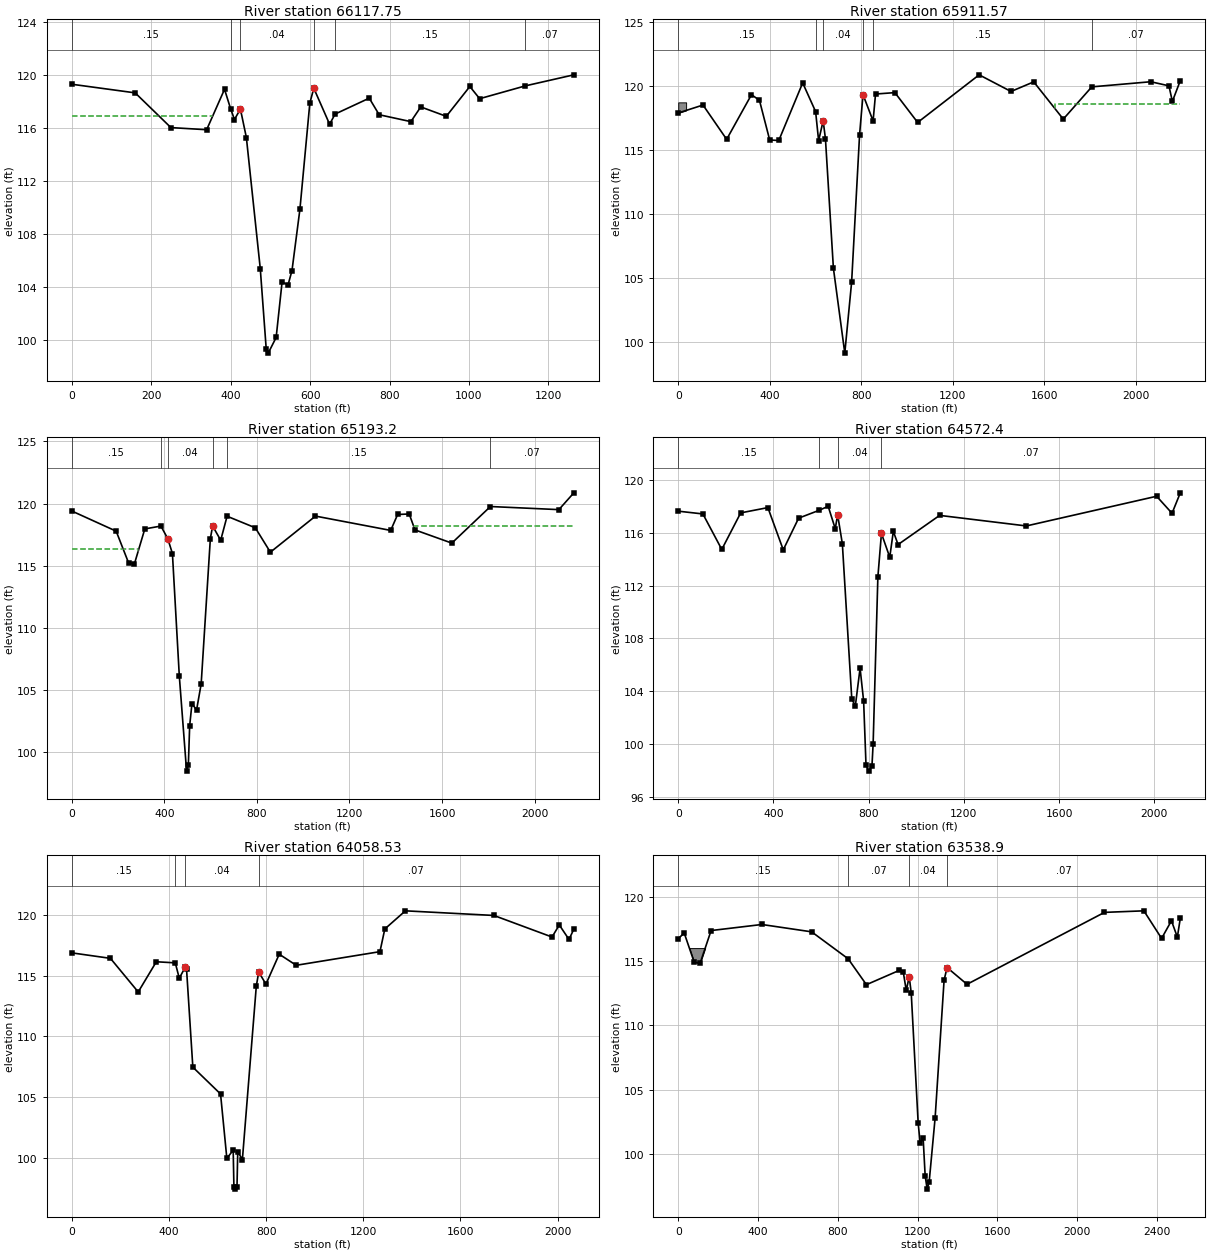
Type RM Length L Ch R = 1 ,66117.75,192.48,206.18,221.1
Node Name=O
XS GIS Cut Line= 5
3024916.7370926913879128.22813373024869.0199965213879002.3300915
3024737.89985195 13878656.3799963024601.4001249413878302.7301128
3024468.8564267813877946.1068103
#Sta/Elev= 30
       0  119.29  159.64  118.64  249.63  116.02  339.62  115.86  384.61  118.91
  399.83  117.45  409.61  116.63  424.61  117.42  439.61  115.27   474.6  105.39
   489.6   99.32   494.6   99.01  514.58  100.19  529.54  104.38   544.5  104.15
  554.48  105.24  574.43  109.86  599.37  117.86  609.35  118.99  649.25  116.27
  662.93  117.04  749.01  118.24  773.95  116.99  853.75  116.47  878.69  117.58
  942.97  116.87 1002.26  119.12 1026.97   118.2 1142.38  119.17 1264.14     120
#Mann= 6 ,-1 , 0
       0     .15       0  399.83     .07       0  424.61     .04       0
  609.35     .07       0  662.93     .15       0 1142.38     .07       0
#XS Ineff= 1 ,-1
       0  354.62   116.9
Permanent Ineff=
       F
Bank Sta=424.61,609.35
XS Rating Curve= 0 ,0
Exp/Cntr=0.3,0.1

Type RM Length L Ch R = 1 ,65911.57,683.48,718.37,692
XS GIS Cut Line= 5
3025087.9562384513879258.05333343025016.9426009513878971.2950486
3024918.86996244 13878575.2699223024812.8527860313877856.0905861
3024546.5485286113877138.7652491
#Sta/Elev= 30
       0  117.92  108.32  118.54  211.72  115.86   320.3  119.35  355.13  118.91
   399.9  115.81  439.71  115.77  544.19  120.27  600.71  118.03  613.85  115.76
  633.75   117.3   643.7  115.91  678.53  105.79   728.3   99.16  758.18   104.7
  793.03  116.23  807.97  119.35  852.11   117.3  862.74   119.4  947.39  119.51
 1046.97  117.18 1315.84   120.9  1455.2   119.6 1554.57  120.35 1683.76  117.44
 1808.41  119.96 2066.34  120.36 2145.83  120.04 2160.74  118.82 2195.52  120.45
#Mann= 6 ,-1 , 0
       0     .15       0  600.71     .07       0  633.75     .04       0
  807.97     .07       0  852.11     .15       0 1808.41     .07       0
#XS Ineff= 2 ,-1
       0  474.54  116.89 1648.98 2195.52  118.65
Permanent Ineff=
       F       F
#Block Obstruct= 2 , 0
       0   34.47  118.75               0
Bank Sta=633.75,807.97
XS Rating Curve= 0 ,0
Exp/Cntr=0.3,0.1

Type RM Length L Ch R = 1 ,65193.2 ,580.49,620.8,606.15
XS GIS Cut Line= 6
3025609.9699581913879312.22940613025578.18918186 13879073.339792
3025548.0301214513878846.64011423025525.2998519413878619.3698994
3025468.8554110213877841.51285943025372.9579650313877156.8383757
#Sta/Elev= 30
       0   119.4  191.81  117.78  245.97  115.21  270.82  115.16  315.57  117.96
  385.17  118.19     415  117.17  434.89  115.98  464.72  106.12  496.08    98.5
  503.71   98.98  509.41  102.15  519.34  103.93  539.21  103.41  559.07   105.5
  598.79  117.19  608.72  118.19  643.48  117.05  671.08  118.98  793.08  118.05
  858.08  116.09 1053.05  118.99 1378.01  117.84    1408  119.12    1458  119.16
 1482.97  117.88 1642.13  116.82 1808.87  119.76 2104.69  119.51 2169.35  120.86
#Mann= 6 ,-1 , 0
       0     .15       0  385.17     .07       0     415     .04       0
  608.72     .07       0  671.08     .15       0 1808.87     .07       0
#XS Ineff= 2 ,-1
       0  285.74  116.33 1477.99 2169.35  118.17
Permanent Ineff=
       F       F
Bank Sta=415,608.72
XS Rating Curve= 0 ,0
Exp/Cntr=0.3,0.1

Type RM Length L Ch R = 1 ,64572.4 ,535.53,513.87,510.91
Node Name=N
XS GIS Cut Line= 5
3026013.6850300313879276.8187158 3026015.524265213879153.5177813
3026025.29983619  13878498.159843026022.8132926113877819.6461052
3026008.8077431913877168.0617784
#Sta/Elev= 30
       0  117.64  103.58  117.43   182.9  114.74  262.35  117.51  376.55  117.91
   441.1  114.71  505.65  117.11  592.54  117.71  629.78  118.01  659.58  116.31
  669.51  117.37  689.37  115.17  729.09  103.39  743.99  102.89  763.85  105.74
  778.75  103.25  788.72   98.41  799.56   97.94  813.67    98.3  818.66     100
  838.61  112.66  853.58  115.95  888.51  114.15  903.47  116.11  923.43  115.11
 1098.05  117.32 1462.24  116.52  2009.5  118.77 2074.17  117.48    2109  119.03
#Mann= 4 ,-1 , 0
       0     .15       0  592.54     .07       0  669.51     .04       0
  853.58     .07       0
#XS Ineff= 1 ,-1
       0  470.89  115.29
Permanent Ineff=
       F
Bank Sta=669.51,853.58
XS Rating Curve= 0 ,0
Exp/Cntr=0.3,0.1

Type RM Length L Ch R = 1 ,64058.53,540.56,519.63,518.22
Node Name=M
XS GIS Cut Line= 5
3026482.0151301213879197.25128963026529.9799291913878767.3000498
 3026536.820138613878370.93995013026518.4596110313877921.6908486
3026486.2746360313877134.1786441
#Sta/Elev= 30
       0  116.86  159.12  116.41  273.49  113.65  348.08  116.13  426.12  116.04
  442.53  114.78  467.31  115.69   472.5  115.52  498.38  107.48  612.45  105.28
  638.41   99.99   664.5  100.67  667.46   97.68  672.77   97.47  680.17   97.68
  683.24  100.54   702.4    99.9  759.66  114.13  769.57  115.29  799.31  114.29
  854.02  116.75  923.96  115.84 1268.67  116.96 1288.64  118.82 1373.44  120.31
  1737.6  119.93 1977.04  118.16 2006.97  119.15 2046.88  117.96 2066.83  118.81
#Mann= 4 ,-1 , 0
       0     .15       0  426.12     .07       0  467.31     .04       0
  769.57     .07       0
#XS Ineff= 1 ,-1
       0  318.25  115.13
Permanent Ineff=
       F
Bank Sta=467.31,769.57
XS Rating Curve= 0 ,0
Exp/Cntr=0.3,0.1

Type RM Length L Ch R = 1 ,63538.9 ,379,377.01,377.92
XS GIS Cut Line= 4
 3026999.528202713879787.65365213027053.1301296113878555.8001447
3027057.83943778 13877666.5788263027059.9316251913877271.5563221
#Sta/Elev= 30
       0  116.73   29.95  117.17   79.87  114.91  109.82  114.83  164.74  117.36
  419.33  117.83  668.93  117.26  851.79  115.17  943.48  113.16 1108.22  114.27
 1128.19  114.15 1143.16  112.72 1158.14  113.77 1168.12  112.53 1203.07   102.4
 1213.05  100.87 1228.03  101.23 1238.02   98.33 1247.97    97.3    1258   97.84
 1287.97  102.83 1332.93  113.51 1347.92  114.49 1447.84  113.19 2137.07  118.77
 2334.59  118.89 2423.47  116.75 2472.85  118.12 2502.47  116.85 2517.29  118.32
#Mann= 4 ,-1 , 0
       0     .15       0  851.79     .07       0 1158.14     .04       0
 1347.92     .07       0
#Block Obstruct= 2 , 0
       0  164.74     116               0
Bank Sta=1158.14,1347.92
XS Rating Curve= 0 ,0
Exp/Cntr=0.3,0.1

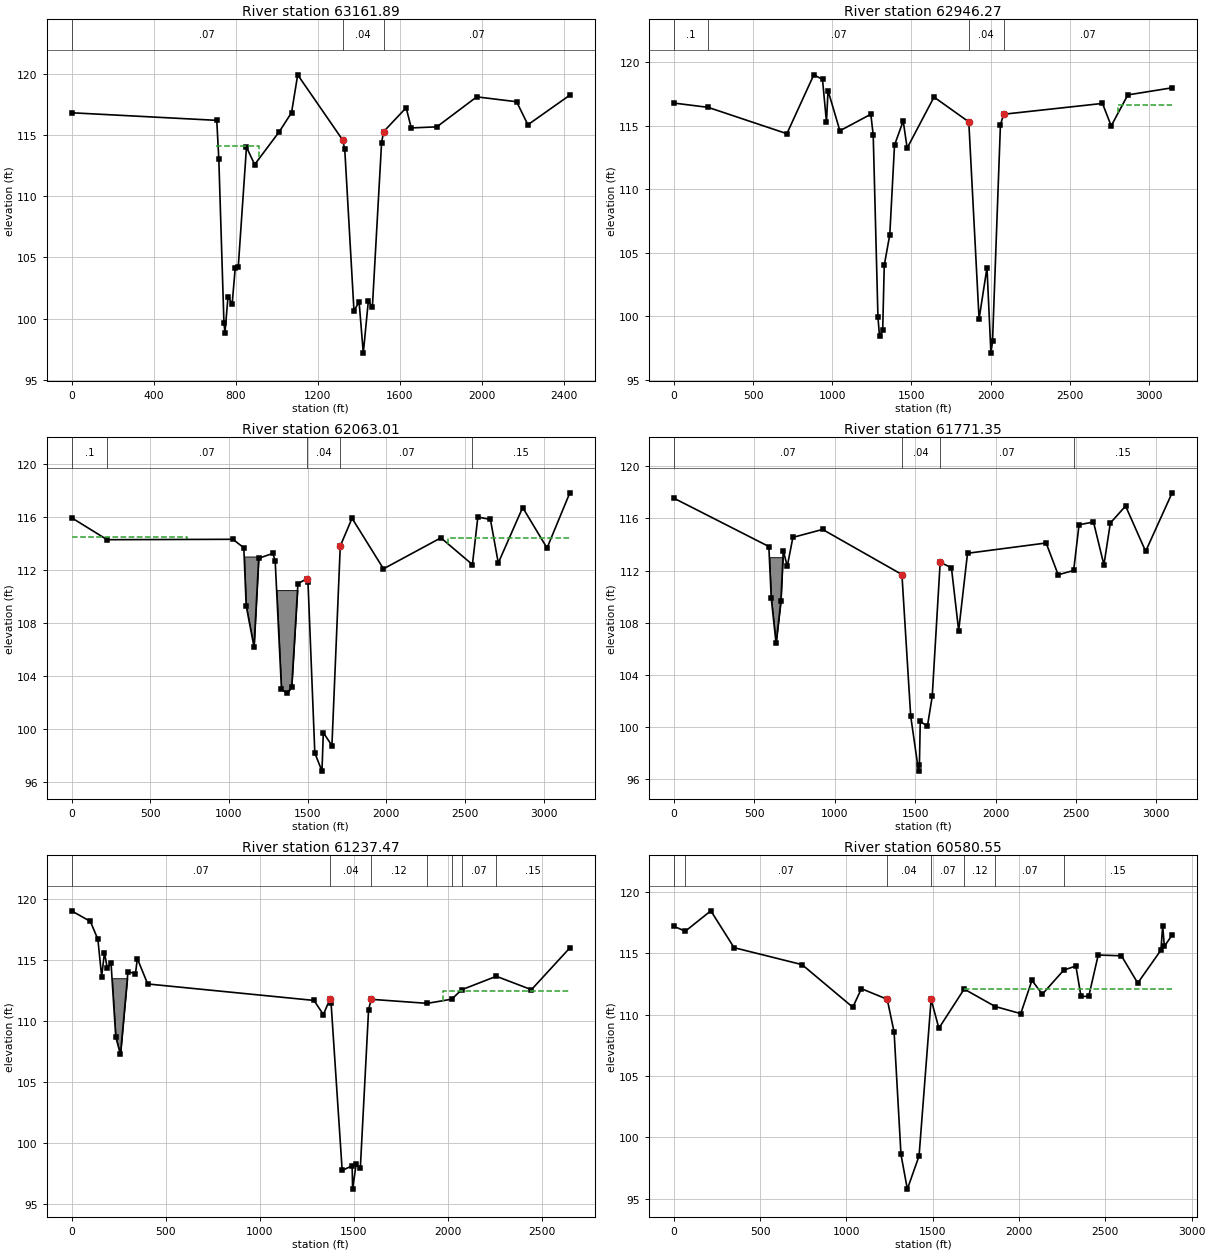
Type RM Length L Ch R = 1 ,63161.89,201.27,215.62,212.55
Node Name=L
XS GIS Cut Line= 5
3027202.9835044413879928.37843633027210.9067169413879700.1866354
 3027222.856496213879356.03345233027426.2642258613878829.9239403
3027443.1890607813877538.8481103
#Sta/Elev= 30
       0  116.82  707.47   116.2  717.45  113.02  742.41   99.65   747.4   98.86
  762.38   101.8  782.34  101.18  797.32  104.12  812.29  104.25  852.23  114.01
  892.16  112.59 1011.96  115.27 1071.86  116.83 1101.81  119.92 1321.21  114.59
 1331.18  113.82 1376.05  100.64 1400.97  101.37 1421.51   97.18 1445.84  101.41
 1465.78  100.96 1510.65  114.39 1520.62  115.28  1630.3  117.23 1655.22  115.58
 1779.86  115.67 1974.28  118.12 2168.71  117.72 2223.55  115.84 2427.95  118.26
#Mann= 3 ,-1 , 0
       0     .07       0 1321.21     .04       0 1520.62     .07       0
#XS Ineff= 1 ,-1
  702.47  912.13  114.07
Permanent Ineff=
       T
Bank Sta=1321.21,1520.62
XS Rating Curve= 0 ,0
Exp/Cntr=0.3,0.1

Type RM Length L Ch R = 1 ,62946.27,809.47,883.26,888.34
Node Name=K
XS GIS Cut Line= 6
 3027814.463252613880481.25856413027769.73991686 13879443.779996
3027715.2200127813879303.56997463027590.1021527813879043.0494983
3027637.3300766913878571.37983793027707.4300021113877379.6200823
#Sta/Elev= 30
       0  116.78  216.93  116.44  713.66  114.37  883.55     119  938.51  118.64
  963.49  115.29  973.49  117.76 1048.15   114.6 1243.69   115.9 1258.64  114.26
 1288.54   99.95  1298.5   98.42 1318.43   98.92  1328.4  104.02 1363.28  106.43
 1393.18  113.47 1447.99  115.37  1472.9  113.24 1642.55  117.25  1862.1   115.3
 1926.97   99.79 1976.89  103.83 2001.76   97.11 2011.86   98.03 2061.81  115.06
 2081.79   115.9 2706.17  116.75 2761.11  114.98 2866.01  117.42 3145.73  117.98
#Mann= 4 ,-1 , 0
       0      .1       0  216.93     .07       0  1862.1     .04       0
 2081.79     .07       0
#XS Ineff= 2 ,-1
 1258.64 1393.18  113.47 2806.07 3145.73  116.64
Permanent Ineff=
       T       F
Bank Sta=1862.1,2081.79
XS Rating Curve= 0 ,0
Exp/Cntr=0.3,0.1

Type RM Length L Ch R = 1 ,62063.01,376.66,291.66,178.64
XS GIS Cut Line= 5
 3027986.516386213880540.36868213028015.3299768613880400.5100379
3028282.8199274413879102.13993133028433.1598498713878832.2198674
3028468.3677846913877443.4486949
#Sta/Elev= 30
       0  115.97   225.9  114.31 1024.89  114.34 1094.66   113.7 1109.61  109.32
 1159.45  106.21 1189.35  112.91 1279.06  113.27 1294.01   112.7 1333.88  103.01
 1368.76  102.72 1398.66  103.16 1438.53     111 1493.35  111.34 1502.46  111.12
  1545.9    98.2 1591.35   96.83 1599.86   99.74 1654.54   98.76 1707.63  113.83
  1782.4  115.93 1982.28  112.11 2347.08  114.45 2547.44  112.43 2581.95  116.02
  2661.9  115.84 2711.87  112.55 2866.79  116.74  3021.7  113.68 3166.62  117.85
#Mann= 5 ,-1 , 0
       0      .1       0   225.9     .07       0 1493.35     .04       0
 1707.63     .07       0 2547.44     .15       0
#XS Ineff= 2 ,-1
       0  735.84  114.52 2392.05 3166.62  114.46
Permanent Ineff=
       F       F
#Block Obstruct= 2 ,-1
 1094.36  1204.3  113.04 1298.99 1438.53   110.5
Bank Sta=1493.35,1707.63
XS Rating Curve= 0 ,0
Exp/Cntr=0.3,0.1

Type RM Length L Ch R = 1 ,61771.35,482.51,533.88,531.47
XS GIS Cut Line= 6
 3029116.770031213880423.6723932 3029037.831212713880190.0130836
 3028666.046523213879089.5303764 3028554.5113132 13878873.895309
 3028456.503635213878728.97204243028493.33492637 13877457.319402
#Sta/Elev= 30
       0  117.56  590.62  113.85  605.58  109.88  635.49  106.43   665.4  109.64
  680.36  113.53  705.29  112.33  740.18  114.55  924.64  115.16 1418.13   111.7
 1472.63  100.84 1521.58   96.61 1526.87   97.09 1532.08  100.42 1576.67  100.06
  1606.4  102.34 1655.99  112.64 1725.97  112.22 1770.96  107.39 1825.94  113.33
 2314.87  114.12  2389.7  111.68 2485.94  112.01 2519.42  115.52 2609.22  115.73
 2674.08  112.44 2713.99  115.65 2808.78  116.96 2933.51  113.48 3098.14  117.97
#Mann= 4 ,-1 , 0
       0     .07       0 1418.13     .04       0 1655.99     .07       0
 2485.94     .15       0
#XS Ineff= 2 ,-1
       0  924.64  115.16 2314.87 3098.14  114.12
Permanent Ineff=
       F       F
#Block Obstruct= 1 ,-1
  590.62  680.36  113.03
Bank Sta=1418.13,1655.99
XS Rating Curve= 0 ,0
Exp/Cntr=0.3,0.1

Type RM Length L Ch R = 1 ,61237.47,624.28,656.92,600.63
XS GIS Cut Line= 4
3029447.7454191113880079.36041783029031.0999269513878808.2999678
3028969.60004994 13878511.0298933028980.2532438613877505.3307889
#Sta/Elev= 30
       0  119.03   99.82  118.16  139.75  116.69  159.71  113.64  174.69   115.6
  189.66  114.33  209.62  114.73  234.58   108.7  259.54  107.25  299.46  114.03
  339.39  113.88  349.37  115.11  404.28  113.03 1287.69  111.68  1337.6  110.52
 1372.44  111.79 1378.36   111.5 1437.47   97.73 1490.39   98.12 1492.94    96.2
 1511.52   98.23 1533.99   97.93 1577.73   110.9  1591.4  111.77 1889.33  111.44
 2019.39  111.78  2071.6  112.55 2256.34  113.66 2442.79  112.56 2646.93  115.99
#Mann= 7 ,-1 , 0
       0     .07       0 1372.44     .04       0  1591.4     .12       0
 1889.33     .07       0 2019.39     .15       0  2071.6     .07       0
 2256.34     .15       0
#XS Ineff= 2 ,-1
       0  349.37  115.11 1974.76 2646.93  112.49
Permanent Ineff=
       F       F
#Block Obstruct= 1 ,-1
  209.62   299.4   113.5
Bank Sta=1372.44,1591.4
XS Rating Curve= 0 ,0
Exp/Cntr=0.3,0.1

Type RM Length L Ch R = 1 ,60580.55,550.11,551.19,554.75
XS GIS Cut Line= 4
3030010.1301211113880051.18002793029608.6099267813878740.5799589
3029305.7122386113877894.55277953028997.6144296113877359.4974192
#Sta/Elev= 30
       0  117.19   66.39  116.79  214.33  118.45  348.91  115.45  742.68  114.07
 1036.77   110.6 1086.61  112.11 1236.15  111.25 1276.02  108.58  1315.9   98.61
 1352.76   95.79 1420.65   98.49 1490.54  111.24 1535.48  108.89 1681.93  112.08
 1861.68  110.66 2009.75  110.08 2074.65  112.79 2134.55  111.66 2258.85  113.62
  2329.1  113.96 2358.97  111.48 2403.79  111.49 2458.56  114.85    2593  114.79
  2687.6  112.57 2822.04  115.25    2832  117.23 2841.96  115.55 2886.77  116.49
#Mann= 7 ,-1 , 0
       0     .12       0   66.39     .07       0 1236.15     .04       0
 1490.54     .07       0 1681.93     .12       0 1861.68     .07       0
 2258.85     .15       0
#XS Ineff= 1 ,-1
 1681.93 2886.77  112.11
Permanent Ineff=
       F
Bank Sta=1236.15,1490.54
XS Rating Curve= 0 ,0
Exp/Cntr=0.3,0.1

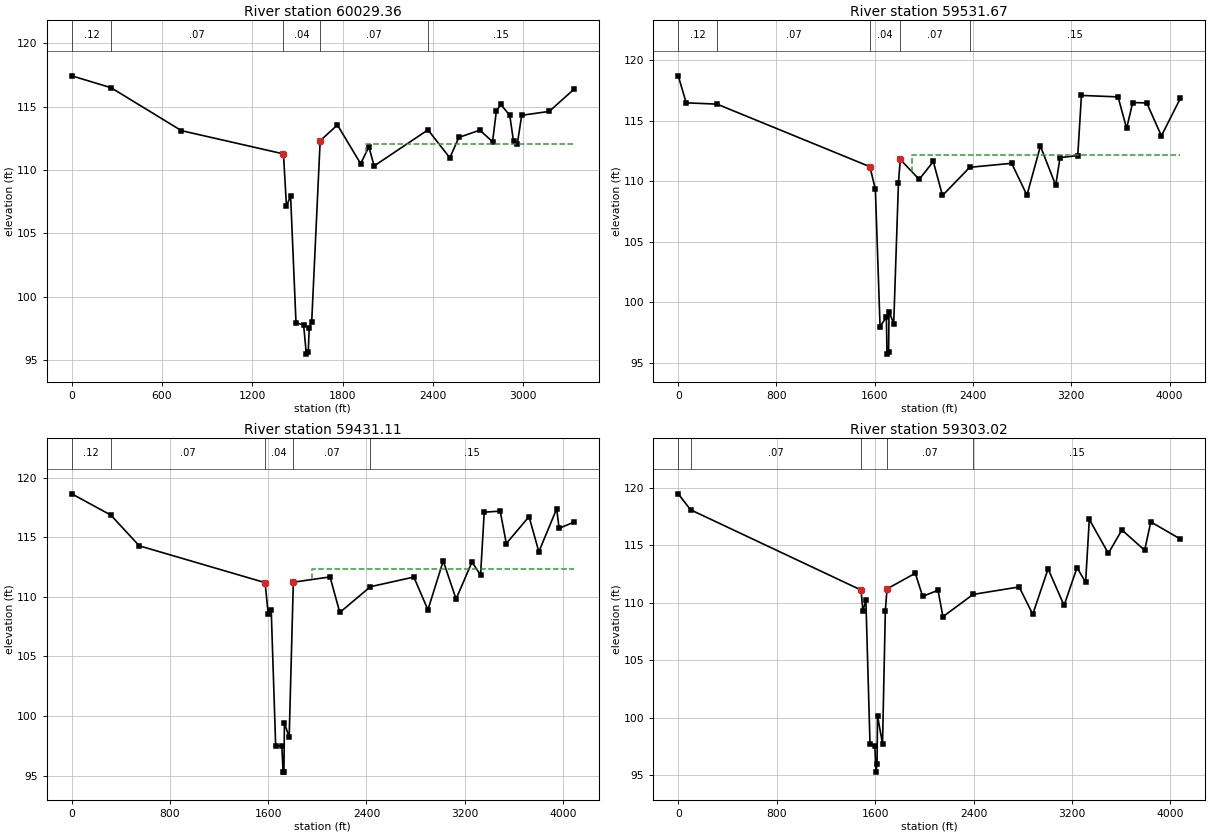
Type RM Length L Ch R = 1 ,60029.36,485.91,497.69,507.81
XS GIS Cut Line= 5
3030667.8207348613880016.25293243030168.9099872713878695.5400227
3030073.2399030313878391.43990913029422.9616760313877448.0392369
3029008.0310754513877248.3864209
#Sta/Elev= 30
       0  117.44  261.31   116.5  728.35  113.11 1406.82  111.27 1426.75  107.17
 1454.48  107.93 1490.27   97.93 1540.95   97.76 1558.82   95.45 1571.83   95.61
 1578.17   97.55 1594.61      98  1650.9  112.31 1765.47  113.56 1919.91   110.5
 1974.71  111.83 2009.58  110.32 2367.51  113.17 2512.73  110.96 2572.52  112.57
    2712  113.15 2796.69  112.23  2821.6  114.64 2851.49  115.18 2911.06  114.31
 2935.82  112.27 2960.57  112.02 2990.28  114.32 3173.48  114.63 3336.87  116.37
#Mann= 5 ,-1 , 0
       0     .12       0  261.31     .07       0 1406.82     .04       0
  1650.9     .07       0 2367.51     .15       0
#XS Ineff= 1 ,-1
 1954.78 3336.87  112.05
Permanent Ineff=
       F
Bank Sta=1406.82,1650.9
XS Rating Curve= 0 ,0
Exp/Cntr=0.3,0.1

Type RM Length L Ch R = 1 ,59531.67,90.71,100.56,109.04
XS GIS Cut Line= 5
3030803.0425772813880098.32429063030630.0875426113878567.3535993
3030569.2333336213878256.67541483029731.0827789513877103.6869072
3029024.1583397813876718.5078875
#Sta/Elev= 30
       0   118.7   64.82  116.47  316.11  116.36 1560.49  111.19 1605.01  109.32
 1643.13   97.98  1694.8   98.76 1699.51    95.7 1712.47   95.85 1716.32   99.22
 1754.34   98.22 1792.98  109.87 1807.82  111.79 1961.96  110.14 2076.59  111.62
 2151.35  108.81 2373.32  111.14 2714.55  111.47 2839.15  108.84  2948.8  112.89
  3073.4  109.65 3108.29  111.94 3252.83  112.11 3282.73  117.08  3580.9  116.96
 3650.47  114.36 3700.16  116.49 3814.46  116.46 3933.73  113.74 4087.78  116.83
#Mann= 5 ,-1 , 0
       0     .12       0  316.11     .07       0 1560.49     .04       0
 1807.82     .07       0 2373.32     .15       0
#XS Ineff= 1 ,-1
 1907.13 4087.78  112.15
Permanent Ineff=
       F
Bank Sta=1560.49,1807.82
XS Rating Curve= 0 ,0
Exp/Cntr=0.3,0.1

Type RM Length L Ch R = 1 ,59431.11,152,128.09,109.1
Node Name=J
XS GIS Cut Line= 6
3030849.4840854413880104.1963261 3030690.219640213878306.8820073
 3030641.883122713878296.45650333030589.7556022713878257.5976571
 3029752.501043213877091.92971283029236.8321270213876568.3343033
#Sta/Elev= 30
       0  118.64  317.74  116.86   549.8  114.28 1574.44  111.19 1599.43  108.58
 1624.42  108.87 1660.46   97.53 1710.68   97.49 1721.32    95.3 1727.68    95.3
  1731.9   99.41 1770.57   98.23 1804.36  111.23 2103.21  111.67 2182.94  108.69
 2431.95  110.85 2785.92  111.66 2900.53  108.91 3025.12  113.01 3129.77  109.82
 3259.33  112.92  3329.1  111.82 3359.02   117.1    3489  117.19 3538.99  114.47
 3723.96  116.73 3803.95  113.78 3948.93  117.38 3968.92  115.75  4088.9  116.26
#Mann= 5 ,-1 , 0
       0     .12       0  317.74     .07       0 1574.44     .04       0
 1804.36     .07       0 2431.95     .15       0
#XS Ineff= 1 ,-1
 1958.69  4088.9  112.37
Permanent Ineff=
       F
Bank Sta=1574.44,1804.36
XS Rating Curve= 0 ,0
Exp/Cntr=0.3,0.1

Type RM Length L Ch R = 1 ,59303.02,227.93,132.65,34.23
XS GIS Cut Line= 6
3031340.5903866913879903.48314483030879.37739836 13878532.655834
3030796.5383251913878301.61955073030647.4073898613878285.1714209
3030614.5108021113878255.56452473029328.9457879413876477.9253634
#Sta/Elev= 30
       0  119.47  100.47  118.08  1485.6   111.1 1500.33  109.29 1524.92  110.23
 1558.39   97.71 1597.07   97.57 1606.98   95.26  1615.5   96.01 1619.52  100.16
 1660.18   97.72  1683.1  109.31 1696.56   111.2 1926.23  112.56  1986.2  110.55
 2111.13  111.08 2151.11  108.78 2396.12  110.72 2770.77  111.37 2880.72  108.99
 3005.65  112.94 3135.58  109.76 3240.52  113.05 3310.48  111.78 3340.47  117.24
 3495.39  114.29 3605.33  116.33 3790.23  114.56  3840.2  117.03 4080.07  115.54
#Mann= 5 ,-1 , 0
       0      .1       0  100.47     .07       0  1485.6     .04       0
 1696.56     .07       0 2396.12     .15       0
#XS Ineff= 1 ,-1
 1926.23 4080.07  112.56
Permanent Ineff=
       F
Bank Sta=1485.6,1696.56
XS Rating Curve= 0 ,0
Exp/Cntr=0.5,0.3