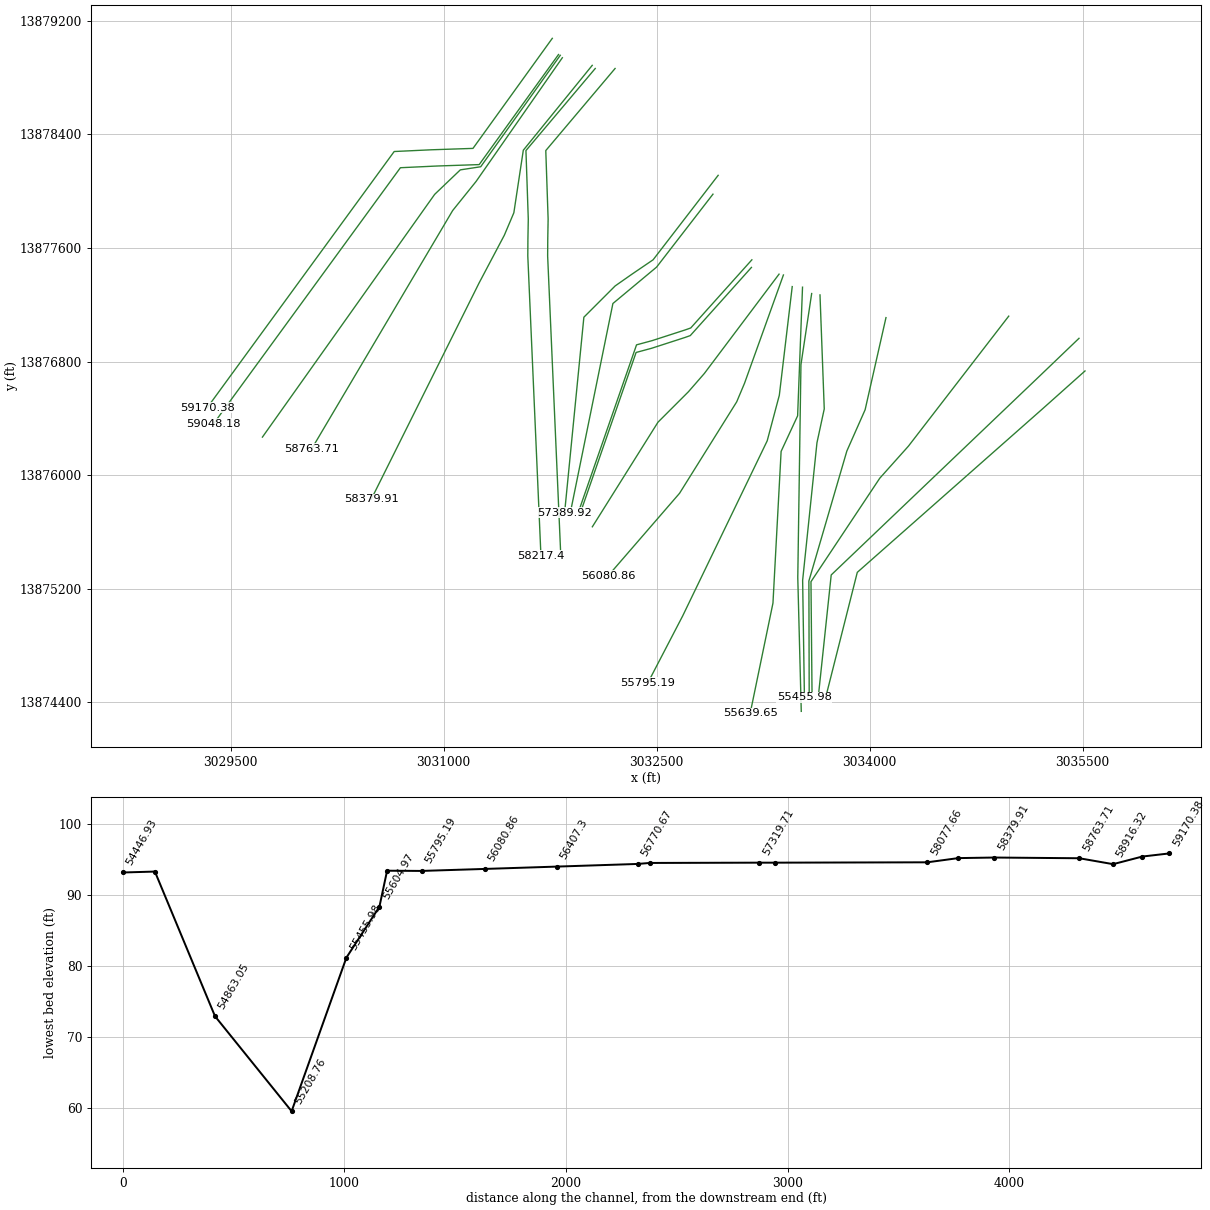
HEC-RAS study U100-00-00.prj: U100-00-00

--- U100-00-00.g01 (geometry) --- (continued)

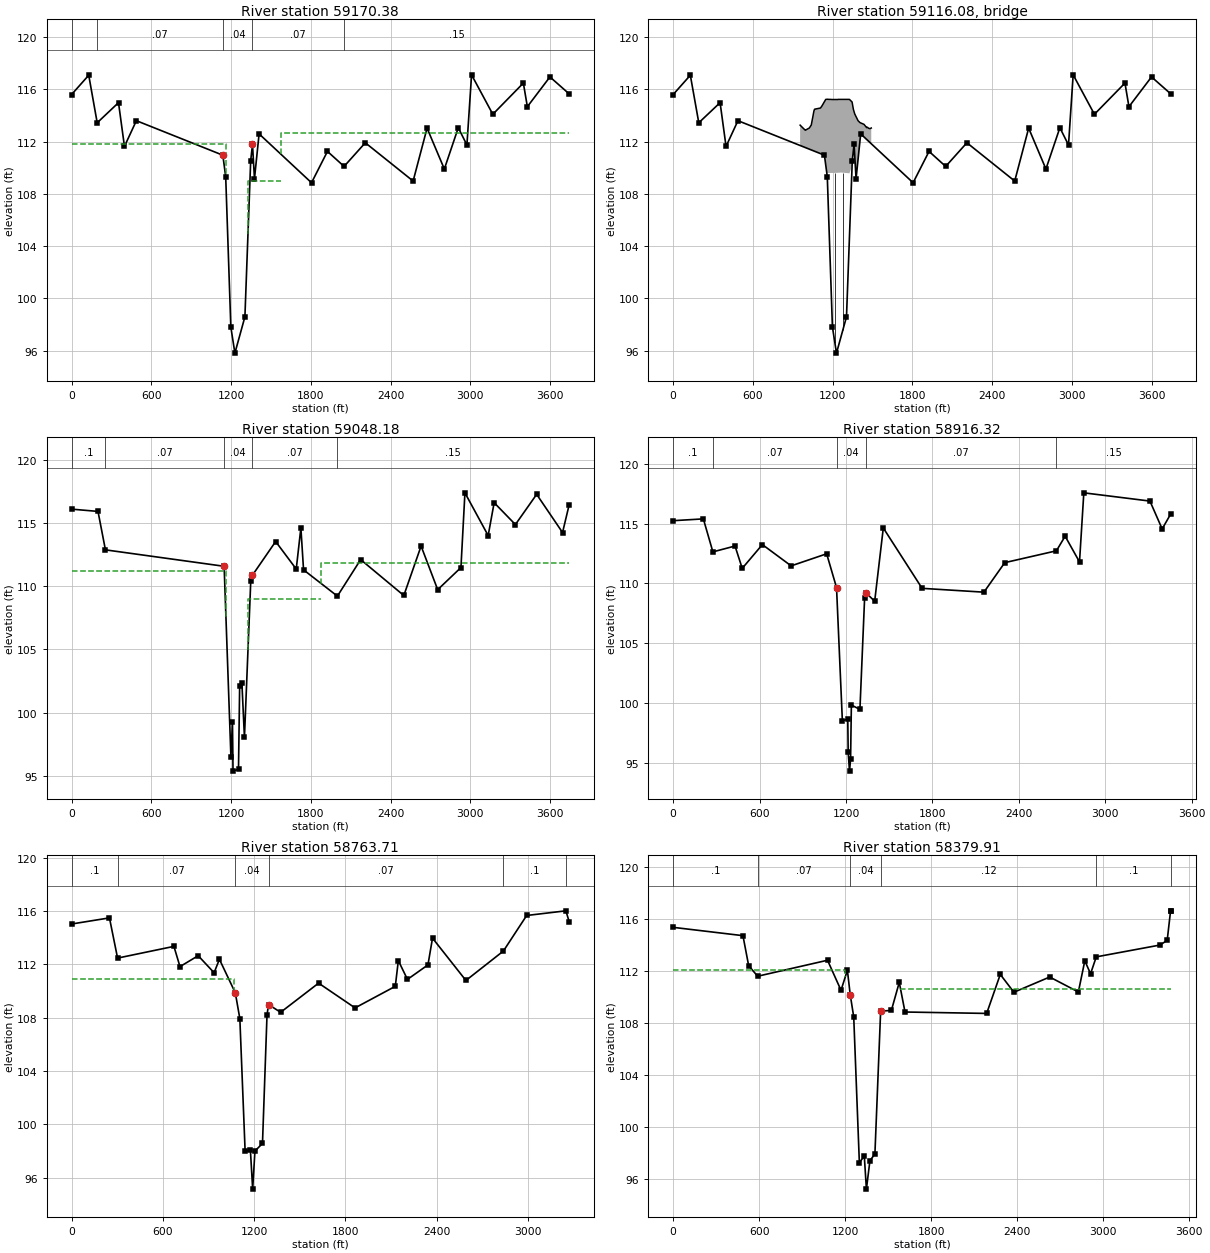
Type RM Length L Ch R = 1 ,59170.38,131.3,122.19,129.03
BEGIN DESCRIPTION:
Upstream Section - WEST LITTLE YORK RD
END DESCRIPTION:
XS GIS Cut Line= 5
3031764.9343542813879076.56353883031206.4111931213878301.6070835
3030915.1292953613878291.83380913030651.6275257813878279.5720226
3029335.0753688713876475.5726779
#Sta/Elev= 30
       0   115.6  129.36  117.08  192.97  113.44  353.24  114.98  398.02  111.63
  487.58   113.6 1138.02  110.96 1159.67  109.32 1198.32   97.81 1228.83   95.81
 1304.18   98.59 1347.65  110.53 1361.17  111.79  1376.1  109.16 1410.94  112.59
 1805.26  108.85 1925.17  111.25 2050.27   110.1 2209.95  111.91 2569.68  108.98
  2674.6  113.03  2804.5   109.9 2909.42  113.06 2974.37  111.74 3009.35  117.11
 3169.23  114.09 3399.05  116.48 3429.03  114.67  3598.9  116.95 3743.79  115.65
#Mann= 5 ,-1 , 0
       0      .1       0  192.97     .07       0 1138.02     .04       0
 1361.17     .07       0 2050.27     .15       0
#XS Ineff= 3 ,-1
       0 1158.24   111.8 1327.34 1575.44  109.01 1575.44 3743.79  112.64
Permanent Ineff=
       F       F       F
Bank Sta=1138.02,1361.17
XS Rating Curve= 0 ,0
Exp/Cntr=0.5,0.3

Type RM Length L Ch R = 3 ,59116.08,,,
BEGIN DESCRIPTION:
WEST LITTLE YORK RD
U00_400
END DESCRIPTION:
Node Name=WEST LITTLE YORK
Bridge Culvert--1,0,-1,-1, 0
Deck Dist Width WeirC Skew NumUp NumDn MinLoCord MaxHiCord MaxSubmerge Is_Ogee
9,104,2.6,0, 58, 58, , , 0.98, 0, 0,0,,
  955.25  965.13  975.01  984.89  989.83  994.77 1004.65 1024.41 1039.23 1044.17
 1049.11 1054.05 1058.99 1063.93 1068.87 1073.81 1083.69 1088.63 1098.51 1108.38
 1118.26 1128.14 1133.08 1142.96  1147.9 1157.78 1162.72  1172.6 1182.48  1197.3
 1202.24 1207.18 1212.12    1222 1236.82 1241.76 1251.68 1261.63 1266.61 1276.56
 1291.49 1296.47  1311.4 1326.33 1346.24  1356.2 1366.15  1376.1 1381.08 1391.04
 1405.97 1410.94 1435.83 1455.74 1460.72 1470.67 1480.62 1490.58
  113.26  113.16  113.06  112.96  112.91  112.87  112.93  113.04  113.27  113.54
   113.8  114.07  114.34  114.48  114.49   114.5  114.52  114.53  114.55  114.57
  114.71  114.88  114.97  115.14  115.23  115.24  115.24  115.23  115.23  115.22
  115.22  115.22  115.22  115.22  115.22  115.23  115.23  115.23  115.23  115.23
  115.23  115.23  115.23  115.23  115.03  114.46  114.12  113.91  113.81   113.6
  113.45  113.43  113.32  113.07   113.1  113.02  112.99  113.04
       0       0       0       0       0       0       0       0       0       0
       0       0       0       0       0       0       0       0       0       0
       0       0  109.98  109.73  109.61   109.6   109.6   109.6   109.6   109.6
   109.6   109.6   109.6  109.61  109.61  109.62  109.62  109.63  109.63  109.62
  109.61   109.6  109.59  109.57       0       0       0       0       0       0
       0       0       0       0       0       0       0       0
  955.25  965.13  975.01  984.89  989.83  994.77 1004.65 1024.41 1039.23 1044.17
 1049.11 1054.05 1058.99 1063.93 1068.87 1073.81 1083.69 1088.63 1098.51 1108.38
 1118.26 1128.14 1133.08 1142.96  1147.9 1157.78 1162.72  1172.6 1182.48  1197.3
 1202.24 1207.18 1212.12    1222 1236.82 1241.76 1251.68 1261.63 1266.61 1276.56
 1291.49 1296.47  1311.4 1326.33 1346.24  1356.2 1366.15  1376.1 1381.08 1391.04
 1405.97 1410.94 1435.83 1455.74 1460.72 1470.67 1480.62 1490.58
  113.11  113.07  113.13  113.36  113.31  113.26  113.16  112.96   112.9  112.92
  112.94  112.96  112.99  113.01  113.03  113.06  113.11   113.3  113.69  114.07
  114.46  114.66  114.72  116.48  116.48  116.47  116.46  116.45  116.44  116.42
  116.42  116.41  116.41  116.39  116.38  116.37  116.36  116.35  116.34  116.33
  116.31  116.31  116.29  116.27  116.25  116.23  116.22  114.55  114.53  114.48
   114.4  114.37  113.29  112.84  112.91  113.03  113.16  113.04
       0       0       0       0       0       0       0       0       0       0
       0       0       0       0       0       0       0       0       0       0
       0       0       0       0       0  109.61  109.61  109.61  109.61  109.61
  109.61  109.61  109.61  109.61  109.61  109.61   109.6   109.6   109.6   109.6
  109.59  109.59  109.59  109.58       0       0       0       0       0       0
       0       0       0       0       0       0       0       0
Pier Skew, UpSta & Num, DnSta & Num=  ,1217.57, 2 ,1226.67, 2 , 0 , 0 , 0 ,,
    1.35    1.35
      95     111
    1.35    1.35
      95     111
Pier Skew, UpSta & Num, DnSta & Num=  ,1277.77, 2 ,1286.67, 2 , 0 , 0 , 0 ,,
    1.35    1.35
      95     111
    1.35    1.35
      95     111
BR Coef=-1 , 1 , 1 ,1.25, 0 ,,,0.8,0,2,0,
WSPro=,,,, 1 ,,,, 0 ,,,, 0 ,,,,-1 ,-1 ,-1 , 0 , 0 , 0 , 0 , 0
BC Design=,, 0 ,, 0 ,,,,,,
BC Use User HTab Curves=0
BC User HTab FreeFlow(D)= 0

Type RM Length L Ch R = 1 ,59048.18,72.71,131.87,212.3
BEGIN DESCRIPTION:
Downstream Section - WEST LITTLE YORK RD
END DESCRIPTION:
XS GIS Cut Line= 5
3031808.6691749413878962.46731043031250.14601378 13878187.510855
3030958.8641160313878177.73758063030695.3623464413878165.4757941
3029378.8101895313876361.4764494
#Sta/Elev= 30
       0  116.09  199.01  115.91  254.81  112.87  1147.9  111.57  1198.9   96.51
 1210.56   99.28 1214.78   95.37 1255.99   95.52 1264.65  102.08 1281.47  102.35
 1300.72   98.03 1348.16  110.39 1361.17  110.87 1535.47  113.53 1690.35  111.35
 1725.32  114.61 1745.31  111.29 1999.84  109.21 2174.98   112.1 2499.73  109.26
 2629.64  113.17 2754.54  109.72 2929.41  111.47 2959.38  117.38 3134.25     114
 3179.22   116.6  3339.1  114.87 3498.97  117.26 3693.83  114.24 3743.79  116.45
#Mann= 5 ,-1 , 0
       0      .1       0  254.81     .07       0  1147.9     .04       0
 1361.17     .07       0 1999.84     .15       0
#XS Ineff= 3 ,-1
       0 1161.39  111.16  1327.2 1880.21  109.01 1880.21 3743.79  111.84
Permanent Ineff=
       F       F       F
Bank Sta=1147.9,1361.17
XS Rating Curve= 0 ,0
Exp/Cntr=0.5,0.3

Type RM Length L Ch R = 1 ,58916.32,141.96,152.6,166.28
XS GIS Cut Line= 5
3031821.0566173613878957.04310863031260.8172522813878172.3333919
 3031117.212880713878150.32949893030936.5495281113877977.7727574
3029723.7583185313876268.5727638
#Sta/Elev= 30
       0  115.25  209.82   115.4  275.88  112.64  429.63  113.13  479.59  111.26
  619.47  113.25   819.3  111.47 1065.87  112.48 1134.44  109.65  1174.9   98.51
 1212.46   98.65 1215.27   95.88 1224.47    94.3    1232   95.31 1237.42   99.83
 1296.83   99.46 1329.31  108.77  1339.3  109.21 1399.21  108.51 1459.09  114.64
 1728.54  109.59 2157.67  109.27 2302.38  111.74 2660.96  112.73 2721.52  113.95
 2821.32   111.8 2851.26  117.58 3310.32  116.89 3395.15  114.56 3455.03  115.82
#Mann= 5 ,-1 , 0
       0      .1       0  275.88     .07       0 1134.44     .04       0
  1339.3     .07       0 2660.96     .15       0
#XS Ineff= 2 ,-1
       0 1065.87  112.48 1459.09 3455.03  110.87
Permanent Ineff=
       F       F
Bank Sta=1134.44,1339.3
XS Rating Curve= 0 ,0
Exp/Cntr=0.3,0.1

Type RM Length L Ch R = 1 ,58763.71,357.36,383.8,402.98
XS GIS Cut Line= 4
3031835.7432677713878940.03198783031228.2434985313878068.8112893
3031063.4180407813877863.9567121 3030071.807163113876187.7409044
#Sta/Elev= 30
       0  115.04  249.32   115.5  302.66  112.48  673.17  113.36  713.06  111.84
  832.74  112.66  937.45  111.38  972.36  112.39    1077  109.87 1106.76  107.93
 1141.49   97.96 1176.21   98.05  1191.1   95.13 1205.98   97.99 1255.59   98.56
 1285.36   108.2 1295.28  108.99 1374.98  108.41 1624.67   110.6 1864.37  108.74
 2129.04  110.36 2149.01  112.29 2208.93  110.88 2343.76  111.97 2373.73  113.98
 2593.45   110.8 2839.86  113.01 2992.94  115.68 3250.76  116.03 3272.59  115.21
#Mann= 6 ,-1 , 0
       0      .1       0  302.66     .07       0    1077     .04       0
 1295.28     .07       0 2839.86      .1       0 3250.76     .07       0
#XS Ineff= 2 ,-1
       0 1067.05  110.91 1624.67 3272.59   110.6
Permanent Ineff=
       F       F
Bank Sta=1077,1295.28
XS Rating Curve= 0 ,0
Exp/Cntr=0.3,0.1

Type RM Length L Ch R = 1 ,58379.91,127.06,162.51,201.62
XS GIS Cut Line= 6
3032046.2100384413878886.37002163031560.7700644413878288.6586186
3031494.2800399413877848.37012913031427.1400823613877690.1001044
3031249.6801354413877354.35996233030489.4362491113875829.6192454
#Sta/Elev= 30
       0  115.36  486.84  114.72  526.59  112.42  589.22   111.6 1076.75  112.83
 1170.76  110.52 1215.29  112.06 1234.93  110.19 1259.49  108.47 1298.79   97.26
 1333.17   97.78 1347.91   95.23 1372.47   97.42 1407.19   97.93 1447.17  108.92
 1522.12  108.97 1577.08  111.13 1617.06  108.85 2186.65  108.74 2281.58  111.74
 2376.51  110.37 2626.33  111.54 2826.19  110.39 2871.16  112.79 2911.13  111.79
 2951.06  113.09 3395.78     114 3445.74  114.36 3469.06  116.61 3470.72  116.63
#Mann= 6 ,-1 , 0
       0      .1       0  589.22     .07       0 1234.93     .04       0
 1447.17     .12       0 2951.06      .1       0 3469.06     .15       0
#XS Ineff= 2 ,-1
       0 1200.44  112.09 1587.08 3470.72  110.59
Permanent Ineff=
       F       F
Bank Sta=1234.93,1447.17
XS Rating Curve= 0 ,0
Exp/Cntr=0.5,0.3

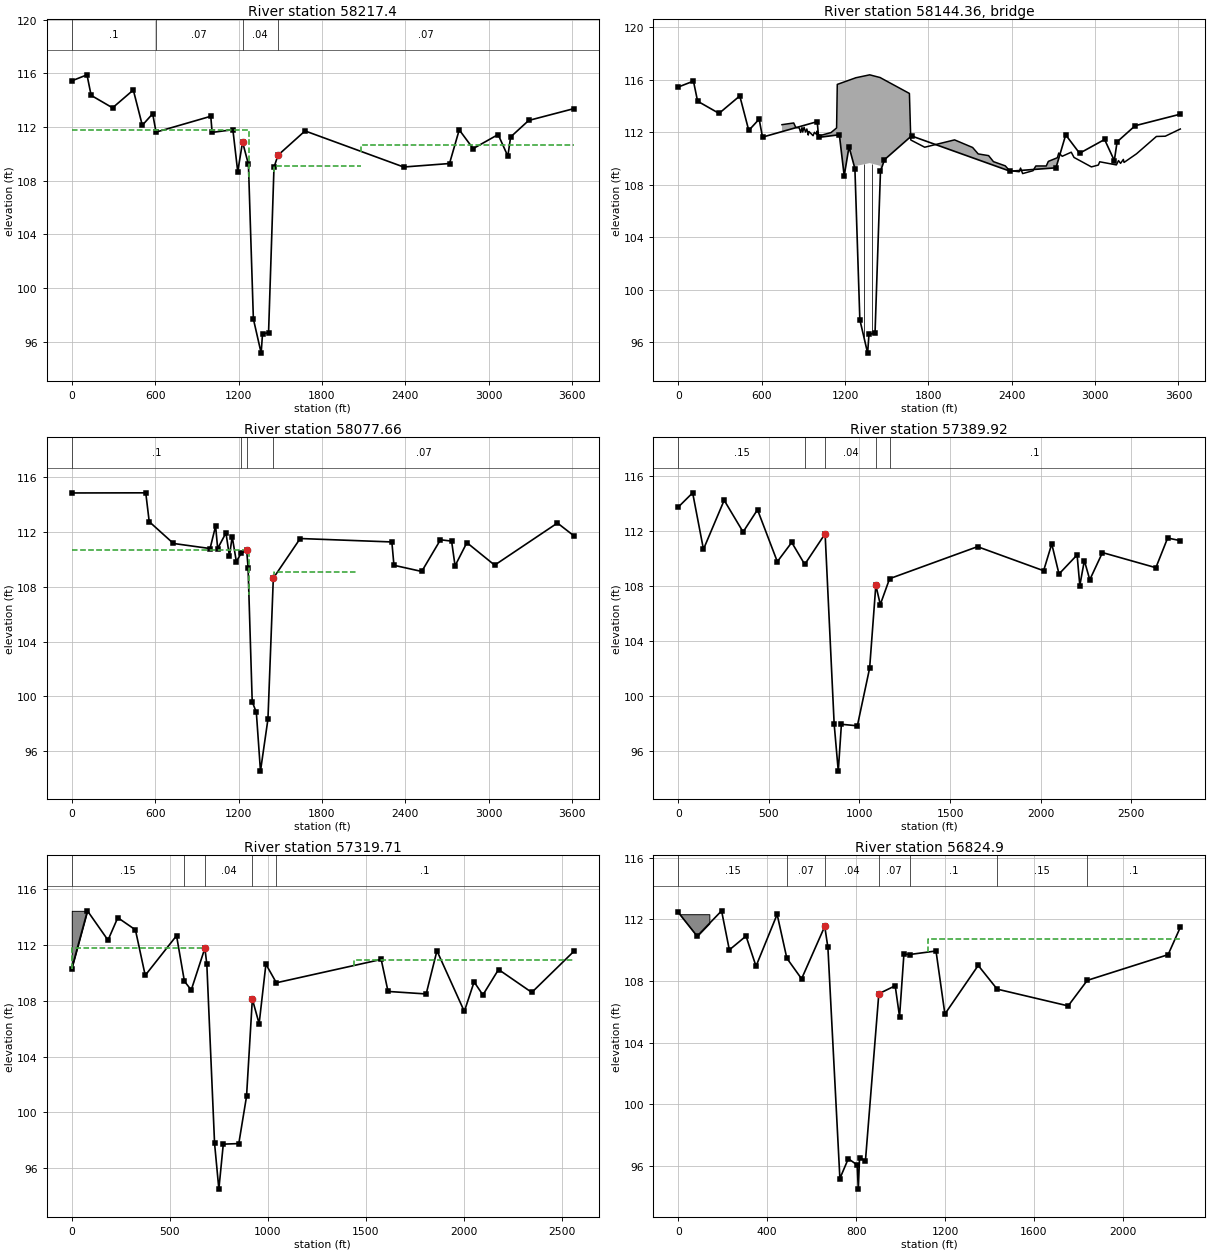
Type RM Length L Ch R = 1 ,58217.4 ,140.15,139.75,139.77
BEGIN DESCRIPTION:
Upstream Section - SH 6
END DESCRIPTION:
Node Name=I
XS GIS Cut Line= 6
3032067.3162954513878864.21127333031579.3763264413878286.1963532
 3031595.863498213877803.75013963031593.2693432713877660.0486553
3031592.44683836 13877544.0711973031685.0985559413875431.5278499
#Sta/Elev= 30
       0  115.44  109.48  115.89  139.34  114.36  293.61  113.43  442.91  114.76
   507.6  112.13  582.25  112.99  606.56  111.62 1000.28   112.8 1010.23   111.6
 1159.53   111.8 1194.37  108.67 1229.21  110.88 1271.45  109.22 1307.03    97.7
 1363.07   95.15  1372.7   96.58 1416.33   96.68 1455.37     109 1484.37   109.9
 1678.82  111.71 2388.65  109.02 2718.57  109.28 2788.55  111.79 2888.52  110.39
 3068.48  111.44 3138.46  109.83 3158.46  111.26 3288.42  112.49 3613.42  113.37
#Mann= 4 ,-1 , 0
       0      .1       0  606.56     .07       0 1229.21     .04       0
 1484.37     .07       0
#XS Ineff= 3 ,-1
       0 1274.97  111.75 1454.26 2083.73  109.07 2083.73 3613.42  110.68
Permanent Ineff=
       F       F       F
Bank Sta=1229.21,1484.37
XS Rating Curve= 0 ,0
Exp/Cntr=0.5,0.3

Type RM Length L Ch R = 3 ,58144.36,,,
BEGIN DESCRIPTION:
SH 6
END DESCRIPTION:
Node Name=SH 6
Bridge Culvert--1,0,-1,-1, 0
Deck Dist Width WeirC Skew NumUp NumDn MinLoCord MaxHiCord MaxSubmerge Is_Ogee
22,104,2.6,0, 60, 60, , , 0.98, 0, 0,0,,
  746.48  831.08  846.01  870.89  880.84   890.8  895.77  905.73  915.68  925.63
  935.59  940.56  970.42  980.38  995.31 1000.28 1005.26 1025.16 1099.81 1139.63
  1144.6 1273.85 1274.97 1377.93 1454.26  1460.2 1663.83 1673.82  1773.8 1988.75
 2118.72 2158.71 2233.69 2268.68 2353.66 2383.65 2453.63 2463.63 2478.63 2553.61
  2573.6 2648.58 2663.58 2728.56 2738.56 2763.56 2828.54 2848.53  2973.5 3023.49
 3033.49 3153.46 3168.45 3183.45 3203.44 3208.44 3298.42 3441.29 3505.22 3613.42
  112.57   112.7  112.36  112.32  111.98  112.35  112.01  112.37  112.01  112.24
  111.78  112.05  111.73  111.99  111.83  112.09  111.82  111.75  111.97  112.32
  115.64  116.13  116.14  116.37  116.16  116.12  114.95   111.4  110.85  111.41
  110.83  110.34  110.21  109.75  109.43  109.07  108.98  109.26  108.84  109.06
  109.42  109.42  109.77  110.05  110.41  110.16  110.47  110.07  109.35  109.49
  109.74   109.5  109.83  109.62  109.92  109.69  110.35  111.67  111.69  112.24
       0       0       0       0       0       0       0       0       0       0
       0       0       0       0       0       0       0       0       0       0
       0       0  109.41  109.64  109.43       0       0       0       0       0
       0       0       0       0       0       0       0       0       0       0
       0       0       0       0       0       0       0       0       0       0
       0       0       0       0       0       0       0       0       0       0
  746.48  831.08  846.01  870.89  880.84   890.8  895.77  905.73  915.68  925.63
  935.59  940.56  970.42  980.38  995.31 1000.28 1005.26 1025.16 1099.81 1139.63
  1144.6 1273.85 1274.97 1377.93 1454.26  1460.2 1663.83 1673.82  1773.8 1988.75
 2118.72 2158.71 2233.69 2268.68 2353.66 2383.65 2453.63 2463.63 2478.63 2553.61
  2573.6 2648.58 2663.58 2728.56 2738.56 2763.56 2828.54 2848.53  2973.5 3023.49
 3033.49 3153.46 3168.45 3183.45 3203.44 3208.44 3298.42 3441.29 3505.22 3613.42
  112.57   112.7  112.36  112.32  111.98  112.35  112.01  112.37  112.01  112.24
  111.78  112.05  111.73  111.99  111.83  112.09  111.82  111.75  111.97  112.32
  115.64  116.13  116.14  116.37  116.16  116.12  114.95   111.4  110.85  111.41
  110.83  110.34  110.21  109.75  109.43  109.07  108.98  109.26  108.84  109.06
  109.42  109.42  109.77  110.05  110.41  110.16  110.47  110.07  109.35  109.49
  109.74   109.5  109.83  109.62  109.92  109.69  110.35  111.67  111.69  112.24
       0       0       0       0       0       0       0       0       0       0
       0       0       0       0       0       0       0       0       0       0
       0       0  109.31  109.54  109.33       0       0       0       0       0
       0       0       0       0       0       0       0       0       0       0
       0       0       0       0       0       0       0       0       0       0
       0       0       0       0       0       0       0       0       0       0
Pier Skew, UpSta & Num, DnSta & Num=  ,1335.27, 2 ,1335.27, 2 , 0 , 0 , 0 ,,
     1.4     1.4
      95   110.5
     1.4     1.4
      95   110.5
Pier Skew, UpSta & Num, DnSta & Num=  ,1394.27, 2 ,1394.27, 2 , 0 , 0 , 0 ,,
     1.4     1.4
      95   110.5
     1.4     1.4
      95   110.5
Abutment Skew #Up #Dn= , 2 , 2
 1274.77 1308.27
  109.41    97.7
 1274.77 1308.27
  109.31    97.6
Abutment Skew #Up #Dn= , 2 , 2
 1417.37 1454.46
   96.68  109.43
 1417.37 1454.46
   96.58  109.33
BR Coef=-1 , 1 , 1 ,0.9, 0 ,,,0.8,0,1.2,0,
WSPro=,,,, 1 ,,,, 0 ,,,, 0 ,,,,-1 ,-1 ,-1 , 0 , 0 , 0 , 0 , 0
BC Design=,, 0 ,, 0 ,,,,,,
BC Use User HTab Curves=0
BC User HTab FreeFlow(D)= 0

Type RM Length L Ch R = 1 ,58077.66,761.14,687.73,585.14
BEGIN DESCRIPTION:
Downstream Section - SH 6
END DESCRIPTION:
XS GIS Cut Line= 6
 3032207.048955613878864.21127333031719.1089866213878286.1963532
3031735.5961583613877803.75013963031733.0020034513877660.0486553
3031732.17949852 13877544.0711973031824.8312161113875431.5278499
#Sta/Elev= 30
       0  114.83  532.49  114.84  557.37  112.74  731.55  111.15  995.31  110.78
 1035.12  112.42 1050.05  110.78 1109.77  111.92 1134.65  110.23 1154.56  111.65
 1184.42  109.83 1219.25  110.44 1258.98  110.64 1268.89  109.39 1298.63   99.62
 1328.37   98.84  1358.1   94.56 1411.88   98.35 1450.54  108.62 1643.83  111.51
 2303.67  111.26 2318.67  109.56 2518.62  109.11 2653.58  111.42 2733.56  111.32
 2758.56  109.52 2843.54  111.21 3043.48  109.57 3495.39  112.64 3613.42  111.71
#Mann= 4 ,-1 , 0
       0      .1       0 1219.25     .07       0 1258.98     .04       0
 1450.54     .07       0
#XS Ineff= 3 ,-1
       0 1274.97  110.66 1454.26 2043.74  109.07 2043.74 3613.42  110.18
Permanent Ineff=
       F       F       F
Bank Sta=1258.98,1450.54
XS Rating Curve= 0 ,0
Exp/Cntr=0.5,0.3

Type RM Length L Ch R = 1 ,57389.92,63.78,70.21,100.02
XS GIS Cut Line= 6
3032932.8798530313878111.96999563032474.9401521113877517.2398859
3032326.2501607813877416.12985183032207.3101099413877332.8698478
3031987.26002511 13877112.8200913031851.51948294 13875735.539381
#Sta/Elev= 30
       0  113.73   79.53  114.77  139.19  110.66  253.52  114.23  357.91  111.92
  437.44  113.54   546.8  109.76  626.34  111.16  698.12  109.56  810.55  111.79
  860.49   97.94  883.16   94.51  900.45   97.92  988.49   97.81 1056.25  102.01
 1090.42  108.04 1115.12  106.64 1166.41  108.52 1651.61  110.85 2016.33   109.1
  2061.3  111.05 2101.27  108.86 2201.19  110.25 2216.18  108.02 2241.16  109.84
 2271.14  108.44 2341.08  110.42 2635.86  109.32  2700.8  111.48 2770.75  111.29
#Mann= 5 ,-1 , 0
       0     .15       0  698.12     .07       0  810.55     .04       0
 1090.42     .07       0 1166.41      .1       0
#XS Ineff= 2 ,-1
       0  810.55  111.79 1651.61 2770.75  110.85
Permanent Ineff=
       F       F
Bank Sta=810.55,1090.42
XS Rating Curve= 0 ,0
Exp/Cntr=0.3,0.1

Type RM Length L Ch R = 1 ,57319.71,486.65,494.81,400.46
XS GIS Cut Line= 4
3032896.3736924413877979.35904033032499.1799330313877465.4801469
3032191.6700493513877209.22016073031890.2457834513875727.7939897
#Sta/Elev= 30
       0   110.3   79.94  114.43  184.85  112.33  234.81  113.94  324.74  113.07
   374.7  109.81  534.58  112.65  574.68  109.39  609.52  108.76  679.14  111.76
  689.02  110.61  728.56   97.78750.4399   94.51  773.03   97.73   852.1   97.77
  891.64  101.15  921.29  108.11  955.88  106.35  990.47  110.61  1043.7  109.28
 1578.65  110.95 1613.58  108.66 1808.16  108.48 1863.05  111.57 2002.75  107.23
 2052.64  109.34 2097.55  108.41 2177.38  110.23 2347.01  108.59 2561.55  111.53
#Mann= 5 ,-1 , 0
       0     .15       0  574.68     .07       0  679.14     .04       0
  921.29     .07       0  1043.7      .1       0
#XS Ineff= 2 ,-1
       0  679.14  111.76 1438.95 2561.55   110.9
Permanent Ineff=
       F       F
#Block Obstruct= 2 , 0
       0   79.94  114.43               0
Bank Sta=679.14,921.29
XS Rating Curve= 0 ,0
Exp/Cntr=0.5,0.3

Type RM Length L Ch R = 1 ,56824.9 ,50.42,54.23,51.29
BEGIN DESCRIPTION:
Upstream Section - 12" WATERLINE
END DESCRIPTION:
XS GIS Cut Line= 6
3033170.2740632713877517.04500443032739.7424440213877037.0472767
3032699.5830755213877022.87374863032467.2331465313876947.7036234
3032358.1293621113876918.21385293031959.7594239413875771.7230357
#Sta/Elev= 30
       0  112.46   84.97  110.91  194.94  112.56  229.93  110.02   304.9  110.92
  349.89  108.96  444.86  112.33  488.49  109.48  554.82  108.14  658.99  111.55
  673.18  110.18  727.11   95.16  764.98   96.45  804.87   96.04  809.92   94.47
  815.57   96.52  842.01   96.31  902.25  107.17  975.81  107.69  995.47  105.68
 1015.12  109.75 1040.88  109.72 1159.48  109.95 1199.44  105.85 1349.29  109.01
 1434.45  107.47 1753.86  106.38  1839.9  108.04 2203.39  109.71 2258.34  111.49
#Mann= 7 ,-1 , 0
       0     .15       0  488.49     .07       0  658.99     .04       0
  902.25     .07       0 1040.88      .1       0 1434.45     .15       0
  1839.9      .1       0
#XS Ineff= 2 ,-1
       0  658.99  111.55 1124.52 2258.34  110.72
Permanent Ineff=
       F       F
#Block Obstruct= 2 , 0
       0  139.95  112.34               0
Bank Sta=658.99,902.25
XS Rating Curve= 0 ,0
Exp/Cntr=0.5,0.3

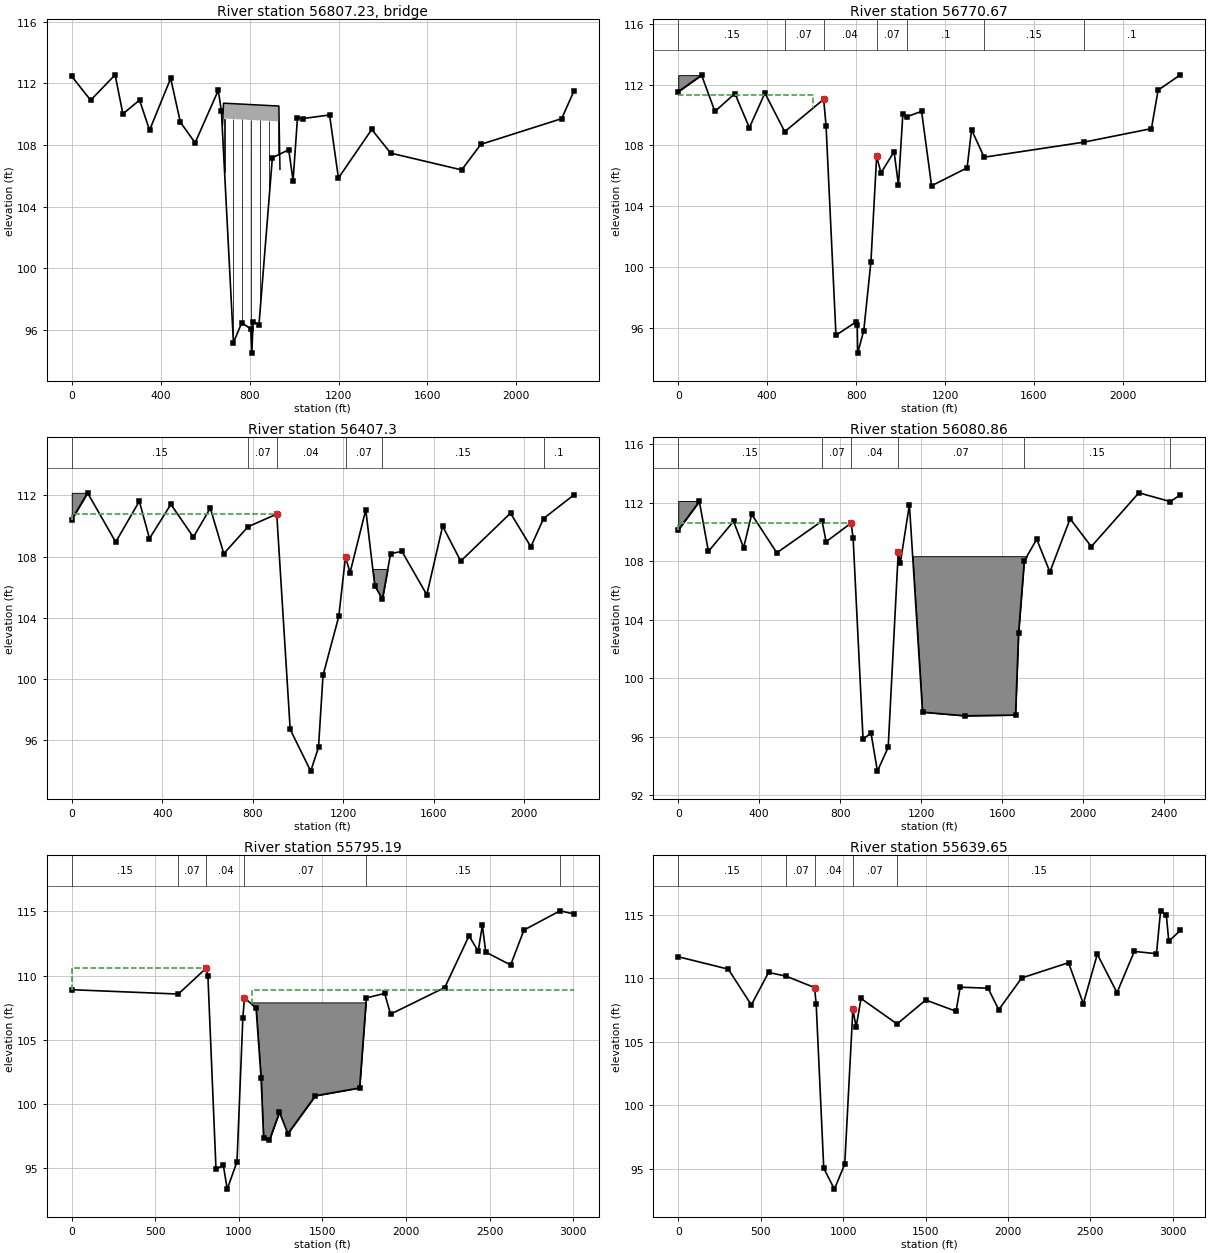
Type RM Length L Ch R = 3 ,56807.23,,,
BEGIN DESCRIPTION:
12" WATERLINE
END DESCRIPTION:
Node Name=12" WATERLINE
Bridge Culvert--1,0,-1,-1, 0
Deck Dist Width WeirC Skew NumUp NumDn MinLoCord MaxHiCord MaxSubmerge Is_Ogee
16.5,1,2.6,0, 54, 54, , , 0.98, 0, 0,0,,
  677.91  682.65  687.38  692.26  697.13  702.01  706.89  711.77  716.65  721.52
   726.4  731.28  736.16  741.04  745.91  750.79  755.67  760.55  765.42   770.3
  775.18  780.06  784.94  789.81  794.69  799.57  804.45  809.34  814.23  819.12
  824.01   828.9  833.79  838.68  843.57  848.46  853.35  858.24  863.13  868.02
  872.91   877.8  882.69  887.58  892.47  897.36  902.25  907.14  912.03  916.92
  921.81  926.69  931.58   936.5
  109.29  110.72  110.71  110.71  110.71   110.7   110.7   110.7  110.69  110.69
  110.69  110.68  110.68  110.67  110.67  110.67  110.66  110.66  110.66  110.65
  110.65  110.65  110.64  110.64  110.63  110.63  110.63  110.62  110.62  110.62
  110.61  110.61   110.6   110.6   110.6  110.59  110.59  110.59  110.58  110.58
  110.58  110.57  110.57  110.56  110.56  110.56  110.55  110.55  110.55  110.54
  110.54  110.54  110.53  106.42
       0  109.72  109.71  109.71  109.71   109.7   109.7   109.7  109.69  109.69
  109.69  109.68  109.68  109.67  109.67  109.67  109.66  109.66  109.66  109.65
  109.65  109.65  109.64  109.64  109.63  109.63  109.63  109.62  109.62  109.62
  109.61  109.61   109.6   109.6   109.6  109.59  109.59  109.59  109.58  109.58
  109.58  109.57  109.57  109.56  109.56  109.56  109.55  109.55  109.55  109.54
  109.54  109.54  109.53       0
  677.91  682.65  687.38  692.26  697.13  702.01  706.89  711.77  716.65  721.52
   726.4  731.28  736.16  741.04  745.91  750.79  755.67  760.55  765.42   770.3
  775.18  780.06  784.94  789.81  794.69  799.57  804.45  809.34  814.23  819.12
  824.01   828.9  833.79  838.68  843.57  848.46  853.35  858.24  863.13  868.02
  872.91   877.8  882.69  887.58  892.47  897.36  902.25  907.14  912.03  916.92
  921.81  926.69  931.58   936.5
  109.29  110.72  110.71  110.71  110.71   110.7   110.7   110.7  110.69  110.69
  110.69  110.68  110.68  110.67  110.67  110.67  110.66  110.66  110.66  110.65
  110.65  110.65  110.64  110.64  110.63  110.63  110.63  110.62  110.62  110.62
  110.61  110.61   110.6   110.6   110.6  110.59  110.59  110.59  110.58  110.58
  110.58  110.57  110.57  110.56  110.56  110.56  110.55  110.55  110.55  110.54
  110.54  110.54  110.53  106.42
       0  109.72  109.71  109.71  109.71   109.7   109.7   109.7  109.69  109.69
  109.69  109.68  109.68  109.67  109.67  109.67  109.66  109.66  109.66  109.65
  109.65  109.65  109.64  109.64  109.63  109.63  109.63  109.62  109.62  109.62
  109.61  109.61   109.6   109.6   109.6  109.59  109.59  109.59  109.58  109.58
  109.58  109.57  109.57  109.56  109.56  109.56  109.55  109.55  109.55  109.54
  109.54  109.54  109.53       0
Pier Skew, UpSta & Num, DnSta & Num=  ,687.22, 2 ,687.22, 2 , 0 , 0 , 0 ,,
       1       1
      90   110.2
       1       1
      90   110.2
Pier Skew, UpSta & Num, DnSta & Num=  ,726.22, 2 ,726.22, 2 , 0 , 0 , 0 ,,
       1       1
      90   110.2
       1       1
      90   110.2
Pier Skew, UpSta & Num, DnSta & Num=  ,766.72, 2 ,766.72, 2 , 0 , 0 , 0 ,,
       1       1
      90   110.2
       1       1
      90   110.2
Pier Skew, UpSta & Num, DnSta & Num=  ,805.92, 2 ,805.92, 2 , 0 , 0 , 0 ,,
       1       1
      90   110.2
       1       1
      90   110.2
Pier Skew, UpSta & Num, DnSta & Num=  ,846.92, 2 ,846.92, 2 , 0 , 0 , 0 ,,
       1       1
      90   110.2
       1       1
      90   110.2
Pier Skew, UpSta & Num, DnSta & Num=  ,887.62, 2 ,887.62, 2 , 0 , 0 , 0 ,,
       1       1
      90   110.2
       1       1
      90   110.2
Pier Skew, UpSta & Num, DnSta & Num=  ,926.52, 2 ,926.52, 2 , 0 , 0 , 0 ,,
       1       1
      90   110.2
       1       1
      90   110.2
BR Coef=-1 , 1 , 1 ,0.9, 0 ,,,0.8,-1,1.2,0,
WSPro=,,,, 1 ,,,, 0 ,,,, 0 ,,,,-1 ,-1 ,-1 , 0 , 0 , 0 , 0 , 0
BC Design=,, 0 ,, 0 ,,,,,,
BC Use User HTab Curves=0
BC User HTab FreeFlow(D)= 0

Type RM Length L Ch R = 1 ,56770.67,329.33,363.37,498.62
BEGIN DESCRIPTION:
Downstream Section - 12" WATERLINE
END DESCRIPTION:
XS GIS Cut Line= 6
3033167.1812216913877463.39878623032736.6496024413876983.4010585
3032696.4902339413876969.22753043032464.1403049413876894.0574052
3032355.0365205313876864.56763483031956.6665823613875718.0768175
#Sta/Elev= 30
       0  111.53  104.97  112.62  164.95  110.23  254.92  111.41   319.9  109.16
  389.87  111.44     479   108.9  654.25  111.03  664.93  109.28   709.5   95.51
  799.65   96.38  805.15   96.18  807.11   94.33  834.46   95.81  866.67  100.33
  892.47  107.28  912.03  106.19   970.9  107.58  990.55  105.39 1010.21  110.04
 1028.03  109.88 1094.55  110.24  1139.5  105.34 1299.34  106.52 1319.32  109.03
 1375.95  107.22 1824.47  108.21 2128.47   109.1 2158.44  111.63 2258.34  112.64
#Mann= 7 ,-1 , 0
       0     .15       0     479     .07       0  654.25     .04       0
  892.47     .07       0 1028.03      .1       0 1375.95     .15       0
 1824.47      .1       0
#XS Ineff= 2 ,-1
       0   604.8  111.32 1094.55 2258.34  110.24
Permanent Ineff=
       F       F
#Block Obstruct= 2 , 0
       0  104.97  112.62               0
Bank Sta=654.25,892.47
XS Rating Curve= 0 ,0
Exp/Cntr=0.5,0.3

Type RM Length L Ch R = 1 ,56407.3 ,302.04,326.44,391.76
Node Name=H
XS GIS Cut Line= 5
3033361.6480243713877416.13214843032835.2589852813876716.1706219
3032723.7500219513876588.20991983032509.2399522813876373.6998501
3032047.0135145313875637.0218615
#Sta/Elev= 30
       0  110.42   69.67  112.17  194.07  108.95  298.57  111.62  343.35  109.18
   437.9  111.42  537.42  109.27  612.07  111.17  671.78  108.19   778.7  109.95
  905.76  110.78  965.14   96.69 1055.92   93.96 1090.29   95.52 1110.18  100.22
 1179.81  104.08 1209.65  107.99 1229.54  106.94 1299.16  111.06 1338.95  106.09
 1372.43  105.21 1408.87  108.19 1458.86  108.34 1568.82   105.5 1638.79  109.99
 1718.76   107.7 1938.68  110.84 2028.65  108.64 2084.76  110.49 2218.58  112.03
#Mann= 6 ,-1 , 0
       0     .15       0   778.7     .07       0  905.76     .04       0
 1209.65     .07       0 1372.43     .15       0 2084.76      .1       0
#XS Ineff= 2 ,-1
       0  905.76  110.78 1299.16 2218.58  109.63
Permanent Ineff=
       F       F
#Block Obstruct= 2 ,-1
       0   69.67  112.17 1294.19 1408.87  107.19
Bank Sta=905.76,1209.65
XS Rating Curve= 0 ,0
Exp/Cntr=0.3,0.1

Type RM Length L Ch R = 1 ,56080.86,266.12,285.67,313.93
XS GIS Cut Line= 5
3033392.4399575313877410.24994233033118.6357151113876647.8977925
3033063.3999331913876516.71006283032661.1901076913875873.1700113
3032157.8390802713875291.4247837
#Sta/Elev= 30
       0  110.15  104.36   112.1  149.09  108.68  273.32  110.74  323.02  108.93
  362.77  111.22  487.01  108.58  710.64  110.76  730.52  109.34  854.21  110.62
  864.02  109.59  913.11   95.81  952.37   96.24  984.07   93.63 1037.25   95.26
 1087.18  108.66 1097.16  107.88  1142.1  111.88    1207   97.67  1416.7   97.42
 1666.33   97.47 1681.31  103.06 1709.54  108.03 1771.21  109.51 1836.15  107.27
 1936.06  110.91 2040.96  109.01 2275.73  112.69 2431.04  112.09 2480.54  112.55
#Mann= 6 ,-1 , 0
       0     .15       0  710.64     .07       0  854.21     .04       0
 1087.18     .07       0 1709.54     .15       0 2431.04      .1       0
#XS Ineff= 2 ,-1
       0  854.21  110.62  1142.1 2480.54  109.53
Permanent Ineff=
       F       F
#Block Obstruct= 2 ,-1
       0   99.39  112.13  1142.1 1726.25  108.35
Bank Sta=854.21,1087.18
XS Rating Curve= 0 ,0
Exp/Cntr=0.3,0.1

Type RM Length L Ch R = 1 ,55795.19,146.51,155.55,137.19
XS GIS Cut Line= 5
3033454.4352403613877328.42103783033363.6401463613876563.4399562
 3033278.220041613876242.2601524 3032683.012570613875009.3065815
3032437.3529569513874537.0844288
#Sta/Elev= 30
       0   108.9   637.4  108.56  805.07  110.59  814.62  109.95  862.99   94.89
  906.64   95.23  930.08   93.35  988.68   95.49 1023.65  106.71 1033.25  108.27
  1102.7  107.47 1132.68  102.02 1147.67   97.36 1182.64   97.18  1242.6   99.35
 1292.57   97.67 1457.46  100.63 1722.29  101.24 1762.59  108.26 1872.19  108.61
 1907.17  106.99 2231.96  109.07 2376.86   113.1 2431.82   111.9 2456.81  113.93
 2476.77  111.83 2626.02  110.83 2705.61  113.55 2921.14  115.05  3004.1  114.81
#Mann= 6 ,-1 , 0
       0     .15       0   637.4     .07       0  805.07     .04       0
 1033.25     .07       0 1762.59     .15       0 2921.14      .1       0
#XS Ineff= 2 ,-1
       0  805.07  110.59 1077.89  3004.1  108.91
Permanent Ineff=
       F       F
#Block Obstruct= 1 ,-1
 1077.89 1812.23  107.91
Bank Sta=805.07,1033.25
XS Rating Curve= 0 ,0
Exp/Cntr=0.3,0.1

Type RM Length L Ch R = 1 ,55639.65,16.34,34.67,76.97
XS GIS Cut Line= 5
3033526.9429693713877324.30162343033492.4200725313876418.3900494
3033376.2300161913876168.13005133033318.7872176913875099.5183434
3033158.2553865313874323.1777044
#Sta/Elev= 30
       0   111.7  303.85  110.72  443.32   107.9  547.93  110.46  654.16  110.17
  826.87  109.27  836.83  107.95  882.68   95.02  947.19   93.38 1010.04   95.35
 1059.31  107.56 1079.02  106.14 1108.58  108.41 1327.52   106.4 1501.04  108.29
 1685.21   107.4  1710.1   109.3 1879.33  109.22 1944.04  107.52 2083.41  110.03
 2367.31  111.23 2457.06     108 2541.82   111.9 2661.48  108.87 2766.19  112.12
 2900.81  111.94 2925.74  115.32 2960.64  114.96  2975.6  112.93  3045.4  113.77
#Mann= 5 ,-1 , 0
       0     .15       0  654.16     .07       0  826.87     .04       0
 1059.31     .07       0 1327.52     .15       0
#XS Ineff= 2 ,-1
       0  547.93  110.46 1108.58  3045.4  108.41
Permanent Ineff=
       F       F
Bank Sta=826.87,1059.31
XS Rating Curve= 0 ,0
Exp/Cntr=0.3,0.1

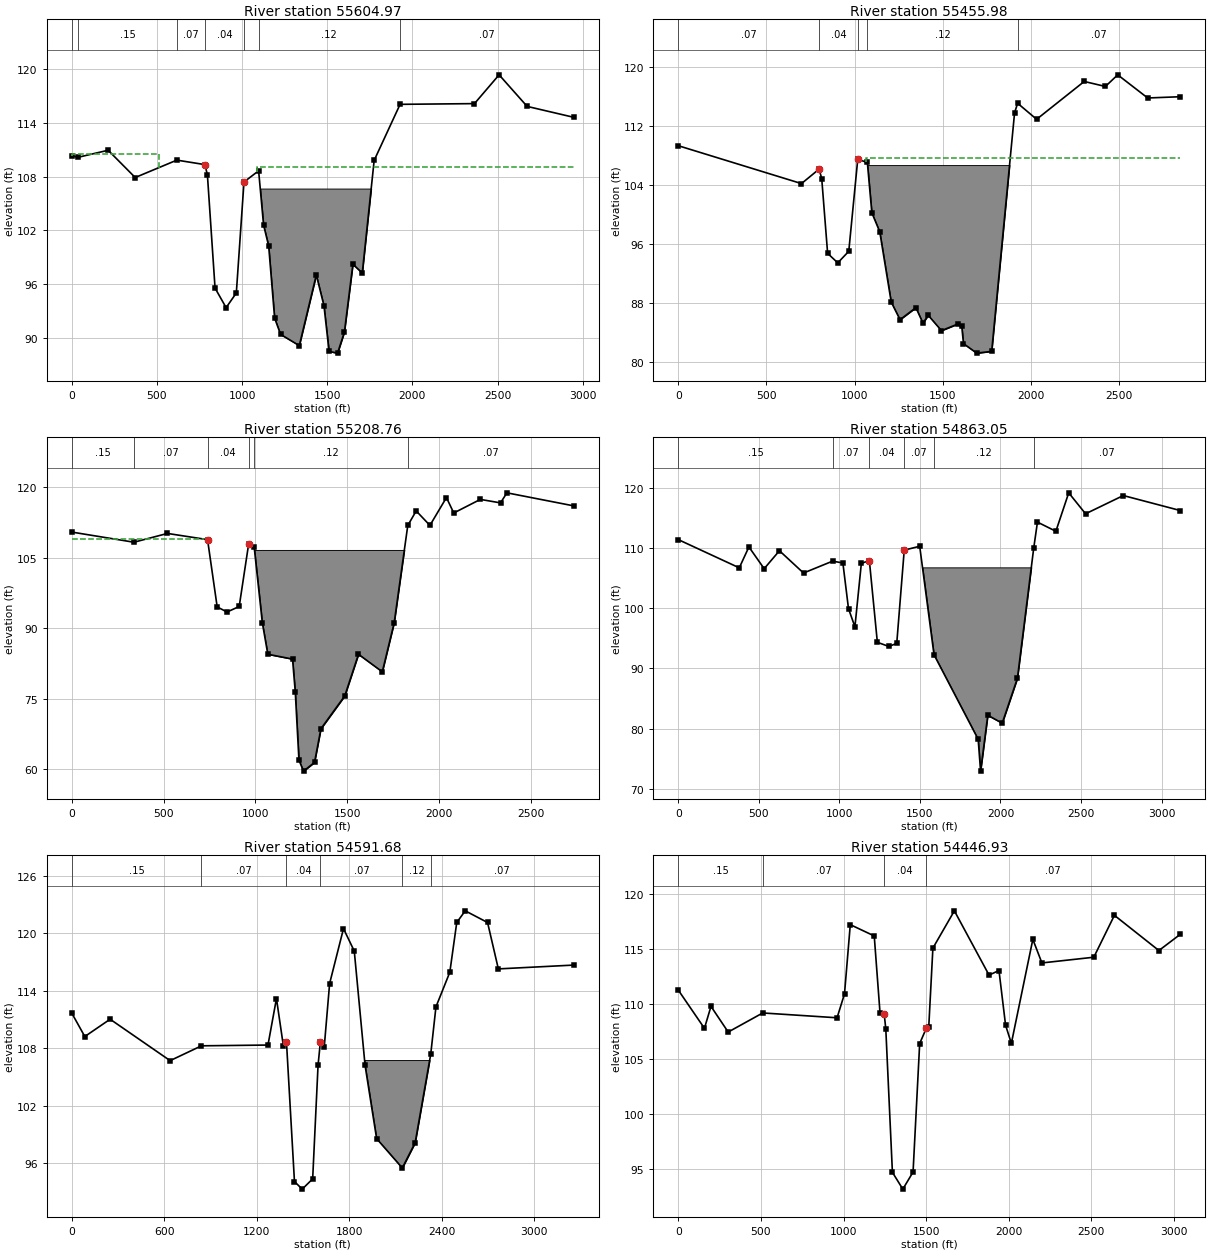
Type RM Length L Ch R = 1 ,55604.97,171.09,148.99,129.37
XS GIS Cut Line= 4
3033591.3368694513877279.52743483033515.88524869 13876778.576665
3033493.5499915313875279.78766793033518.1086694413874337.4165211
#Sta/Elev= 30
       0  110.33   36.16  110.15  213.57  110.94   372.5   107.9  617.04  109.84
  781.41  109.34   796.4  108.21  841.37   95.57  906.37   93.39  966.28   95.03
 1011.25   107.4 1097.23  108.65 1126.17  102.61 1156.15  100.28 1191.12   92.23
  1226.1   90.41 1336.02   89.16 1435.95   97.04 1480.92    93.6  1510.9   88.51
 1560.86   88.32 1600.84   90.67  1650.8   98.23 1705.76   97.25 1775.71  109.81
 1927.85  116.06 2364.67  116.14 2509.31  119.35 2673.91  115.83 2948.23  114.61
#Mann= 7 ,-1 , 0
       0     .07       0   36.16     .15       0  617.04     .07       0
  781.41     .04       0 1011.25     .07       0 1097.23     .12       0
 1927.85     .07       0
#XS Ineff= 2 ,-1
       0   511.6  110.51  1086.2 2948.23  109.07
Permanent Ineff=
       F       F
#Block Obstruct= 1 ,-1
  1086.2 1770.72  106.67
Bank Sta=781.41,1011.25
XS Rating Curve= 0 ,0
Exp/Cntr=0.3,0.1

Type RM Length L Ch R = 1 ,55455.98,267.87,247.22,225.87
XS GIS Cut Line= 5
3033650.00866811 13877269.7489113033679.9938443613876467.2170515
3033628.6238683613876228.71326343033527.7753167713875260.2302923
3033540.3714201913874436.1377804
#Sta/Elev= 30
       0   109.3  698.34  104.16   798.1  106.12  813.05  104.85  846.51    94.7
  903.99   93.41  966.33   94.98 1017.19  107.45 1071.58  107.03    1097  100.21
 1141.94   97.62 1206.86   88.09 1256.79   85.71 1346.67   87.34 1386.62   85.24
 1416.58    86.3 1491.48   84.22 1586.36   85.14 1606.33   84.85 1616.32   82.46
 1691.22   81.17 1776.11   81.41 1905.94  113.78 1923.28  115.05 2030.78  112.88
 2300.52  118.01  2420.4  117.33 2490.33  118.91 2660.17  115.77 2844.99  115.94
#Mann= 5 ,-1 , 0
       0     .07       0   798.1     .04       0 1017.19     .07       0
 1071.58     .12       0 1923.28     .07       0
#XS Ineff= 2 ,-1
       0   798.1  106.12 1062.05 2844.99  107.67
Permanent Ineff=
       F       F
#Block Obstruct= 1 ,-1
 1062.05  1935.9  106.67
Bank Sta=798.1,1017.19
XS Rating Curve= 0 ,0
Exp/Cntr=0.3,0.1

Type RM Length L Ch R = 1 ,55208.76,377.71,345.71,312.68
Node Name=G
XS GIS Cut Line= 5
3034114.6580012713877110.03039843033967.7291612813876461.0950165
3033839.0496286213876170.37479743033571.7794938513875255.3408664
3033573.9471404413874456.1935145
#Sta/Elev= 30
       0  110.46  338.88   108.3  521.37  110.17  739.87  108.85  792.28   94.54
845.9399   93.45   912.3   94.63  963.42  107.83  994.09  107.21 1038.19    91.2
 1068.13   84.47 1202.89   83.44 1217.86   76.42 1237.82   61.95 1262.78    59.6
 1322.67   61.46 1357.61   68.62 1487.37    75.6 1562.24   84.46    1692   80.73
 1756.88   91.19 1830.81  111.86 1876.66  114.96 1951.54  111.88 2041.44   117.8
  2081.4  114.52 2226.25  117.41 2336.14  116.67  2371.1  118.81 2735.72  116.03
#Mann= 6 ,-1 , 0
       0     .15       0  338.88     .07       0  739.87     .04       0
  963.42     .07       0  994.09     .12       0 1830.81     .07       0
#XS Ineff= 2 ,-1
       0     720  109.08  963.42 2735.72  107.83
Permanent Ineff=
       F       F
#Block Obstruct= 1 ,-1
  988.28 1878.66  106.66
Bank Sta=739.87,963.42
XS Rating Curve= 0 ,0
Exp/Cntr=0.3,0.1

Type RM Length L Ch R = 1 ,54863.05,279.37,271.36,262.9
XS GIS Cut Line= 5
3034979.0194615313877120.41784483034272.5198902813876204.6700044
3034070.9198997813875979.15995683033586.4474435313875250.4514404
3033593.8558932813874468.0855511
#Sta/Elev= 30
       0  111.37  378.89  106.68  438.71  110.15  533.43  106.54  628.16  109.52
  777.72  105.82  958.09  107.79    1022  107.49  1056.9   99.89 1096.78    96.9
 1136.66  107.43 1186.36  107.88 1236.01   94.32 1306.82   93.64 1356.31   94.13
 1402.86  109.62 1498.86  110.26 1587.69   92.26 1861.81   78.22 1876.73   72.94
 1921.48   82.21 2010.97    80.9 2105.44   88.36 2206.76  109.99 2229.74  114.27
 2344.12  112.75 2423.85  119.13  2528.5  115.65 2762.72  118.68 3116.54  116.19
#Mann= 6 ,-1 , 0
       0     .15       0  958.09     .07       0 1186.36     .04       0
 1402.86     .07       0 1587.69     .12       0 2206.76     .07       0
#XS Ineff= 2 ,-1
       0 1186.36  107.88 1454.13 3116.54  107.88
Permanent Ineff=
       F       F
#Block Obstruct= 1 ,-1
 1454.13 2244.65  106.76
Bank Sta=1186.36,1402.86
XS Rating Curve= 0 ,0
Exp/Cntr=0.3,0.1

Type RM Length L Ch R = 1 ,54591.68,148.82,144.76,140.65
XS GIS Cut Line= 4
3035473.8111228613876964.1678293 3035204.379575113876705.9764165
3033728.9697962713875297.90902273033639.8590821213874457.9858338
#Sta/Elev= 30
       0  111.66   84.59  109.21  248.78  111.02   638.1  106.69  841.59  108.24
 1272.94  108.32 1327.93  113.18 1372.92  108.22 1392.91  108.65 1444.77   94.05
 1495.09   93.26 1562.87   94.33 1597.86  106.22 1612.86  108.64 1637.85   108.1
 1672.84  114.75 1762.82  120.49  1832.8  118.14 1902.78   106.2 1977.76   98.54
 2144.31   95.47  2227.7   98.11 2328.87  107.37 2362.67  112.31 2452.64  115.93
 2497.62  121.13  2552.6  122.35 2697.54  121.13 2767.51  116.28 3257.31  116.68
#Mann= 6 ,-1 , 0
       0     .15       0  841.59     .07       0 1392.91     .04       0
 1612.86     .07       0 2144.31     .12       0 2328.87     .07       0
#XS Ineff= 2 ,-1
       0 1392.91  108.65 1612.86 3257.31  108.64
Permanent Ineff=
       F       F
#Block Obstruct= 1 ,-1
  1852.8 2422.65  106.75
Bank Sta=1392.91,1612.86
XS Rating Curve= 0 ,0
Exp/Cntr=0.3,0.1

Type RM Length L Ch R = 1 ,54446.93,597.64,611.32,626.17
XS GIS Cut Line= 4
3035516.0495554513876734.28279033035216.6236451113876467.2170515
3033912.6308462813875316.2751277 3033692.727414713874446.3792297
#Sta/Elev= 30
       0  111.28  158.51  107.79  198.13  109.79  302.16  107.45  511.29  109.19
  960.99  108.75 1005.97  110.93 1040.95  117.24 1185.89  116.21 1220.88  109.19
 1245.87  109.13 1255.86  107.72 1295.85   94.66 1358.88   93.13 1420.79   94.69
 1460.78   106.4 1500.76  107.79 1515.75  107.92 1540.74   115.1 1670.69   118.5
  1880.6  112.64 1940.58  113.06 1980.56  108.07 2015.54  106.42 2145.48   115.9
 2200.31  113.75 2514.35  114.27 2638.97  118.09 2908.14  114.88 3037.74  116.36
#Mann= 4 ,-1 , 0
       0     .15       0  511.29     .07       0 1245.87     .04       0
 1500.76     .07       0
#XS Ineff= 2 ,-1
       0 1245.87  109.13 1540.74 3037.74  109.13
Permanent Ineff=
       F       F
#Block Obstruct= 1 ,-1
 1920.58 2145.48  106.75
Bank Sta=1245.87,1500.76
XS Rating Curve= 0 ,0
Exp/Cntr=0.3,0.1