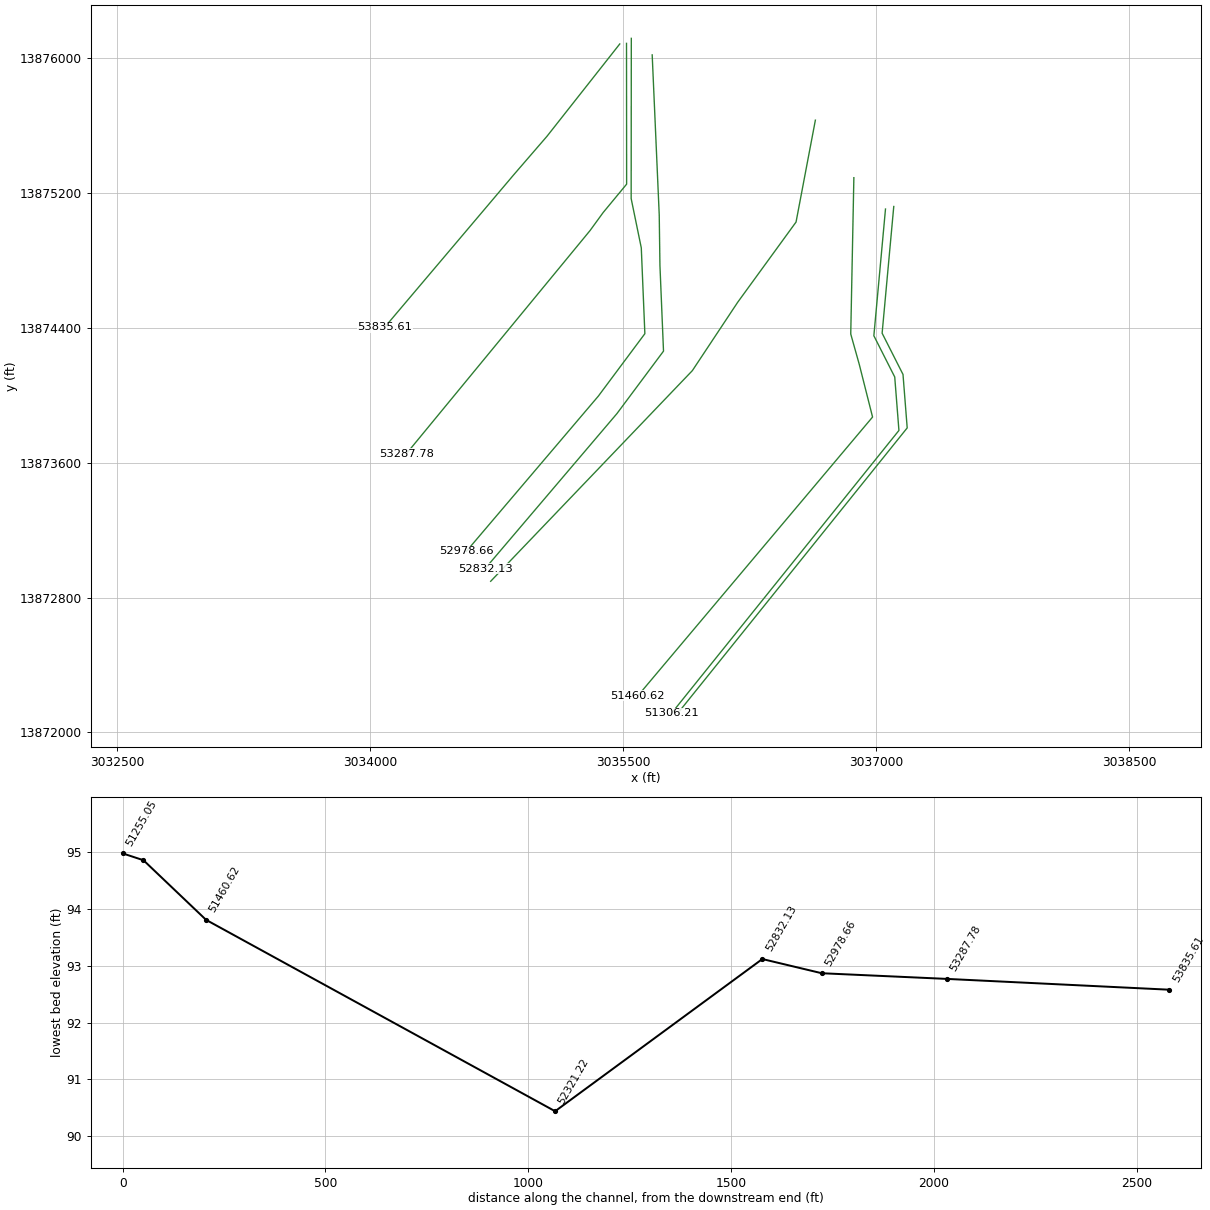
HEC-RAS study U100-00-00.prj: U100-00-00

--- U100-00-00.g01 (geometry) --- (continued)

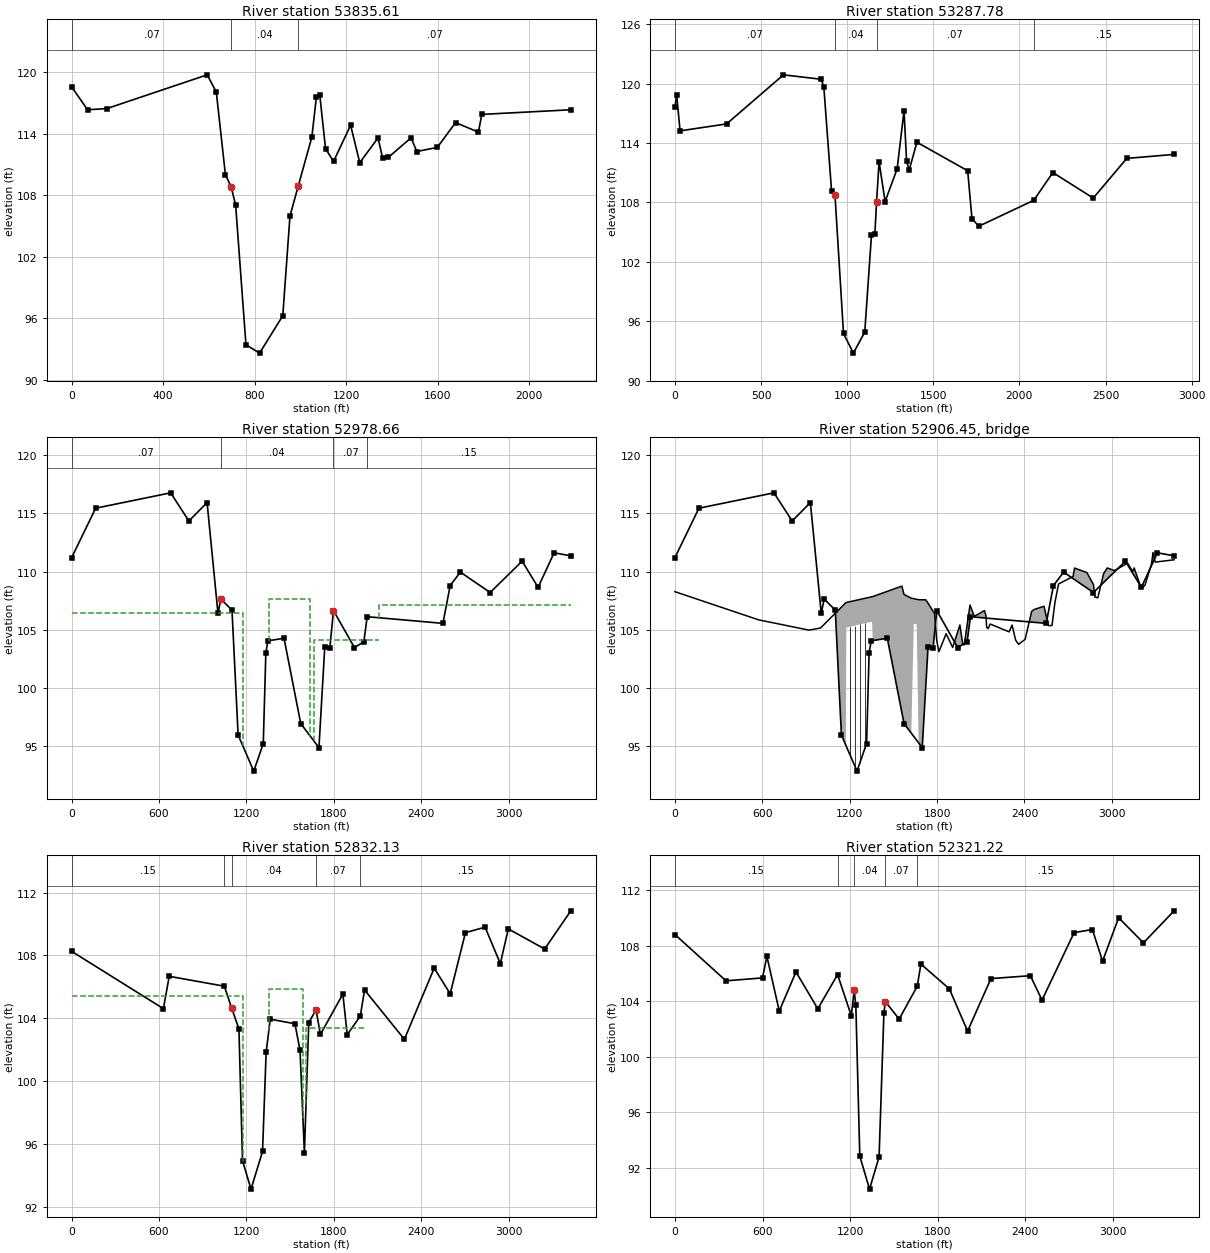
Type RM Length L Ch R = 1 ,53835.61,545.4,547.83,558.08
Node Name=F
XS GIS Cut Line= 4
3035479.6464130313876082.34741443035048.1400581913875534.9800709
3034853.3799490313875309.47002323034086.7269547713874403.6191446
#Sta/Elev= 30
       0  118.56    69.7  116.32  154.34  116.44  592.45  119.73  632.28  118.06
  672.11  109.98     697  108.81  716.86  107.02  761.91    93.4  821.52   92.58
  922.86   96.23  954.25  105.95     990  108.85 1049.82  113.65 1069.76  117.58
 1084.72  117.72 1109.65  112.54 1144.56  111.28 1219.35  114.81 1259.24  111.16
 1339.02  113.57 1358.97  111.65  1383.9  111.67 1483.63  113.59 1508.56  112.25
 1598.31  112.65 1678.09  115.07 1777.82  114.14 1792.78  115.87  2181.7  116.32
#Mann= 3 ,-1 , 0
       0     .07       0     697     .04       0     990     .07       0
Bank Sta=697,990
XS Rating Curve= 0 ,0
Exp/Cntr=0.3,0.1

Type RM Length L Ch R = 1 ,53287.78,144.32,309.11,727.62
XS GIS Cut Line= 5
3035519.7687081113876086.07969043035520.4425912813875251.1824101
3035381.2886701113875082.90321913035303.6211745313874976.1107818
3034215.1935613613873653.6393453
#Sta/Elev= 30
       0  117.63      10  118.86      30  115.22  299.96  115.92  629.92  120.88
  849.78  120.43  864.67  119.63  909.34  109.16  929.19  108.76  978.82   94.76
 1035.98   92.77 1102.16    94.9 1141.29  104.73 1160.85   104.8 1170.63  108.01
  1185.3   112.1 1220.26  108.08 1290.17  111.38 1330.12  117.25  1345.1  112.15
 1360.08  111.27 1405.02  114.07 1699.64  111.19 1724.61  106.35 1764.55  105.59
 2083.79  108.21 2193.99  111.01 2428.69  108.43 2623.43  112.44 2898.07  112.84
#Mann= 4 ,-1 , 0
       0     .07       0  929.19     .04       0 1170.63     .07       0
 2083.79     .15       0
#XS Ineff= 1 ,-1
  1185.3 2898.07     109
Permanent Ineff=
       F
Bank Sta=929.19,1170.63
XS Rating Curve= 0 ,0
Exp/Cntr=0.5,0.3

Type RM Length L Ch R = 1 ,52978.66,230.02,146.53,125.41
BEGIN DESCRIPTION:
Upstream Section - ADDICKS-SATSUMA RD
Main Chan. Skewed 45 Degrees
END DESCRIPTION:
XS GIS Cut Line= 6
3035548.21615778   13876115.80243035547.2929312713875165.8029877
3035607.34300803 13874873.4505543035628.5808264513874364.4404172
3035352.5561160313873994.12980613034570.4927195313873074.2743624
#Sta/Elev= 30
       0   111.2     165  115.45     680  116.77     805  114.35     930  115.93
 1004.72  106.42 1024.61  107.651100.936   106.71143.143   95.971250.354   92.87
1315.769   95.241333.425  103.031347.553  104.06 1458.23  104.28 1573.11   96.95
 1697.98   94.89 1737.93  103.53 1772.81  103.45 1797.64  106.66 1941.66  103.48
 2006.22  103.98 2029.13  106.13 2549.06  105.56 2598.96  108.81 2668.81  109.96
 2873.36  108.21 3092.89   110.9 3202.65  108.65 3312.41  111.62 3427.16  111.36
#Mann= 4 ,-1 , 0
       0     .07       0 1024.61     .04       0 1797.64     .07       0
 2029.13     .15       0
#XS Ineff= 4 ,-1
       0 1176.25  106.42 1353.73 1638.21  107.66 1661.22 2110.52  104.17
 2110.52 3427.16  107.16
Permanent Ineff=
       F       F       F       F
Bank Sta=1024.61,1797.64
XS Rating Curve= 0 ,0
Exp/Cntr=0.5,0.3

Type RM Length L Ch R = 3 ,52906.45,,,
BEGIN DESCRIPTION:
ADDICKS-SATSUMA RD
END DESCRIPTION:
Node Name=ADDICKS-SATSUMA
Bridge Culvert--1,0,-1,-1, 0
Deck Dist Width WeirC Skew NumUp NumDn MinLoCord MaxHiCord MaxSubmerge Is_Ogee
54,50,2.6,0, 60, 60, , , 0.98, 0, 0,0,,
       0     575     920  999.74 1173.84 1176.54 1353.39 1358.34 1558.13 1573.11
 1623.06  1639.8 1659.89    1673 1722.95 1782.74 1797.64 1812.54  1862.2  1906.9
 1956.56 1976.43 1986.36 2026.09 2055.89 2125.42 2135.35 2140.32 2150.25 2165.15
 2294.62 2314.57 2339.52 2359.48 2404.38 2449.28 2464.25  2534.1 2564.03 2588.98
 2608.94 2633.88 2733.67 2743.65 2828.46 2873.37 2883.34  2903.3 2943.21 2968.16
 3018.05 3107.86 3142.78 3152.76 3202.65  3227.6  3272.5 3282.48 3297.45 3427.17
  108.28  105.86  104.98  105.16  107.34  107.35  107.85  107.86  108.76  108.04
  107.72  107.68  107.63  107.59  107.58  106.41  104.07  103.13  104.67  103.49
  105.42  103.75  103.71  107.13  106.16  106.66  106.22  105.22  105.11   105.5
  104.83  105.41  104.11  103.76  104.19  106.59  106.74  107.03  105.36  105.38
  107.34  108.94  109.59  110.31  109.92   108.9  107.82  107.75  109.83  110.32
  110.09  110.73  110.01  110.32  108.54  108.85  110.69  111.64  110.82  111.02
       0       0       0       0       0   105.2   105.7       0       0       0
       0  105.53  105.48       0       0       0       0       0       0       0
       0       0       0       0       0       0       0       0       0       0
       0       0       0       0       0       0       0       0       0       0
       0       0       0       0       0       0       0       0       0       0
       0       0       0       0       0       0       0       0       0       0
       0     575     920  999.74 1173.84 1176.54 1353.39 1358.34 1558.13 1578.11
  1588.8  1608.8 1613.07 1707.97 1767.85 1782.74 1797.64 1812.54  1862.2  1906.9
 1956.56 1976.43 1986.36 2026.09 2055.89 2125.42 2135.35 2140.32 2150.25 2165.15
 2294.62 2314.57 2339.52 2359.48 2404.38 2449.28 2464.25  2534.1 2564.03 2588.98
 2608.94 2633.88 2733.67 2743.65 2828.46 2873.37 2883.34  2903.3 2943.21 2968.16
 3018.05 3107.86 3142.78 3152.76 3202.65  3227.6  3272.5 3282.48 3297.45 3427.17
  108.28  105.86  104.98  105.16  107.34  107.35  107.85  107.86  108.76  107.96
  107.85  107.76  107.75  107.74  106.81  106.41  104.07  103.13  104.67  103.49
  105.42  103.75  103.71  107.13  106.16  106.66  106.22  105.22  105.11   105.5
  104.83  105.41  104.11  103.76  104.19  106.59  106.74  107.03  105.36  105.38
  107.34  108.94  109.59  110.31  109.92   108.9  107.82  107.75  109.83  110.32
  110.09  110.73  110.01  110.32  108.54  108.85  110.69  111.64  110.82  111.02
       0       0       0       0       0   105.1   105.6       0       0       0
  105.43  105.38       0       0       0       0       0       0       0       0
       0       0       0       0       0       0       0       0       0       0
       0       0       0       0       0       0       0       0       0       0
       0       0       0       0       0       0       0       0       0       0
       0       0       0       0       0       0       0       0       0       0
Pier Skew, UpSta & Num, DnSta & Num=  ,1199.7, 2 ,1199.7, 2 , 0 , 0 , 0 ,,
     1.4     1.4
      90   106.5
     1.4     1.4
      90   106.5
Pier Skew, UpSta & Num, DnSta & Num=  ,1234.7, 2 ,1234.7, 2 , 0 , 0 , 0 ,,
     1.4     1.4
      90   106.5
     1.4     1.4
      90   106.5
Pier Skew, UpSta & Num, DnSta & Num=  ,1270.4, 2 ,1270.4, 2 , 0 , 0 , 0 ,,
     1.4     1.4
      90   106.5
     1.4     1.4
      90   106.5
Pier Skew, UpSta & Num, DnSta & Num=  ,1305.7, 2 ,1305.7, 2 , 0 , 0 , 0 ,,
     1.4     1.4
      90   106.5
     1.4     1.4
      90   106.5
BR Coef=-1 , 1 , 1 ,0.9, 0 ,,,0.8,-1,1.2,1,
WSPro=,,,, 1 ,,,, 0 ,,,, 0 ,,,,-1 ,-1 ,-1 , 0 , 0 , 0 , 0 , 0
BC Design=,, 0 ,, 0 ,,,,,,
BC Use User HTab Curves=0
BC User HTab FreeFlow(D)= 0

Type RM Length L Ch R = 1 ,52832.13,589.6,510.91,266.54
BEGIN DESCRIPTION:
Downstream Section - ADDICKS-SATSUMA RD
Main Chan. Skewed 45 Degrees
END DESCRIPTION:
XS GIS Cut Line= 6
3035672.0039679413876017.6907196 3035713.790301713875068.6102687
3035717.9175900213874770.18238793035739.15540844 13874261.172251
3035463.1306980313873890.86163993034681.0673015313872971.0061962
#Sta/Elev= 30
       0  108.26     630  104.61     670  106.67 1048.71  106.04 1099.23  104.63
1148.623  103.321173.244   94.931231.616   93.121310.699   95.521335.419  101.83
1363.675  103.94 1533.15  103.65 1568.12  101.96 1598.08   95.44 1628.05  103.72
    1678  104.54 1707.97  102.97  1862.2  105.54    1892  102.96 1981.67  104.13
 2011.19   105.8 2284.64  102.66  2489.2  107.19 2598.96  105.56 2703.73  109.45
 2838.44   109.8 2943.21  107.48  2998.1  109.69 3247.56  108.41 3427.17  110.84
#Mann= 5 ,-1 , 0
       0     .15       0 1048.71     .07       0 1099.23     .04       0
    1678     .07       0 1981.67     .15       0
#XS Ineff= 4 ,-1
       0 1176.27  105.44 1353.78 1587.88  105.84 1609.05 2011.19  103.37
 2011.19 3427.17   105.8
Permanent Ineff=
       F       F       F       F
Bank Sta=1099.23,1678
XS Rating Curve= 0 ,0
Exp/Cntr=0.5,0.3

Type RM Length L Ch R = 1 ,52321.22,775.81,860.6,1029.1
Node Name=E
XS GIS Cut Line= 5
3036639.6499985313875630.70330463036525.0668943713875026.5365339
3036179.1099091213874550.92987363035910.1366937813874145.4067345
3034714.3027993613872896.3281959
#Sta/Elev= 30
       0  108.81  349.96  105.47  599.94  105.68  629.89  107.24  714.62  103.29
  829.25  106.11  978.78  103.45 1113.97  105.92 1208.03  102.95 1227.89  104.78
 1239.14  103.69 1266.32   92.82 1332.87   90.44 1398.35   92.76 1431.47  103.18
  1441.4  103.97 1535.75  102.71  1659.8  105.08 1684.71  106.68 1879.59  104.89
 2004.54  101.84 2164.47  105.63 2434.35  105.84 2514.31  104.08 2734.21  108.95
 2859.16  109.17 2929.12  106.89 3039.08  110.02    3209  108.21 3418.91  110.52
#Mann= 5 ,-1 , 0
       0     .15       0 1113.97     .07       0 1227.89     .04       0
  1441.4     .07       0  1659.8     .15       0
#XS Ineff= 3 ,-1
       0  629.89  107.24  629.89 1113.97  104.08 1684.71 3418.91   105.7
Permanent Ineff=
       F       F       F
Bank Sta=1227.89,1441.4
XS Rating Curve= 0 ,0
Exp/Cntr=0.3,0.1

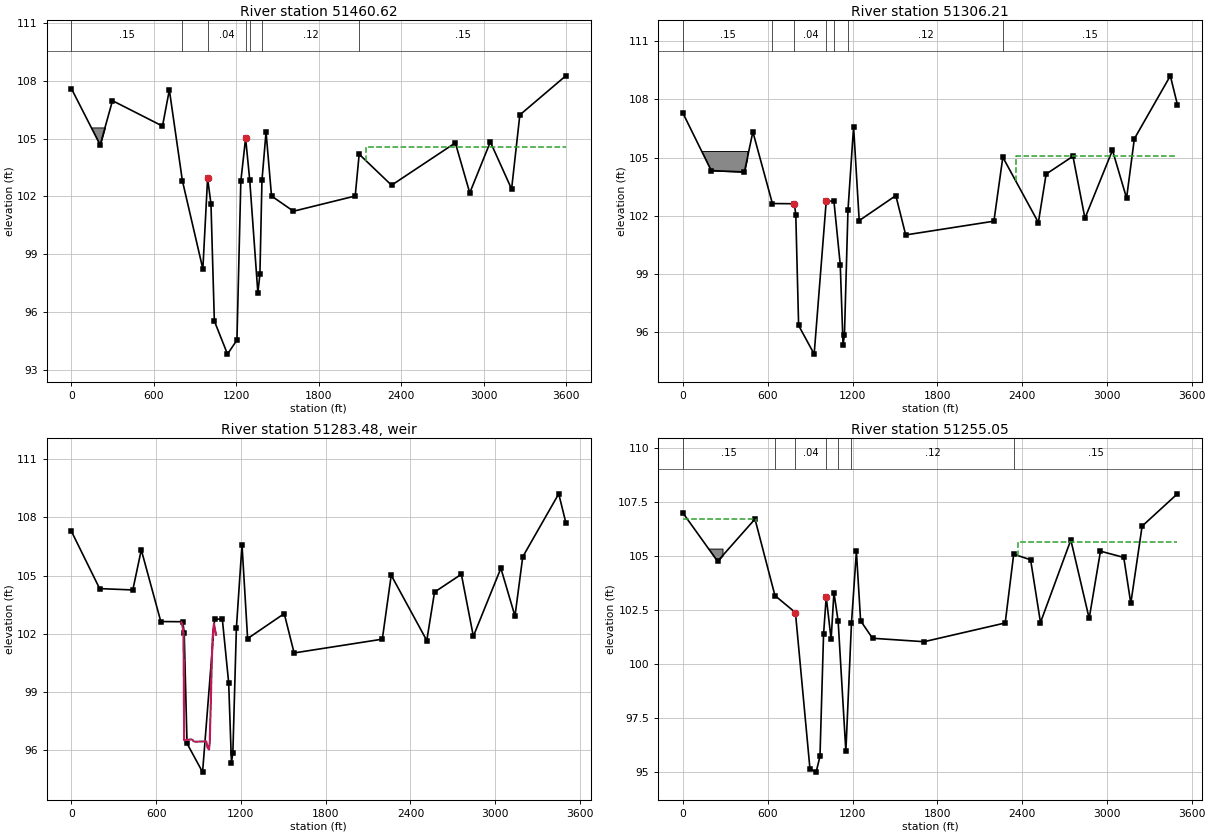
Type RM Length L Ch R = 1 ,51460.62,139.12,154.4,186.84
XS GIS Cut Line= 5
3036867.8605001113875289.55831763036849.35003844 13874362.550001
3036899.8400949413874182.65009843036978.7398715313873870.2101064
 3035586.699676613872216.8767989
#Sta/Elev= 30
       0   107.6  209.37  104.67  299.09  106.97  662.99  105.65  712.84  107.53
  807.53  102.82   956.7   98.23  991.12  102.94  1015.7  101.61 1040.29   95.53
 1135.93   93.81 1204.68   94.54 1233.03   102.8 1267.73  105.02 1297.48  102.87
 1356.97   96.99 1371.84   97.96 1386.72  102.83 1416.46  105.34 1456.26  102.02
 1615.99  101.23 2065.22  102.02 2094.12  104.19 2329.77  102.58 2793.98  104.78
  2898.8  102.18 3048.55  104.83 3203.29  102.38 3263.19  106.23 3597.62  108.26
#Mann= 7 ,-1 , 0
       0     .15       0  807.53     .07       0  991.12     .04       0
 1267.73     .12       0 1297.48    .055       0 1386.72     .12       0
 2094.12     .15       0
#XS Ineff= 3 ,-1
       0  712.84  107.53  712.84  991.12  102.94 2145.09 3597.62  104.59
Permanent Ineff=
       F       T       F
#Block Obstruct= 2 , 0
       0  249.25  105.58               0
Bank Sta=991.12,1267.73
XS Rating Curve= 0 ,0
Exp/Cntr=0.5,0.3

Type RM Length L Ch R = 1 ,51306.21,50.66,51.17,30.11
BEGIN DESCRIPTION:
Upstream Section - DAM D/S OF ADDICKS-SATSUMA
END DESCRIPTION:
Node Name=D
XS GIS Cut Line= 6
3037055.4008074413875103.63775773036986.3999611913874352.2501529
3037043.72694628 13874239.0187523037110.1999104513874107.7201301
3037135.0584565313873790.69976683035786.21010436 13872113.089933
#Sta/Elev= 30
       0  107.29  199.88  104.33  434.74  104.26   494.7  106.33  632.87  102.63
  788.72  102.62  798.48  102.04  818.46   96.34  928.48   94.86 1013.92  102.76
 1068.38  102.75  1113.1   99.48 1132.97   95.34 1142.91   95.87 1167.76  102.29
  1207.5  106.59 1247.25  101.75 1506.45  103.04 1576.37  101.01 2200.68  101.72
 2263.71  105.02 2515.33  101.65 2570.27  104.15 2760.05  105.07 2844.96  101.87
 3039.74  105.38 3139.62  102.91 3194.56  105.97 3449.27  109.22 3499.22  107.74
#Mann= 7 ,-1 , 0
       0     .15       0  632.87     .07       0  788.72     .04       0
 1013.92     .12       0 1068.38    .055       0 1167.76     .12       0
 2263.71     .15       0
#XS Ineff= 2 ,-1
       0   494.7  106.33 2355.51 3499.22  105.07
Permanent Ineff=
       F       F
#Block Obstruct= 2 , 0
       0  454.73  105.34               0
Bank Sta=788.72,1013.92
XS Rating Curve= 0 ,0
Exp/Cntr=0.5,0.3

Type RM Length L Ch R = 5 ,51283.48,,,
BEGIN DESCRIPTION:
DAM D/S OF ADDICKS-SATSUMA
END DESCRIPTION:
Node Name=DAM DS ADKS-SAT
IW Pilot Flow=0
#Inline Weir SE= 29
  778.75  102.58  783.59  102.53  793.28     102  798.12   96.51  802.96   96.51
  812.64   96.52  817.48   96.52  822.32   96.53  827.16   96.53  836.84   96.54
  841.68   96.54  846.53   96.55  856.21   96.53  865.89   96.45  880.41   96.43
  890.29   96.43  910.06   96.44  929.82   96.44  934.76   96.44  954.52   96.45
   964.4   96.11  974.28   96.02  979.23   96.41  984.17   97.72  994.05  100.63
  998.99  101.71 1003.93  102.22 1008.87  102.52 1023.69  101.95
IW Dist,WD,Coef,Skew,MaxSub,Min_El,Is_Ogee,SpillHt,DesHd
11,22.5,2.6,0,0.98,, 0 ,,,0,0,

Type RM Length L Ch R = 1 ,51255.05,26.62,24.41,93.58
BEGIN DESCRIPTION:
Downstream Section - DAM D/S OF ADDICKS-SATSUMA
END DESCRIPTION:
XS GIS Cut Line= 6
3037104.4400794513875118.7272944 3037035.439233213874367.3396896
 3037092.267859713874255.09286693037159.2391824413874122.8096669
3037184.0977285213873805.78930353035835.2493763613872128.1794698
#Sta/Elev= 30
       0     107  244.85  104.76   509.7  106.72  650.88  103.17  795.95  102.38
  898.56   95.14  942.31   94.98  969.57   95.71  994.95  101.37 1013.81  103.11
 1048.51  101.14 1068.38  103.31 1098.19  101.98 1152.85   95.94  1192.6   101.9
 1227.38  105.22 1257.19     102 1341.66  101.19 1706.23  101.03 2280.59   101.9
 2340.66  105.09 2460.39  104.83 2530.31  101.92 2745.07  105.75 2874.92  102.11
 2954.83  105.23 3119.65  104.94 3169.59  102.81  3249.5  106.39 3499.22  107.89
#Mann= 7 ,-1 , 0
       0     .15       0  650.88     .07       0  795.95     .04       0
 1013.81     .12       0 1098.19    .055       0  1192.6     .12       0
 2340.66     .15       0
#XS Ineff= 2 ,-1
       0  514.69  106.74 2370.49 3499.22  105.66
Permanent Ineff=
       F       F
#Block Obstruct= 2 , 0
       0  279.83  105.35               0
Bank Sta=795.95,1013.81
XS Rating Curve= 0 ,0
Exp/Cntr=0.5,0.3