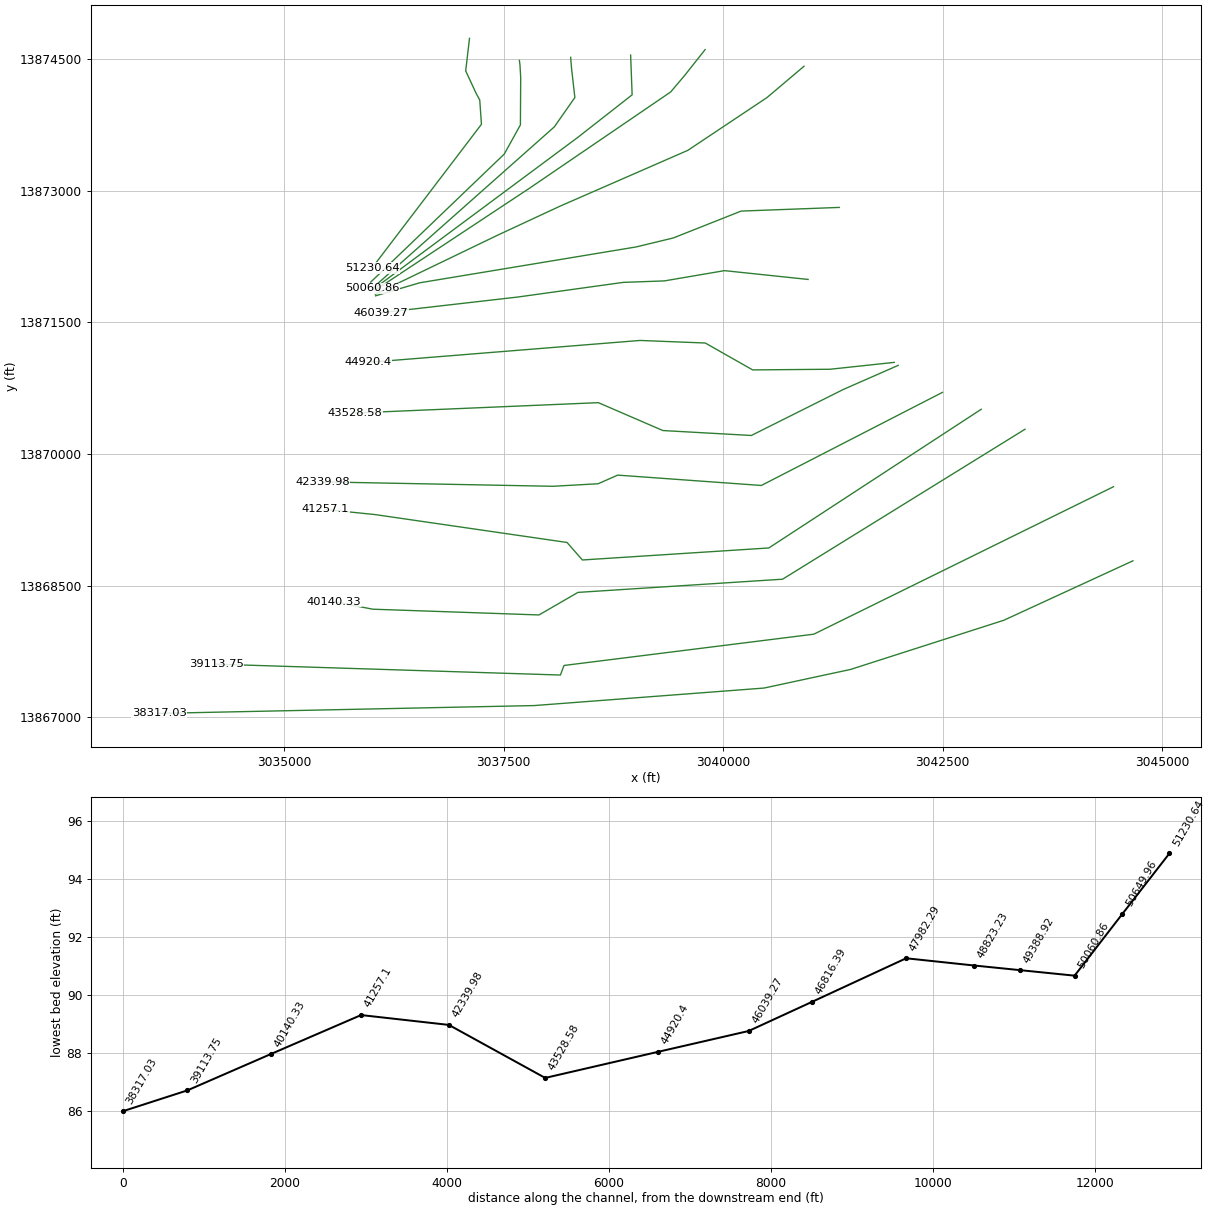
HEC-RAS study U100-00-00.prj: U100-00-00

--- U100-00-00.g01 (geometry) --- (continued)

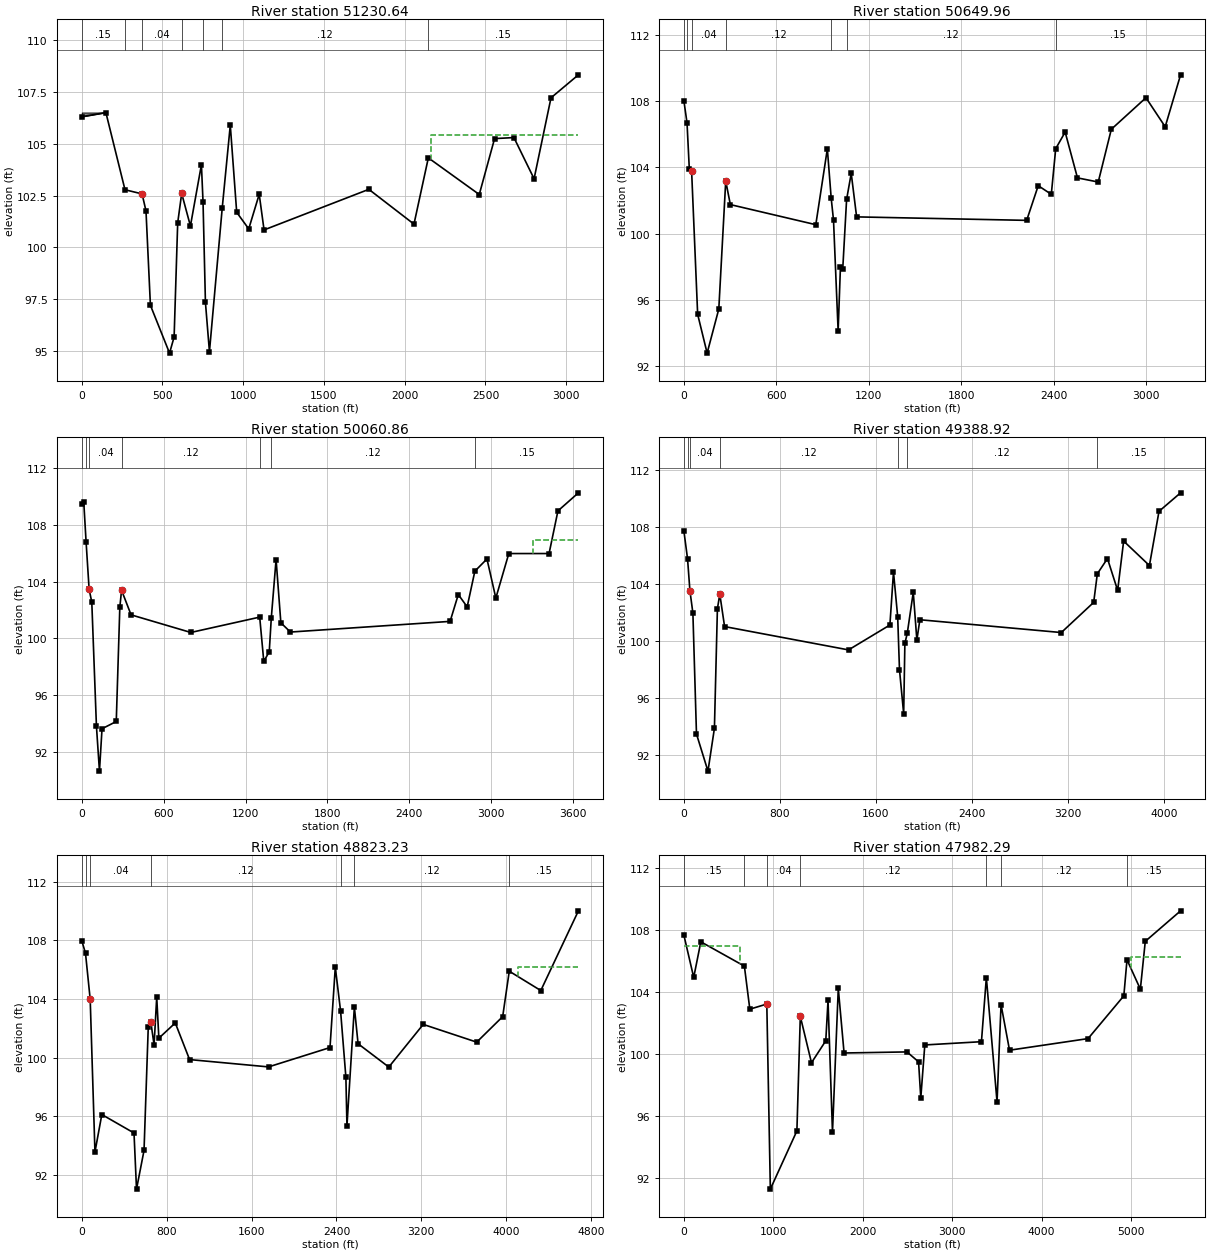
Type RM Length L Ch R = 1 ,51230.64,621.14,580.68,393.81
XS GIS Cut Line= 6
3037111.2464962813874734.41343053037067.8673179413874363.4689624
3037188.0501484413874105.10005663037227.9001343513874032.6500703
3037247.3124971113873755.30121553036001.2798841913872119.1601309
#Sta/Elev= 30
       0  106.31  149.39  106.51  267.78  102.78  373.47  102.58   397.8  101.76
  425.24    97.2   543.7   94.89  571.98   95.67  594.15  101.18  618.87   102.6
  673.02  101.03  741.11  103.99  751.04   102.2  765.94   97.34  790.76   94.96
   870.2  101.92  919.85   105.9  959.56  101.69 1034.12  100.89 1099.01  102.56
 1128.96  100.84 1777.88   102.8 2057.42  101.12 2146.33  104.32 2461.75  102.55
 2556.59  105.25  2676.4   105.3 2801.19  103.31 2906.02  107.22 3075.74  108.33
#Mann= 7 ,-1 , 0
       0     .15       0  267.78     .07       0  373.47     .04       0
  618.87     .12       0  751.04    .055       0   870.2     .12       0
 2146.33     .15       0
#XS Ineff= 1 ,-1
 2162.24 3075.74  105.44
Permanent Ineff=
       F
#Block Obstruct= 2 , 0
       0  149.39  106.51               0
Bank Sta=373.47,618.87
XS Rating Curve= 0 ,0
Exp/Cntr=0.3,0.1

Type RM Length L Ch R = 1 ,50649.96,583.72,589.1,140.78
XS GIS Cut Line= 6
3037679.4146512713874483.25710873037686.2801231113874428.7499999
3037694.3099626913874287.53998043037691.0199430313873748.1201275
3037506.83002269 13873415.9101623035985.7300465313871957.5699029
#Sta/Elev= 30
       0  107.99   20.04  106.68   34.96   103.9   49.94  103.77   89.08   95.14
  150.59    92.8  226.34   95.46   271.3  103.17  301.27  101.75  855.76  100.54
  930.73  105.11  955.72  102.13  970.72  100.81  1000.7   94.14  1015.7   98.01
 1030.69   97.88 1055.68  102.06 1085.67  103.63 1120.65  101.01 2224.21   100.8
 2299.12  102.89 2384.01  102.37 2412.64  105.12 2473.89  106.12 2553.79  103.36
 2688.61  103.11  2773.5  106.29 2998.21  108.19 3123.05  106.44 3222.92  109.57
#Mann= 7 ,-1 , 0
       0     .15       0   20.04     .07       0   49.94     .04       0
   271.3     .12       0  955.72    .055       0 1055.68     .12       0
 2412.64     .15       0
#XS Ineff= 1 ,-1
 2473.89 3222.92  106.12
Permanent Ineff=
       F
Bank Sta=49.94,271.3
XS Rating Curve= 0 ,0
Exp/Cntr=0.3,0.1

Type RM Length L Ch R = 1 ,50060.86,680.59,671.94,200.42
XS GIS Cut Line= 5
3038263.3399926113874518.30001763038273.7500767713874391.2100487
3038311.2299886913874060.13984473038077.3098528513873725.9699094
3036005.4501514413871888.0300157
#Sta/Elev= 30
       0  109.44   14.71  109.59    31.8  106.79   53.95  103.46   73.57  102.55
  107.59   93.83  129.76   90.67  148.49   93.65  252.81   94.16  278.89  102.19
  291.62  103.39  361.24  101.66  798.97  100.42 1303.54   101.5 1333.54   98.38
 1373.53   99.07 1388.53  101.45 1423.53  105.55 1458.52   101.1 1528.51  100.45
 2698.34   101.2 2758.33  103.09 2823.32  102.22 2879.59  104.73  2968.3  105.59
 3033.29  102.84 3128.28  105.97 3423.23  105.97 3488.22  108.97  3638.2  110.24
#Mann= 7 ,-1 , 0
       0     .15       0    31.8     .07       0   53.95     .04       0
  291.62     .12       0 1303.54    .055       0 1388.53     .12       0
 2879.59     .15       0
#XS Ineff= 2 ,-1
  2968.3 3303.25  105.59 3303.25  3638.2  106.95
Permanent Ineff=
       F       F
Bank Sta=53.95,291.62
XS Rating Curve= 0 ,0
Exp/Cntr=0.3,0.1

Type RM Length L Ch R = 1 ,49388.92,804.52,565.69,142.96
XS GIS Cut Line= 4
3038946.46756336 13874543.9394023038963.5613611913874090.9485101
3038342.9917361913873604.85532223036017.9698114413871877.9417813
#Sta/Elev= 30
       0  107.72   30.24  105.78   49.81  103.55   74.72  101.97  104.61   93.47
  200.29   90.86  254.05   93.87  278.96  102.27  298.89   103.3  338.74  101.02
 1371.43   99.38 1715.97  101.13 1745.94  104.85 1780.89  101.71 1795.87   97.99
 1830.82   94.89 1840.81   99.84 1860.78  100.55 1910.72  103.43 1940.68  100.07
 1965.65   101.5 3144.09   100.6 3413.73  102.72 3444.18  104.73 3528.58   105.8
 3613.47  103.56  3663.4  107.03 3878.11  105.31 3958.01  109.12 4137.77  110.42
#Mann= 7 ,-1 , 0
       0     .15       0   30.24     .07       0   49.81     .04       0
  298.89     .12       0 1780.89    .055       0 1860.78     .12       0
 3444.18     .15       0
#XS Ineff= 2 ,-1
 3528.58  3663.4   105.8  3663.4 4137.77  107.03
Permanent Ineff=
       F       F
Bank Sta=49.81,298.89
XS Rating Curve= 0 ,0
Exp/Cntr=0.3,0.1

Type RM Length L Ch R = 1 ,48823.23,818.13,840.94,292.49
BEGIN DESCRIPTION:
Confluence with Horsepen Creek (U106-00-00)
END DESCRIPTION:
XS GIS Cut Line= 5
3039794.7700006113874605.91992113039563.11987336 13874313.309942
3039402.6398793613874123.66005893037797.8501099513873029.4801606
3036032.5800184513871862.3601195
#Sta/Elev= 30
       0  107.98   35.37  107.11   79.62  103.97   124.4   93.55  189.09   96.11
  492.46   94.85  516.05   91.02  586.86   93.66  626.64  102.06   651.6  102.39
  681.56  100.86  706.53  104.13   726.5  101.32  881.28  102.36  1016.1   99.86
 1760.07   99.36 2339.27  100.68  2389.2  106.16 2439.13  103.17 2489.06   98.65
 2499.05   95.34 2568.95  103.44 2603.89  100.94 2893.36   99.35 3217.78  102.26
 3721.87  101.05 3966.42  102.79 4028.64  105.89 4325.79  104.57 4680.16  110.01
#Mann= 7 ,-1 , 0
       0     .15       0   35.37     .07       0   79.62     .04       0
   651.6     .12       0 2439.13    .055       0 2568.95     .12       0
 4028.64     .15       0
#XS Ineff= 2 , 0
       0                 4111.16       0  106.16
Permanent Ineff=
       F       F
Bank Sta=79.62,651.6
XS Rating Curve= 0 ,0
Exp/Cntr=0.3,0.1

Type RM Length L Ch R = 1 ,47982.29,1188.17,1165.9,660.66
XS GIS Cut Line= 6
3040921.6155159513874416.70081143040500.0500861113874060.1398447
3039597.7900796113873458.62989293038144.1400997813872823.7099029
3037425.6700800213872489.53996753036038.8700321213871821.1899263
#Sta/Elev= 30
       0  107.66  109.43  104.94  189.02  107.24  676.13  105.67  737.03  102.89
  926.92  103.22  966.62   91.27 1263.42   95.03 1301.71  102.42 1426.64   99.43
 1586.55  100.85 1611.53  103.45 1661.46   94.95 1726.31  104.23 1791.15  100.06
  2494.5  100.13 2624.19   99.49 2649.13   97.16 2694.03  100.58 3327.44  100.79
 3382.26  104.93 3501.86    96.9 3546.72  103.18 3641.41  100.24 4519.99  100.99
 4919.83  103.75 4955.41  106.08 5104.76  104.18 5159.74  107.27 5554.59  109.24
#Mann= 7 ,-1 , 0
       0     .15       0  676.13     .07       0  926.92     .04       0
 1301.71     .12       0 3382.26    .055       0 3546.72     .12       0
 4955.41     .15       0
#XS Ineff= 2 , 0
       0  632.09     107  4999.8       0  106.23
Permanent Ineff=
       F       F
Bank Sta=926.92,1301.71
XS Rating Curve= 0 ,0
Exp/Cntr=0.3,0.1

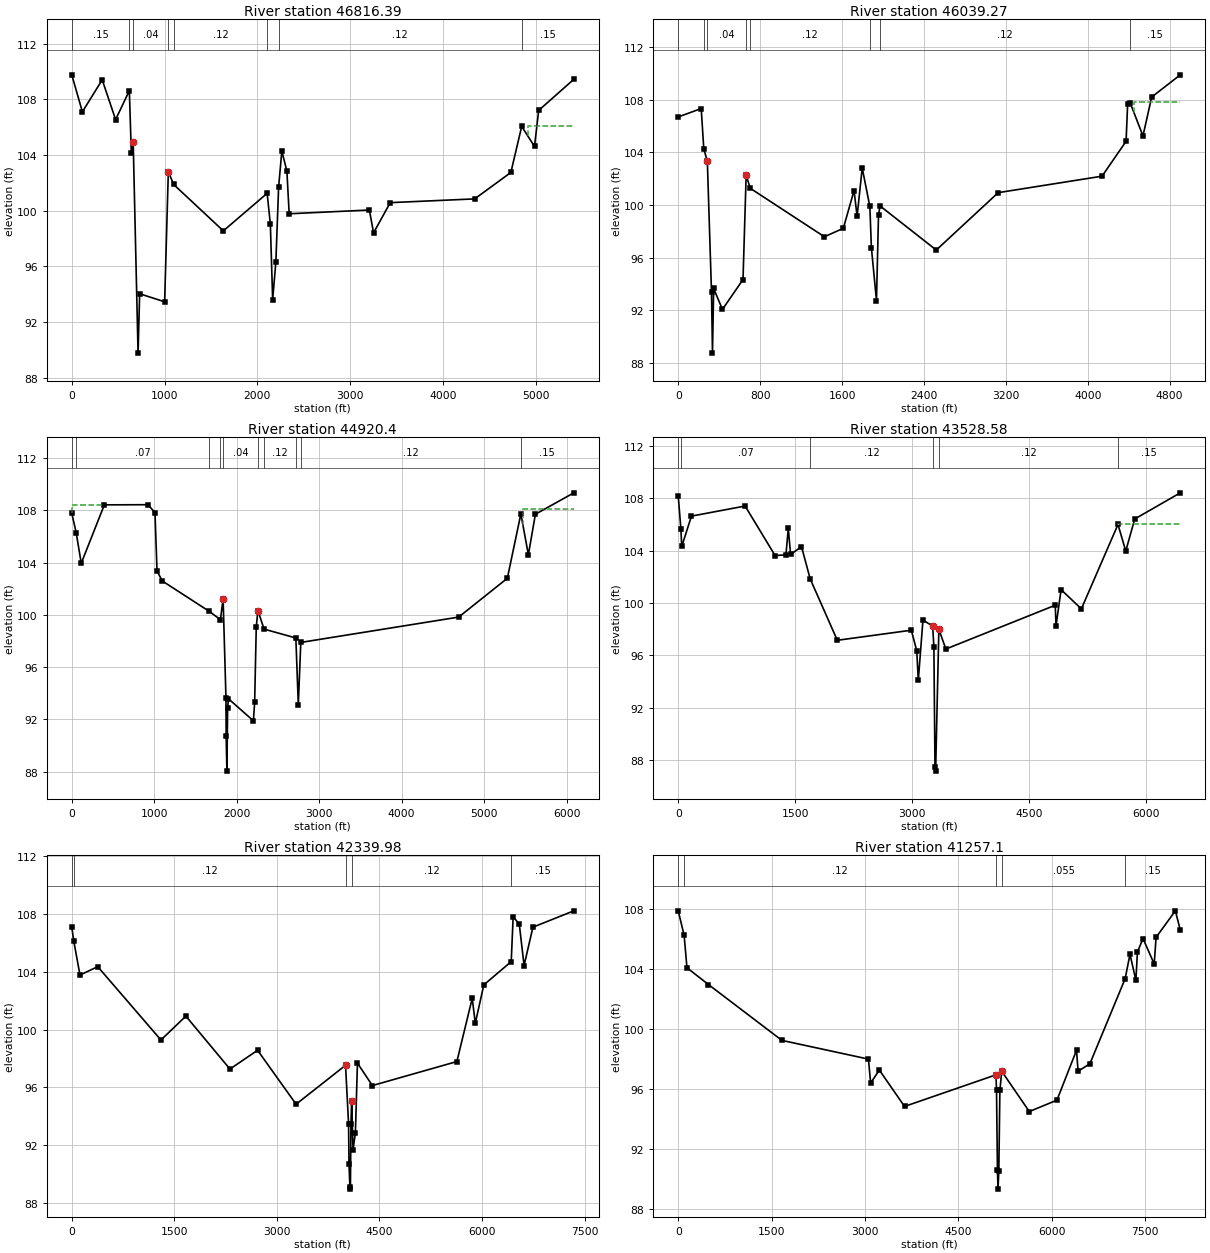
Type RM Length L Ch R = 1 ,46816.39,785.59,777.11,493.55
XS GIS Cut Line= 6
3041322.4805278613872808.55835843040205.03000686 13872766.879964
3039431.8199391113872460.50984193039008.7400766213872358.3899674
3036543.2000601913871949.89997073036040.8546081913871801.8546631
#Sta/Elev= 30
       0  109.77  114.32  107.11  328.05  109.41  472.33  106.55  620.38  108.63
  641.78  104.12  661.71  104.97  714.34   89.76  731.48   94.03  1000.6   93.45
 1040.47  102.81 1097.48  101.89 1633.17   98.55 2105.22  101.25 2139.84   99.03
 2164.57   93.61 2199.19   96.32 2228.86   101.7 2263.48  104.29 2317.89  102.85
 2342.62   99.78 3206.85  100.05 3251.83   98.41 3431.77  100.58 4341.47  100.85
 4731.35  102.75 4848.06  106.06 4986.06  104.62 5030.95  107.21 5410.01  109.45
#Mann= 8 ,-1 , 0
       0     .15       0  620.38     .07       0  661.71     .04       0
 1040.47     .07       0 1097.48     .12       0 2105.22    .055       0
 2228.86     .12       0 4848.06     .15       0
#XS Ineff= 1 ,-1
 4911.25 5410.01  106.07
Permanent Ineff=
       F
Bank Sta=661.71,1040.47
XS Rating Curve= 0 ,0
Exp/Cntr=0.3,0.1

Type RM Length L Ch R = 1 ,46039.27,1140.12,1118.88,713.53
XS GIS Cut Line= 6
 3040967.890029713871988.28014333040015.4998741213872088.5299428
3039330.4500631113871971.56987493038862.6101195213871954.8599345
3037659.5898877813871787.77988813036100.7682022813871608.7740125
#Sta/Elev= 30
       0   106.7  224.45  107.34  249.52  104.28   284.3  103.33  324.99   93.38
  334.54   88.76  346.01   93.67   431.7   92.08  632.73   94.35  663.37  102.27
   703.8  101.28 1427.63    97.6 1612.61   98.24 1717.36  101.11 1747.24   99.15
 1797.04  102.82 1871.74    99.9 1886.68   96.78 1936.48   92.75 1956.41   99.28
 1971.35   99.94 2520.61   96.59  3125.4  100.95 4139.85   102.2 4374.71  104.85
  4389.7  107.66  4415.7  107.75 4539.61  105.26 4624.56  108.21  4904.4   109.9
#Mann= 8 ,-1 , 0
       0     .15       0  249.52     .07       0   284.3     .04       0
  663.37     .07       0   703.8     .12       0 1871.74    .055       0
 1971.35     .12       0  4415.7     .15       0
#XS Ineff= 1 ,-1
 4454.66  4904.4  107.83
Permanent Ineff=
       F
Bank Sta=284.3,663.37
XS Rating Curve= 0 ,0
Exp/Cntr=0.3,0.1

Type RM Length L Ch R = 1 ,44920.4 ,1072.9,1391.81,705.19
Node Name=C
XS GIS Cut Line= 6
3041948.7043410213871043.61995913041218.0617734513870965.3865198
3040336.3299411113870957.8501175 3039796.540010213871264.2199116
 3039052.500159713871293.3901289 3035956.470918713871043.5901035
#Sta/Elev= 30
       0  107.78   53.22   106.3  114.97  103.95   394.9  108.42  924.12  108.43
 1008.81  107.83 1033.72  103.35 1098.48  102.59 1669.12  100.26 1802.73   99.63
 1835.06  101.22 1869.82    93.6 1872.08   90.74 1880.82   88.04 1889.68   92.87
 1899.61   93.58  2202.5   91.89 2217.39    93.3 2237.25    99.1 2257.24  100.33
 2331.48   98.91 2717.01   98.23 2746.99   93.11 2776.97   97.89 4691.63   99.83
 5281.55   102.8 5445.63  107.73 5536.51   104.6  5621.5   107.7 6087.96  109.34
#Mann= 10 ,-1 , 0
       0     .15       0   53.22     .07       0 1669.12     .12       0
 1802.73     .07       0 1835.06     .04       0 2257.24     .07       0
 2331.48     .12       0 2717.01    .055       0 2776.97     .12       0
 5445.63     .15       0
#XS Ineff= 2 ,-1
       0   394.9  108.42 5471.52 6087.96  108.07
Permanent Ineff=
       F       F
Bank Sta=1835.06,2257.24
XS Rating Curve= 0 ,0
Exp/Cntr=0.3,0.1

Type RM Length L Ch R = 1 ,43528.58,667.78,1188.61,1011.81
XS GIS Cut Line= 6
3041994.1369929513871009.54522413041368.88988386 13870735.139933
3040321.3486718513870211.00876343039313.7401227813870267.2999894
3038578.5601626913870584.75998443035809.3157011913870467.2123193
#Sta/Elev= 30
       0  108.17   33.73  105.67   44.86  104.31  169.46  106.63  857.27   107.4
 1241.07  103.62 1380.64  103.67 1410.54  105.69 1440.45   103.7 1580.02   104.3
 1690.99  101.84 2039.01   97.14 2987.67   97.91 3057.31   96.34  3077.2   94.08
 3136.89   98.68 3261.24   98.23 3277.03   96.63 3291.08   87.49  3299.4   87.14
 3340.82   97.98 3430.35   96.47 4832.75   99.82 4842.74   98.24 4907.66  101.01
 5167.36   99.54 5636.85  105.99 5736.69  103.96 5851.56  106.41 6435.87  108.41
#Mann= 6 ,-1 , 0
       0     .15       0   33.73     .07       0 1690.99     .12       0
 3261.24    .055       0 3340.82     .12       0 5636.85     .15       0
#XS Ineff= 2 ,-1
       0  169.46  106.63 5635.85 6435.87  105.99
Permanent Ineff=
       F       F
Bank Sta=3261.24,3340.82
XS Rating Curve= 0 ,0
Exp/Cntr=0.3,0.1

Type RM Length L Ch R = 1 ,42339.98,799.25,1082.88,765.19
Node Name=B
XS GIS Cut Line= 6
3042497.1500945213870701.66985563040435.2168824413869641.6670544
3038799.2099838613869759.57987633038575.9099055213869661.1699681
3038060.5999125213869632.37015693035437.3600802713869682.4999779
#Sta/Elev= 30
       0  107.08   29.65  106.11  119.92  103.77  379.74  104.35 1304.13   99.28
 1668.88  100.93 2313.44   97.27 2717.28   98.57 3280.65   94.84  4003.5   97.53
 4048.32   93.47 4053.97   90.74 4068.81   88.97 4074.97    89.1 4083.18    93.5
 4093.14   95.05 4113.06   91.69 4147.92   92.85  4177.8   97.68 4396.25   96.13
 5631.86   97.79 5856.37  102.16 5901.28  100.44 6026.01  103.09 6426.71   104.7
 6455.07  107.81 6544.82  107.28 6614.62  104.43 6744.25  107.08 7342.54  108.21
#Mann= 5 ,-1 , 0
       0     .15       0   29.65     .12       0  4003.5    .055       0
 4093.14     .12       0 6426.71     .15       0
Bank Sta=4003.5,4093.14
XS Rating Curve= 0 ,0
Exp/Cntr=0.3,0.1

Type RM Length L Ch R = 1 ,41257.1 ,365.66,1116.77,944.42
XS GIS Cut Line= 6
3042940.3204680213870509.91302133040520.61828645     13868929.99
3038396.6901196113868793.02012963038222.13994378 13868992.489875
3036034.2099364413869310.33241523035468.3482072813869368.1164204
#Sta/Elev= 30
       0  107.89   94.81  106.25  139.99  104.09  484.97  102.97  1664.9   99.24
 3054.69   97.99 3089.66   96.39 3229.55   97.26 3634.24   94.83  5101.6   96.94
 5111.42   95.93 5126.15   90.57  5135.2   89.31 5148.27   90.51 5165.41    95.9
 5194.86   97.18 5637.56   94.49 6081.73   95.25 6396.15   98.58  6421.1   97.18
 6610.75   97.68 7177.12  103.36 7254.55  104.99 7349.37  103.25 7374.33  105.15
 7464.16  106.04 7643.79  104.34 7673.72  106.12 7983.07  107.89  8062.9  106.61
#Mann= 5 ,-1 , 0
       0     .15       0   94.81     .12       0  5101.6     .04       0
 5194.86    .055       0 7177.12     .15       0
Bank Sta=5101.6,5194.86
XS Rating Curve= 0 ,0
Exp/Cntr=0.3,0.1

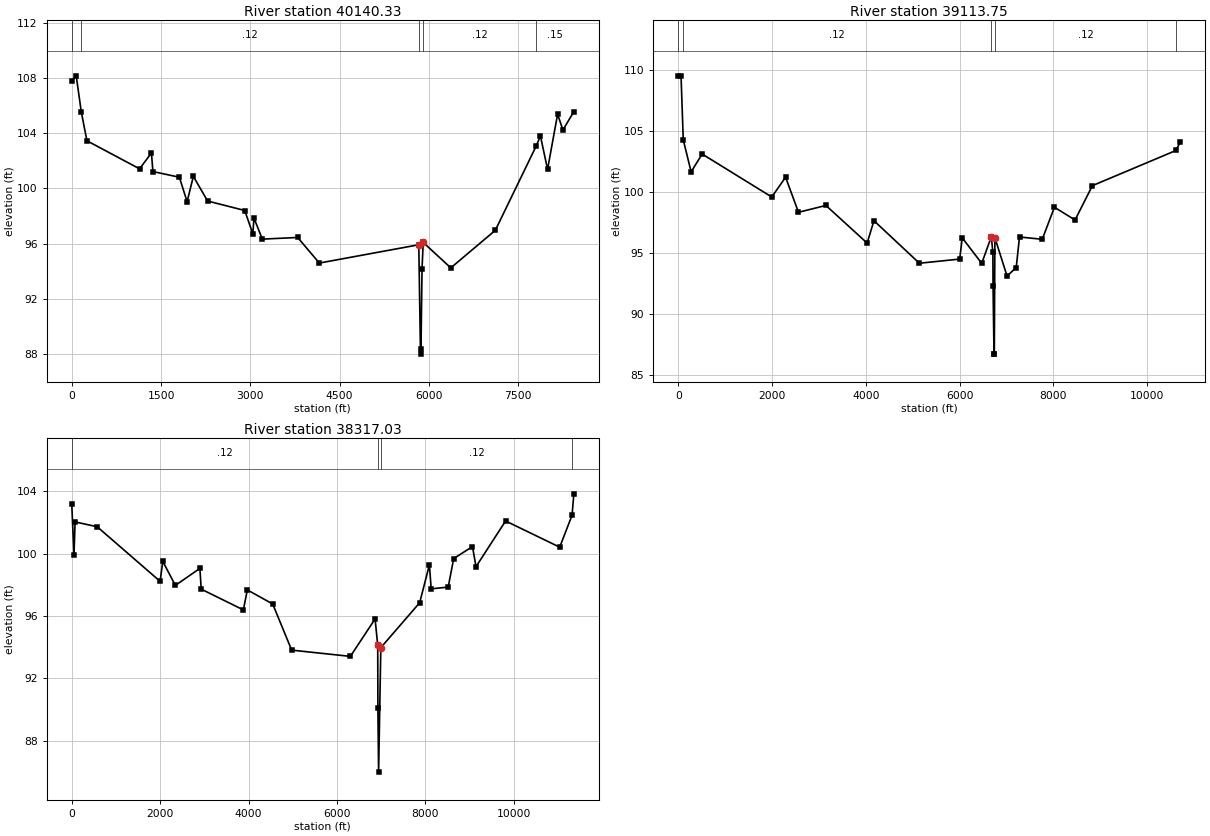
Type RM Length L Ch R = 1 ,40140.33,713.13,1026.58,681.68
XS GIS Cut Line= 6
3043438.49434045 13870282.1762723040677.1871990313868574.1511448
3038346.3998658713868423.74002833037902.8899261113868166.9698725
 3036008.584987713868232.54618493035570.1550902713868317.8688489
#Sta/Elev= 30
       0  107.85   74.93  108.19  160.23  105.56  254.75  103.47  1138.9  101.43
 1338.71  102.58 1363.69  101.23 1808.26  100.82 1938.13   99.04 2043.03  100.88
  2282.8   99.09  2907.2    98.4 3042.07    96.7 3062.06   97.85 3201.92   96.32
 3795.86   96.44 4160.18   94.58 5831.31   95.91 5860.26   87.96 5868.35   88.35
 5886.04   94.18 5905.95   96.08 6369.35   94.23 7117.54   96.96 7802.51  103.07
 7875.72  103.82  7995.4  101.39 8164.14   105.4 8253.47  104.25  8437.1  105.59
#Mann= 5 ,-1 , 0
       0     .15       0  160.23     .12       0 5831.31    .055       0
 5905.95     .12       0 7802.51     .15       0
Bank Sta=5831.31,5905.95
XS Rating Curve= 0 ,0
Exp/Cntr=0.3,0.1

Type RM Length L Ch R = 1 ,39113.75,520.29,796.72,407.93
XS GIS Cut Line= 5
3044446.1225745213869627.4774502 3041033.025726213867947.8754944
3038187.6744615313867591.54254573038146.6374701113867482.6369236
3034229.3923518713867606.2705346
#Sta/Elev= 30
       0  109.49   59.98  109.46   107.2  104.25  274.93  101.63  509.86  103.09
 1994.47   99.57 2289.39  101.19 2564.32   98.32 3149.16   98.88  4028.8    95.8
 4173.67   97.63 5142.83   94.15 6002.09   94.49 6057.04   96.23 6471.68   94.14
 6676.36   96.31 6710.08   95.03 6713.54   92.31 6734.04   86.71  6740.7   86.75
 6752.74   96.23 7012.85    93.1 7207.81    93.8 7277.79    96.3  7762.7   96.11
 8022.65   98.73 8462.56   97.69 8832.49   100.510620.72  103.3910707.12  104.11
#Mann= 5 ,-1 , 0
       0     .15       0   107.2     .12       0 6676.36    .055       0
 6752.74     .12       010620.72     .15       0
Bank Sta=6676.36,6752.74
XS Rating Curve= 0 ,0
Exp/Cntr=0.3,0.1

Type RM Length L Ch R = 1 ,38317.03,0,0,0
Node Name=A
XS GIS Cut Line= 6
3044667.8573672813868783.48012243043197.2084056913868106.5018176
3041451.2200997813867546.26999843040466.28998303 13867334.319963
3037848.12002252 13867134.8400473033577.6712143613867045.8864848
#Sta/Elev= 30
       0  103.15   49.97   99.89   74.95  102.03  574.64  101.72 1998.71   98.22
 2058.67    99.5 2343.46   97.96 2898.04   99.05 2928.02   97.72 3881.55   96.39
 3971.33   97.67 4544.98   96.77 4974.28   93.81 6302.14   93.41 6861.24   95.81
 6920.98   94.11 6924.96   90.08  6940.8   85.99 6991.03   93.97 7870.18   96.85
 8089.99   99.28 8129.95   97.74 8514.63   97.85 8639.53   99.68 9064.18  100.45
 9144.12   99.16 9813.57  102.0911037.57  100.41   11317  102.46 11357.3  103.83
#Mann= 4 ,-1 , 0
       0     .12       0 6920.98    .055       0 6991.03     .12       0
   11317     .15       0
Bank Sta=6920.98,6991.03
XS Rating Curve= 0 ,0
Exp/Cntr=0.3,0.1

Chan Stop Cuts=-1
Use User Specified Reach Order=0
Composite Channel Slope=5